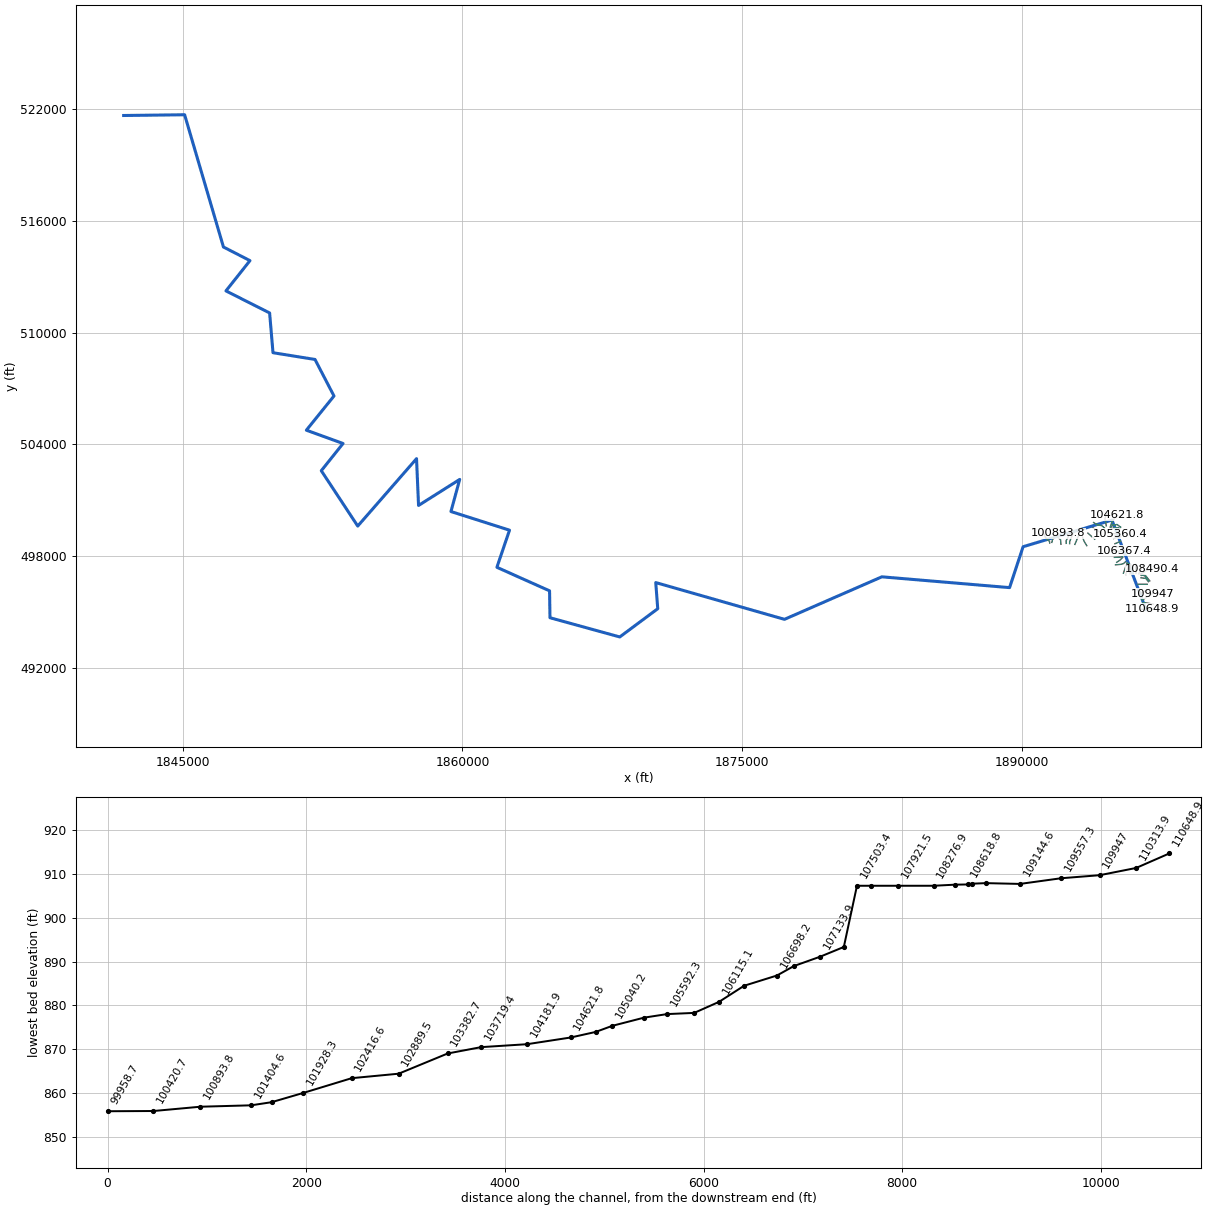
--- BLUECR.prj (project) ---

Proj Title=BLUECR
Current Plan=p01
Default Exp/Contr=0,0
English Units
Geom File=g01
Flow File=f01
Plan File=p01
BEGIN DESCRIPTION:
END DESCRIPTION:
DSS Export Rating Curves= 0
DSS Export Rating Curve Sorted= 0
DSS Export Volume Flow Curves= 0
DXF OffsetX= 0
DXF OffsetY= 0
DXF ScaleX= 0
DXF ScaleY= 0

--- BLUECR.p01 (plan) ---

Plan Title=Floodplain
Program Version=4.00
Geom File=g01
Flow File=f01
K Sum by GR=0
Std Step Tol=0.01
Critical Tol=0.01
Num of Std Step Trials=20
Max Error Tol=0.3
Flow Tol Ratio=0.001
Split Flow NTrial=30
Split Flow Tol=0.02
Split Flow Ratio=0.02
Log Output Level=0
Friction Slope Method=1
Unsteady Friction Slope Method=2
Unsteady Bridges Friction Slope Method=1
Global Log Level=0
CheckData=False
Run HTab=0
Run UNet=0
Run PostProcess=0
UNET Theta=0
UNET Theta Warmup=0
UNET ZTol=0
UNET ZSATol=0
UNET MxIter=0
UNET MaxInSteps=0
UNET DtIC=0
UNET DtMin=0
UNET MaxCRTS=0
UNET WFStab=0
UNET SFStab=0
UNET WFX=0
UNET SFX=0
UNET DSS MLevel=0
UNET DZMax Abort=0
UNET Convert EG Bridges=0
UNET Use Existing IB Tables=0
UNET Froude Limit=0
UNET Froude Power=0
Write IC File=0
Echo Input=False
Echo Output=False
Write Detailed=0

--- BLUECR.f01 (steady flow) ---

Flow Title=NFF Regression Equation
Program Version=4.10
Number of Profiles= 1
Profile Names=P100yr
River Rch & RM=BLUECR,Main            ,110648.9
1695.174
River Rch & RM=BLUECR,Main            ,109947
1701.793
River Rch & RM=BLUECR,Main            ,107921.5
1889.406
River Rch & RM=BLUECR,Main            ,105040.2
1955.116
River Rch & RM=BLUECR,Main            ,104621.8
2631.561
River Rch & RM=BLUECR,Main            ,97061.7
2814.906
River Rch & RM=BLUECR,Main            ,96766.4
3197.593
River Rch & RM=BLUECR,Main            ,94126.3
3367.911
River Rch & RM=BLUECR,Main            ,87680.8
3599.784
River Rch & RM=BLUECR,Main            ,85744.5
3840.656
River Rch & RM=BLUECR,Main            ,79154.6
3969.738
River Rch & RM=BLUECR,Main            ,78824.8
5899.687
River Rch & RM=BLUECR,Main            ,67123.3
6295.868
River Rch & RM=BLUECR,Main            ,66856.5
7736.762
River Rch & RM=BLUECR,Main            ,59417.1
8004.664
River Rch & RM=BLUECR,Main            ,46105.7
8368.527
River Rch & RM=BLUECR,Main            ,35603.9
9297.233
River Rch & RM=BLUECR,Main            ,24296.5
9600.324
River Rch & RM=BLUECR,Main            ,10212.3
10016.77
River Rch & RM=BLUECR,Main            ,4820.3
10090.45
River Rch & RM=BLUECR,Main            ,4230.6
10336.28
Boundary for River Rch & Prof#=BLUECR,Main            , 1
Up Type= 0
Dn Type= 1
Dn Known WS=629.1
DSS Import GetInterval= 0
DSS Import GetPeak= 0
DSS Import FillOption= 0

--- BLUECR.g01 (geometry) ---

Geom Title=USGS 10m DEM
Program Version=4.10

River Reach=BLUECR          ,Main
Reach XY= 30
     1896671.507      495150.132     1894848.512      499939.802
     1890079.963      498510.564     1889354.581      496316.247
     1882502.625      496895.942     1877277.226      494614.957
     1870370.611      496587.097     1870477.207      495184.003
     1868439.852      493669.569     1864695.735      494700.904
     1864673.295      496143.535     1861847.157       497406.49
     1862524.095      499397.931     1859381.861      500398.991
     1859850.665      502120.451     1857643.292      500724.443
     1857535.198      503236.078     1854380.907      499618.619
     1852425.999      502589.149      1853592.12      504049.283
     1851624.427      504762.849     1853106.094      506597.849
     1852088.156       508558.08     1849833.992      508920.132
     1849652.808      511052.982     1847310.447      512236.862
     1848597.508      513860.392     1847175.448       514592.27
     1845092.522      521687.356     1841820.127       521648.08

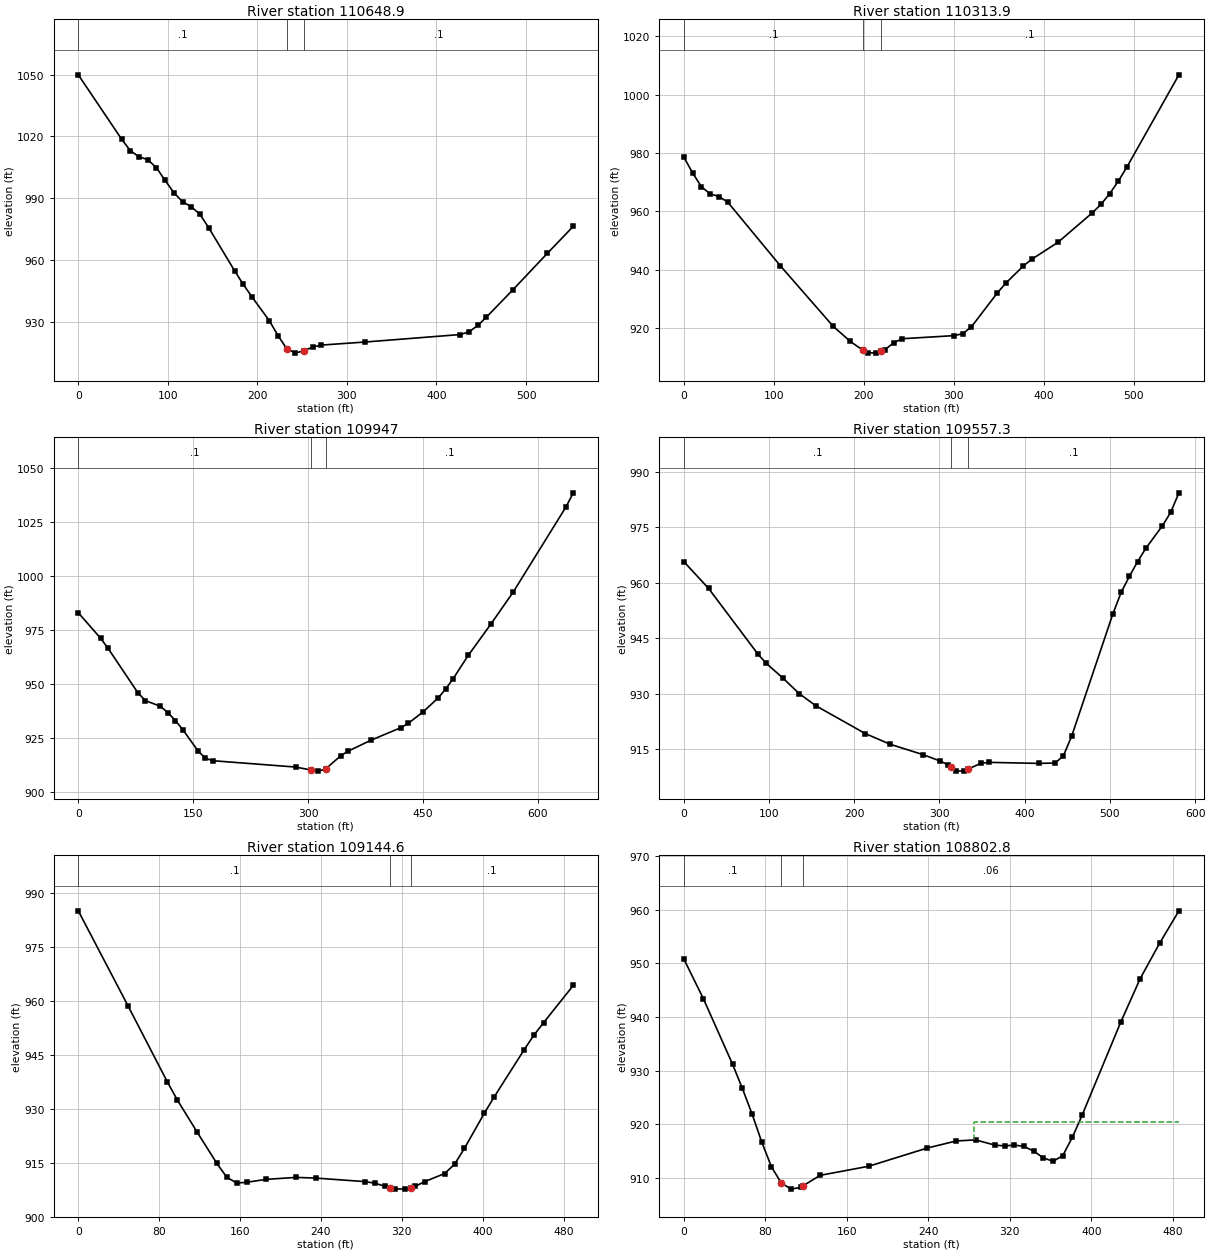
Type RM Length L Ch R = 1 ,110648.9,339.3,335,330.2
XS GIS Cut Line= 2
     1896430.665      495151.717     1896983.087      495171.032
#Sta/Elev= 30
       0 1049.91    48.5 1018.57    58.2    1013    67.9 1010.09    77.6 1008.67
    87.3 1004.76      97  998.58   106.7  992.65   116.4  988.25   126.1  985.84
   135.8  982.14   145.5  975.72   174.6  954.67   184.2  948.08     194  941.97
   213.4  930.39     223  923.21   232.7  916.87   242.4  914.68   252.1   915.9
   261.8   917.6   271.5  918.59     320  920.07   426.7  923.72   436.4  925.04
   446.1  928.13   455.8   932.2   484.9  945.26   523.7  963.12   552.8  976.32
#Mann= 3 , 0 , 0
       0      .1       0   232.7    .045       0   252.1      .1       0
Bank Sta=232.7,252.1
XS Rating Curve= 0 ,0
Exp/Cntr=0.3,0.1

Type RM Length L Ch R = 1 ,110313.9,348.8,366.9,383.9
XS GIS Cut Line= 3
     1896520.391      495500.303     1896676.641      495496.831
     1897065.238      495431.289
#Sta/Elev= 30
       0  978.53     9.8   973.1    19.5  968.39    29.3  965.93    39.1  965.04
    48.8   963.1   107.4  941.25   165.9  920.59   185.1  915.36   198.8  912.42
   204.4  911.54     214  911.36   218.8  911.95   223.6  912.54   233.2   914.9
   242.8   916.3   300.5  917.36   310.1  918.04   319.7  920.37   348.5     932
   358.1  935.39   377.4  941.23     387  943.58   415.8  949.31   454.3   959.5
   463.9  962.41   473.5  966.04   483.1  970.34   492.7  975.21   550.4 1006.76
#Mann= 3 , 0 , 0
       0      .1       0   198.8    .045       0   218.8      .1       0
Bank Sta=198.8,218.8
XS Rating Curve= 0 ,0
Exp/Cntr=0.3,0.1

Type RM Length L Ch R = 1 ,109947  ,392.4,389.7,385.1
XS GIS Cut Line= 3
     1896464.394      495662.339     1896562.822      495704.724
     1897015.244      495998.333
#Sta/Elev= 30
       0  983.04    29.2  971.19      39  966.49    77.9  945.94    87.7  942.36
   107.2  939.71     117   936.8   126.8  933.12   136.6  928.86   156.2  919.16
     166  915.63   175.8  914.53   283.7   911.6   303.3  910.27   313.1  909.71
   322.9  910.66   342.5  916.76   352.3  918.94   381.7  923.94     421  929.78
   430.8  931.79   450.4  937.16     470  943.61   479.8   947.7   489.6  952.53
   509.2  963.25   538.6  977.66   568.1  992.66   636.7 1031.88   646.5 1038.54
#Mann= 3 , 0 , 0
       0      .1       0   303.3    .045       0   322.9      .1       0
Bank Sta=303.3,322.9
XS Rating Curve= 0 ,0
Exp/Cntr=0.3,0.1

Type RM Length L Ch R = 1 ,109557.3,421.3,412.7,402.2
XS GIS Cut Line= 2
     1896303.067      495986.249     1896834.751      496220.624
#Sta/Elev= 30
       0  965.68      29  958.44    87.2  940.58    96.8  938.15   116.2  934.19
   135.6  929.93     155  926.68     213  919.16   242.1  916.28   280.8  913.46
   300.2   911.8   309.9  910.74   313.4  910.13   319.6  909.06   329.3  909.01
   333.4  909.52   348.6  911.14   358.3  911.38   416.4   911.1   435.8   911.2
   445.5  913.19   455.2   918.5   503.6  951.61   513.3  957.43     523  961.75
   532.6  965.72   542.3  969.33   561.7   975.4   571.4  979.04     581   984.3
#Mann= 3 , 0 , 0
       0      .1       0   313.4    .045       0   333.4      .1       0
Bank Sta=313.4,333.4
XS Rating Curve= 0 ,0
Exp/Cntr=0.3,0.1

Type RM Length L Ch R = 1 ,109144.6,344.2,341.8,338.3
XS GIS Cut Line= 2
     1896249.074      496498.879     1896738.657      496498.358
#Sta/Elev= 30
       0  985.11      49  958.78    88.1  937.52    97.9  932.54   117.5   923.6
   137.1  914.85   146.9  911.02   156.7  909.42   166.5  909.62     186  910.44
   215.4  910.98     235  910.79     284   909.8   293.8  909.34   303.5  908.48
   308.6  908.14   313.3  907.82   323.1  907.72   328.6  908.14   332.9  908.46
   342.7  909.81   362.3  912.06   372.1  914.61   381.9  919.05   401.5  928.78
   411.2   933.3   440.6  946.32   450.4  950.45   460.2  954.02   489.6  964.37
#Mann= 3 , 0 , 0
       0      .1       0   308.6    .045       0   328.6      .1       0
Bank Sta=308.6,328.6
XS Rating Curve= 0 ,0
Exp/Cntr=0.3,0.1

Type RM Length L Ch R = 1 ,108802.8,144.5,141.6,139.2
XS GIS Cut Line= 3
     1896405.772      496843.747     1896661.733      496812.313
     1896805.056      496634.979
#Sta/Elev= 30
       0  950.82    19.1  943.44    47.8   931.2    57.3  926.74    66.9  921.94
    76.4  916.71      86  912.04    95.5  909.08   105.1   907.9   114.6  908.22
   116.6  908.47   133.7  910.47   181.5  912.17   238.8  915.56   267.4  916.89
   286.4  917.08   305.4  916.11   314.9  915.96   324.4  916.12   333.9  915.87
   343.4  914.98   352.9  913.73   362.4  913.09   371.9  914.15   381.4   917.6
   390.9   921.7   428.9  939.09   447.9  947.17   466.9  953.75   485.9  959.82
#Mann= 3 , 0 , 0
       0      .1       0    95.5    .045       0   116.6     .06       0
#XS Ineff= 2 , 0
                          284.35           920.4
Permanent Ineff=
       F       F
Bank Sta=95.5,116.6
XS Rating Curve= 0 ,0
Exp/Cntr=0.3,0.1

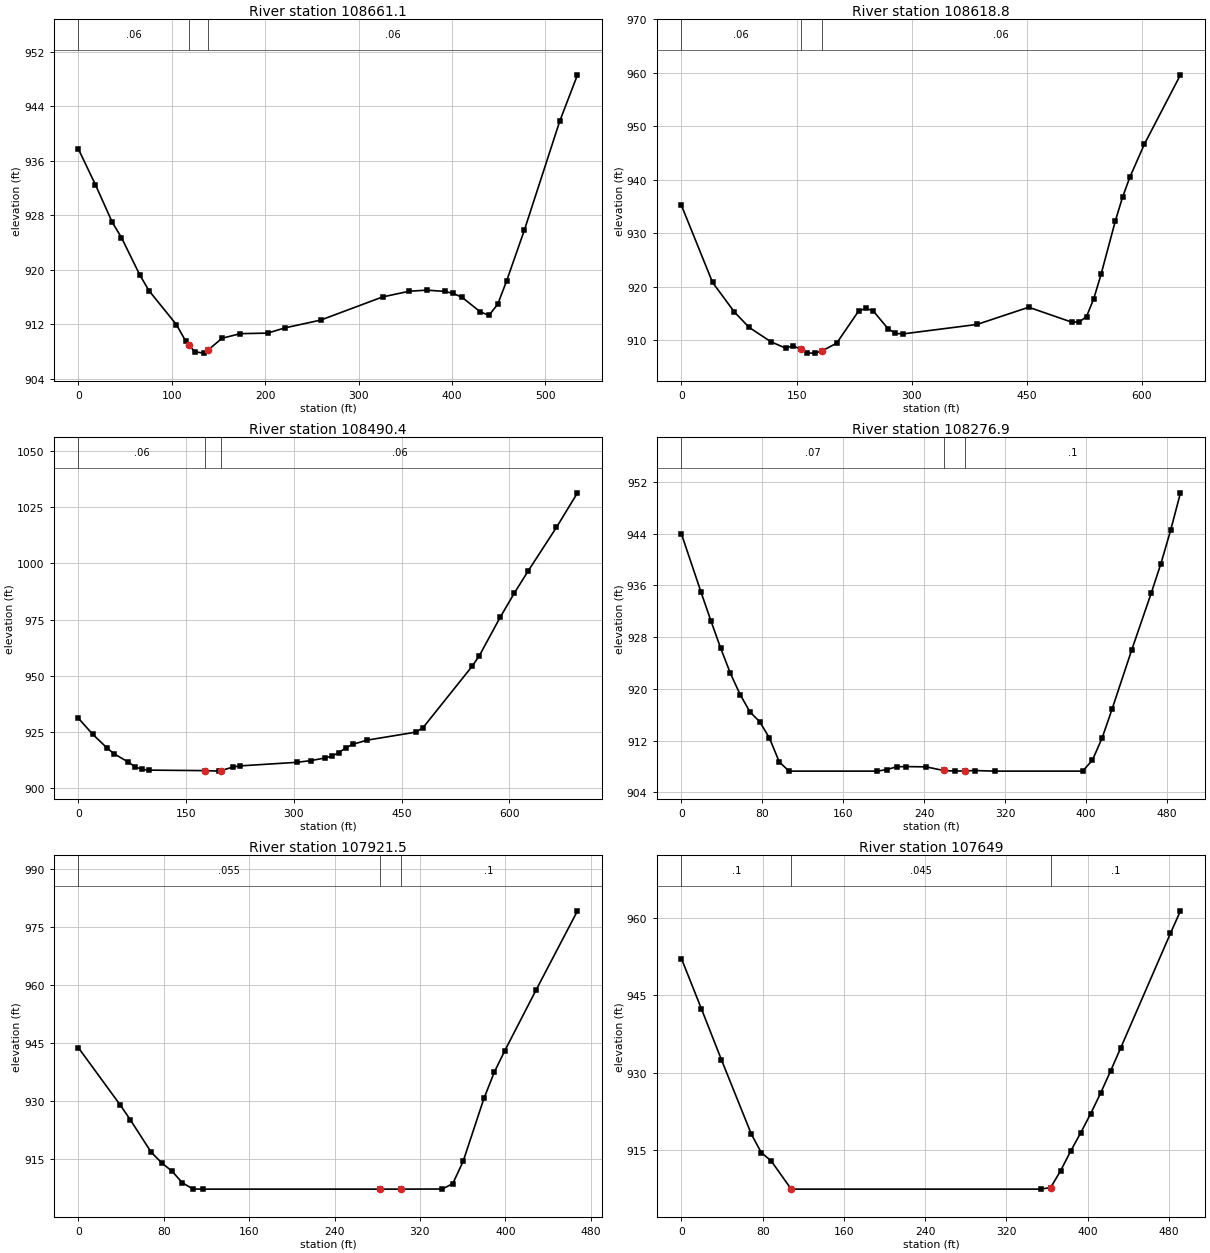
Type RM Length L Ch R = 1 ,108661.1,42.3,42.3,42
XS GIS Cut Line= 5
     1896423.436      496971.277     1896454.686      496989.507
     1896607.067      496952.314     1896700.052      496832.642
     1896820.137      496685.687
#Sta/Elev= 30
       0  937.72    18.1  932.52    36.2  926.98      46  924.75    65.6  919.27
    75.4  916.96   104.8  911.97   114.6  909.59   118.7  908.91   124.4  907.97
   134.2  907.77   138.7  908.22   153.8  909.96   173.4  910.63   202.5  910.71
   221.4  911.49   259.3  912.62   325.6  916.02   354.1  916.86     373  917.02
     392  916.84   401.5  916.53     411  915.95     430  913.86   439.5  913.31
     449  914.96   458.4  918.34   477.4   925.8   515.4  941.85   534.4  948.65
#Mann= 3 , 0 , 0
       0     .06       0   118.7    .045       0   138.7     .06       0
Bank Sta=118.7,138.7
XS Rating Curve= 0 ,0
Exp/Cntr=0.3,0.1

Type RM Length L Ch R = 1 ,108618.8,110.6,128.4,146.1
XS GIS Cut Line= 5
     1896390.449      497018.152     1896424.554      497039.992
      1896627.59      496989.378     1896749.043      496839.029
     1896877.728      496676.794
#Sta/Elev= 30
       0  935.22    40.5  920.82      69  915.28    88.1  912.42   116.6  909.72
   135.6  908.54   145.1  908.94   155.2  908.37   164.2  907.62   173.7   907.6
   183.2  908.02   202.2  909.46   230.7  915.45   240.2  915.97   249.8   915.5
   269.1  912.17   278.7   911.3   288.4  911.19     385  912.96   452.4  916.18
   508.9  913.37   518.3  913.44   527.7  914.43   537.2   917.8   546.6   922.3
   565.4  932.39   574.8  936.82   584.2   940.5     603  946.64   650.1  959.63
#Mann= 3 , 0 , 0
       0     .06       0   155.2    .045       0   183.2     .06       0
Bank Sta=155.2,183.2
XS Rating Curve= 0 ,0
Exp/Cntr=0.3,0.1

Type RM Length L Ch R = 1 ,108490.4,200.5,213.5,226.3
XS GIS Cut Line= 3
     1896374.824      497039.854     1896695.137      497229.958
     1897011.109      497295.062
#Sta/Elev= 30
       0  931.04    19.6  924.01    39.2  918.03      49  915.38    68.6  911.72
    78.4  909.57    88.2  908.31      98     908   176.4  907.77     196  907.55
   198.9   907.8   215.6  909.43   225.4  909.89   303.9  911.46   323.5  912.22
   343.1  913.39   352.9  914.22   362.7   915.8   372.5  917.94   382.2  919.48
   401.8  921.33   470.2  924.91     480  926.92   548.4  954.24   558.2  958.82
   587.6  976.13   607.1  986.77   626.7  996.79   665.8 1016.03   695.1  1031.4
#Mann= 3 , 0 , 0
       0     .06       0   176.4    .045       0   198.9     .06       0
Bank Sta=176.4,198.9
XS Rating Curve= 0 ,0
Exp/Cntr=0.3,0.1

Type RM Length L Ch R = 1 ,108276.9,343.6,355.4,367
XS GIS Cut Line= 2
     1896281.798      497055.197     1896501.654      497496.715
#Sta/Elev= 30
       0  943.96    19.3  934.99      29  930.58    38.7  926.34    48.4   922.4
      58  919.14    67.7  916.45    77.4  914.93      87   912.4    96.7  908.71
   106.4   907.3   193.4   907.3   203.1  907.54   212.8  907.98   222.4     908
   241.8  907.96     259   907.4   270.8   907.3   280.5  907.34   290.1  907.39
   309.5   907.3   396.5   907.3   406.2     909   415.9  912.48   425.5  916.84
   444.9  925.98   464.2  934.77   473.9  939.39   483.6   944.6   493.2  950.32
#Mann= 3 , 0 , 0
       0     .07       0     259    .045       0   280.5      .1       0
Bank Sta=259,280.5
XS Rating Curve= 0 ,0
Exp/Cntr=0.3,0.1

Type RM Length L Ch R = 1 ,107921.5,275.6,272.5,269.4
XS GIS Cut Line= 2
     1896136.148      497083.105     1896111.158      497550.145
#Sta/Elev= 19
       0  943.79      39  929.08    48.7  925.15    68.2  916.81      78  914.08
    87.7  911.92    97.4  908.93   107.2  907.34   116.9   907.3   282.6   907.3
   302.1   907.3     341  907.33   350.8  908.72   360.5  914.47     380  930.71
   389.8  937.56   399.5  943.02   428.7  958.64   467.7  979.18
#Mann= 3 , 0 , 0
       0    .055       0   282.6    .045       0   302.1      .1       0
Bank Sta=282.6,302.1
XS Rating Curve= 0 ,0
Exp/Cntr=0.3,0.1

Type RM Length L Ch R = 1 ,107649  ,150.2,145.6,141
XS GIS Cut Line= 2
     1895820.702       497057.51     1895862.369      497547.094
#Sta/Elev= 18
       0  952.17    19.6  942.43    39.3  932.52    68.8  918.01    78.6  914.41
    88.4  912.78   108.1   907.3   353.8   907.3   363.6  907.61   373.4  910.89
   383.3   914.7   393.1  918.24   402.9  921.96   412.7  925.96   422.6  930.31
   432.4  934.72   481.5  957.08   491.4  961.48
#Mann= 3 , 0 , 0
       0      .1       0   108.1    .045       0   363.6      .1       0
Bank Sta=108.1,363.6
XS Rating Curve= 0 ,0
Exp/Cntr=0.3,0.1

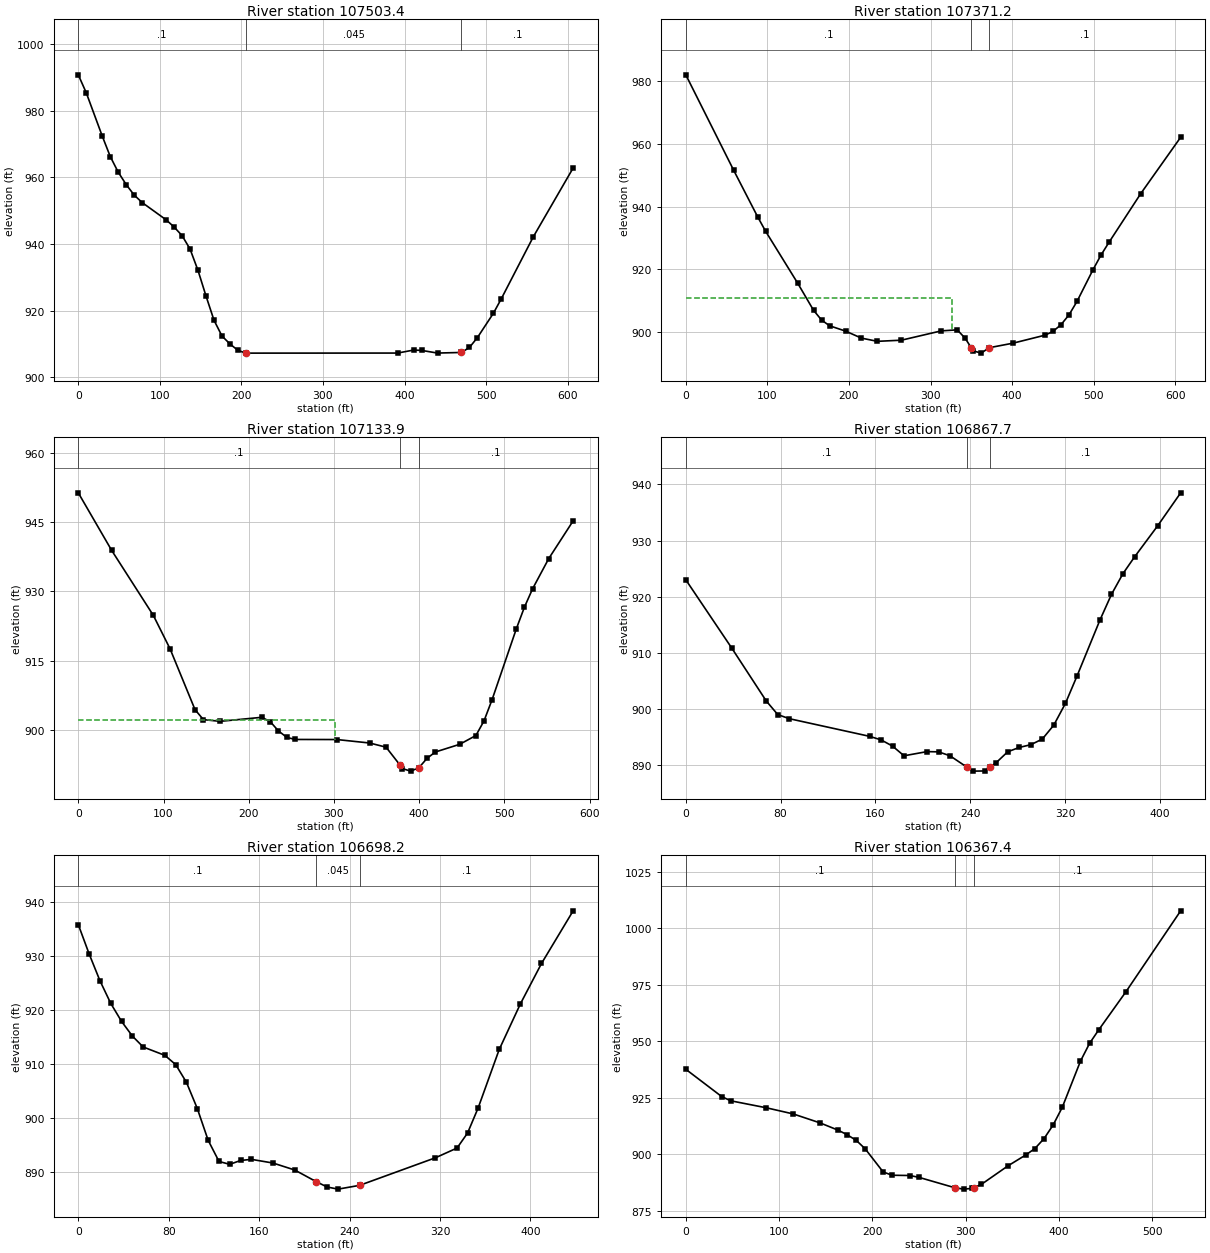
Type RM Length L Ch R = 1 ,107503.4,133.1,132.2,130.7
XS GIS Cut Line= 3
      1895590.57      497020.556     1895733.972      497498.665
      1895776.53      497597.448
#Sta/Elev= 30
       0  990.71     9.8  985.31    29.4  972.34    39.2  966.22    48.9  961.56
    58.7  957.83    68.5  954.68    78.3  952.43   107.7  947.25   117.4  945.12
   127.2  942.53     137  938.51   146.8  932.07   156.6  924.41   166.4  917.15
   176.2  912.42     186  910.04   195.8  908.12   205.5   907.3   391.5  907.32
   411.1  908.22   420.8  908.12   440.4  907.32   469.8   907.5   479.6  909.01
   489.4  911.98   508.9  919.24   518.7  923.63   557.8  942.14   606.7  962.79
#Mann= 3 , 0 , 0
       0      .1       0   205.5    .045       0   469.8      .1       0
Bank Sta=205.5,469.8
XS Rating Curve= 0 ,0
Exp/Cntr=0.3,0.1

Type RM Length L Ch R = 1 ,107371.2,258.2,237.3,215.9
XS GIS Cut Line= 3
     1895462.109      497091.952     1895625.664      497563.547
     1895672.374      497660.436
#Sta/Elev= 30
       0  981.99    58.7  951.58    88.1  936.75    97.9  932.13     137  915.69
   156.6  906.99   166.4  903.89   176.2  902.06   195.8  900.36   215.3  898.12
   234.9   897.1   264.3  897.46   313.2  900.43   332.8  900.75   342.6  898.04
     350  895.02   352.3  894.08   362.1  893.34   371.9  895.06   401.3  896.52
   440.4  899.06   450.2  900.27     460   902.4   469.8  905.53   479.6  909.81
   499.2   919.9   508.9  924.53   518.7  928.59   557.8  944.17   606.7   962.1
#Mann= 3 , 0 , 0
       0      .1       0     350    .045       0   371.9      .1       0
#XS Ineff= 2 , 0
           326.7   910.8
Permanent Ineff=
       F       F
Bank Sta=350,371.9
XS Rating Curve= 0 ,0
Exp/Cntr=0.3,0.1

Type RM Length L Ch R = 1 ,107133.9,254.9,266.2,276.7
XS GIS Cut Line= 4
     1895037.455      497538.237     1895339.538      497566.883
      1895468.01      497606.813     1895573.913      497702.299
#Sta/Elev= 30
       0  951.32    39.2  938.86    88.1   924.8   107.7  917.57     137  904.41
   146.8  902.27   166.4   901.9   215.3  902.77   225.1  901.85   234.9  899.82
   244.7  898.42   254.5  897.98   303.4  897.96   341.9  897.21   361.1  896.31
   377.7  892.39   380.3  891.68   389.9  891.13   399.5  891.84   409.1  893.88
   418.8  895.26   447.5  896.93   466.5  898.83     476  901.99   485.5  906.59
     514  921.94   523.5  926.62     533  930.56     552  937.11   580.6  945.26
#Mann= 3 , 0 , 0
       0      .1       0   377.7    .045       0   399.5      .1       0
#XS Ineff= 2 , 0
          300.85  902.13
Permanent Ineff=
       F       F
Bank Sta=377.7,399.5
XS Rating Curve= 0 ,0
Exp/Cntr=0.3,0.1

Type RM Length L Ch R = 1 ,106867.7,186,169.6,152.6
XS GIS Cut Line= 3
     1895101.995      497673.435     1895279.078      497792.358
      1895423.61       497936.89
#Sta/Elev= 30
       0  923.01    38.8  910.86    67.9  901.46    77.6  899.04    87.3  898.31
   155.1  895.17   164.8  894.54   174.5  893.43   184.2  891.71   203.6  892.45
   213.3  892.41     223  891.71   237.1  889.71   242.5  888.98   252.2  889.01
   257.1  889.75     262  890.49   271.7  892.42   281.4  893.19   291.2  893.68
   300.9  894.68   310.6  897.16   320.4  901.02   330.1  905.84   349.6  915.87
   359.3  920.42     369  924.11   378.8  927.09   398.2  932.59   417.7  938.48
#Mann= 3 , 0 , 0
       0      .1       0   237.1    .045       0   257.1      .1       0
Bank Sta=237.1,257.1
XS Rating Curve= 0 ,0
Exp/Cntr=0.3,0.1

Type RM Length L Ch R = 1 ,106698.2,331.6,330.8,329.5
XS GIS Cut Line= 3
     1894979.462      497939.082     1895314.144      497955.623
     1895414.415       497977.97
#Sta/Elev= 30
       0  935.81     9.6  930.38    19.2   925.4    28.7  921.23    38.3  917.88
    47.9  915.16    57.4  913.15    76.6   911.6    86.2  909.88    95.7   906.6
   105.3  901.75   114.9  895.87   124.5  891.95     134  891.42   143.6  892.14
   153.2  892.34   172.3  891.66   191.5  890.37   210.6   888.2   220.2  887.22
   229.8  886.83   248.9  887.53   315.9  892.63   335.1  894.44   344.4  897.22
   353.8  901.89   372.4  912.69   391.1  921.12   409.8  928.61   437.8  938.36
#Mann= 3 , 0 , 0
       0      .1       0   210.6    .045       0   248.9      .1       0
Bank Sta=210.6,248.9
XS Rating Curve= 0 ,0
Exp/Cntr=0.3,0.1

Type RM Length L Ch R = 1 ,106367.4,248.6,252.3,254.7
XS GIS Cut Line= 5
     1894963.348       498284.32     1895145.192      498272.419
     1895145.717      498272.393     1895337.208      498273.768
     1895492.862      498287.793
#Sta/Elev= 30
       0  937.57    38.4  925.51      48  923.63    86.3  920.52   115.1   917.8
   143.9  913.83     163  910.65   172.6  908.67   182.8  906.06   192.3  902.34
   211.5  892.12   221.1  890.64   240.2  890.52   249.8  889.72   288.1  885.14
   297.7  884.49   307.2  884.83   308.9  885.14   316.8  886.58   345.5  894.84
   364.7  899.69   374.2  902.46     384  906.85   393.8  912.91   403.6  920.75
   423.1   941.2   432.9   949.1   442.6     955   471.9  971.96   530.5 1007.76
#Mann= 3 , 0 , 0
       0      .1       0   288.1    .045       0   308.9      .1       0
Bank Sta=288.1,308.9
XS Rating Curve= 0 ,0
Exp/Cntr=0.3,0.1

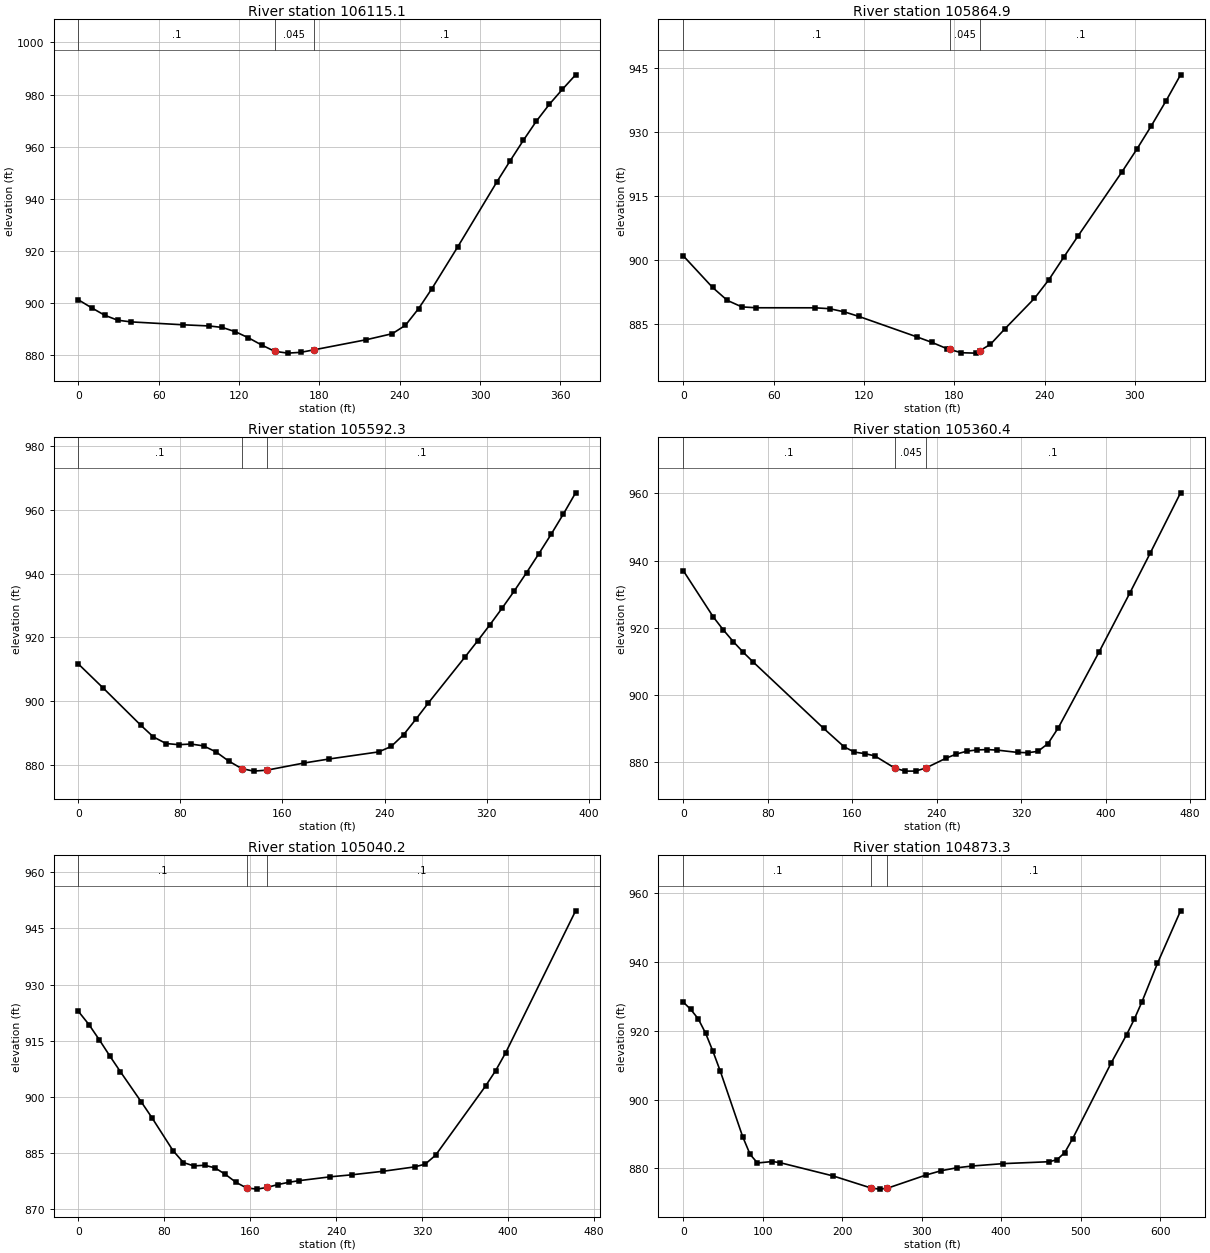
Type RM Length L Ch R = 1 ,106115.1,244.3,250.2,255.8
XS GIS Cut Line= 2
      1895041.69      498490.701     1895409.529      498541.699
#Sta/Elev= 28
       0  901.27     9.8  898.23    19.6  895.36    29.3  893.45    39.1  892.81
    78.2  891.69    97.7  891.24   107.5  890.67   117.3  889.02     127   886.7
   136.8  883.96   146.6  881.52   156.4  880.82   166.1  881.12   175.9  882.08
     215  885.96   234.5  888.28   244.3  891.51   254.1  897.89   263.9  905.43
   283.4  921.62   312.7   946.6   322.5   954.6   332.3  962.39     342  969.74
   351.8  976.27   361.6  982.05   371.4  987.57
#Mann= 3 , 0 , 0
       0      .1       0   146.6    .045       0   175.9      .1       0
Bank Sta=146.6,175.9
XS Rating Curve= 0 ,0
Exp/Cntr=0.3,0.1

Type RM Length L Ch R = 1 ,105864.9,274.6,272.5,270.4
XS GIS Cut Line= 2
     1895006.214      498670.936     1895310.752      498799.201
#Sta/Elev= 27
       0  901.04    19.4  893.67    29.2  890.64    38.9  889.11    48.6  888.91
    87.5   888.9    97.2  888.69   106.9  887.96   116.6  886.89   155.5  882.06
   165.2  880.81   174.9  879.38   177.1  879.16   184.7  878.39   194.4   878.3
   197.1  878.88   204.1  880.37   213.8  884.03   233.3   891.1     243  895.52
   252.7   900.7   262.4  905.76   291.6  920.76   301.3  925.97     311  931.48
   320.7  937.27   330.4  943.39
#Mann= 3 , 0 , 0
       0      .1       0   177.1    .045       0   197.1      .1       0
Bank Sta=177.1,197.1
XS Rating Curve= 0 ,0
Exp/Cntr=0.3,0.1

Type RM Length L Ch R = 1 ,105592.3,238.4,232,224.4
XS GIS Cut Line= 3
     1894938.913      498951.855     1895191.423      499031.699
     1895315.302      499048.383
#Sta/Elev= 30
       0  911.67    19.6  904.06      49  892.41    58.8  888.77    68.7   886.7
    78.5  886.34    88.3  886.53    98.1  885.96   107.9  884.06   117.7  881.23
   127.9  878.85   137.3  878.03   147.9  878.34   176.6  880.56   196.2  881.82
   235.4  884.07   245.2  885.77     255   889.5   264.8  894.44   274.4  899.46
   303.3  913.98   312.9  918.89   322.5  923.93   332.1  929.17   341.8  934.66
   351.4   940.4     361  946.33   370.6   952.4   380.2  958.77   389.8  965.43
#Mann= 3 , 0 , 0
       0      .1       0   127.9    .045       0   147.9      .1       0
Bank Sta=127.9,147.9
XS Rating Curve= 0 ,0
Exp/Cntr=0.3,0.1

Type RM Length L Ch R = 1 ,105360.4,317.1,320.2,322.3
XS GIS Cut Line= 3
     1894812.611      499175.727     1894921.552       499208.32
     1895278.775      499208.496
#Sta/Elev= 30
       0  936.95    28.4  923.16    37.9   919.3    47.4  915.79    56.9   912.6
    66.3   909.7     133  889.93   152.3  884.46     162  882.89   171.6  882.45
   181.3  881.77   200.6  878.06   210.3  877.22   219.9  877.23   229.6  878.14
   248.9  881.09   258.5   882.3   268.2  883.14   277.8  883.53   287.5  883.64
   297.2  883.49   316.5   882.8   326.1  882.71   335.8  883.11   345.4  885.44
   355.1  890.13   393.7  912.72   422.7  930.22     442   942.1   470.9  960.18
#Mann= 3 , 0 , 0
       0      .1       0   200.6    .045       0   229.6      .1       0
Bank Sta=200.6,229.6
XS Rating Curve= 0 ,0
Exp/Cntr=0.3,0.1

Type RM Length L Ch R = 1 ,105040.2,165.8,166.8,167.9
XS GIS Cut Line= 4
     1894828.872      499493.414     1894945.192      499509.039
     1895158.733      499535.514     1895279.827      499487.337
#Sta/Elev= 30
       0  922.85     9.8  919.33    19.6   915.2    29.3  910.91    39.1  906.73
    58.7  898.59    68.5  894.42      88  885.67    97.8  882.44   107.6  881.55
   117.4  881.73   127.1  881.04   136.9  879.28   146.7  877.17   156.5  875.67
   166.3  875.35     176  875.83   185.8  876.58   195.6  877.16   205.4  877.61
   234.7  878.65   254.3  879.17   283.6  880.12     313  881.29   322.8  882.02
   332.5   884.4   379.1  902.92   388.4  906.99   397.7  911.75   462.9  949.72
#Mann= 3 , 0 , 0
       0      .1       0   156.5    .045       0     176      .1       0
Bank Sta=156.5,176
XS Rating Curve= 0 ,0
Exp/Cntr=0.3,0.1

Type RM Length L Ch R = 1 ,104873.3,235.7,251.5,265.8
XS GIS Cut Line= 4
     1894791.192       499555.77     1894880.602      499663.409
     1895120.185      499704.207     1895315.498       499560.11
#Sta/Elev= 30
       0   928.3     9.3  926.19    18.7  923.47      28  919.28    37.3  913.98
    46.6  908.18    74.6  889.25      84  884.06    93.3  881.56   111.9  881.98
   121.3  881.67   188.5  877.79   236.6  874.26   246.9  873.96   256.6  874.21
   305.2  878.05   324.6  879.32   344.1  880.16   363.5  880.68   402.4  881.37
   460.6  881.93   470.3  882.52     480   884.6   489.8  888.59   538.3   910.6
   557.7   918.8   567.4  923.32   577.1  928.39   596.6  939.57   625.7  954.85
#Mann= 3 , 0 , 0
       0      .1       0   236.6    .045       0   256.6      .1       0
Bank Sta=236.6,256.6
XS Rating Curve= 0 ,0
Exp/Cntr=0.3,0.1

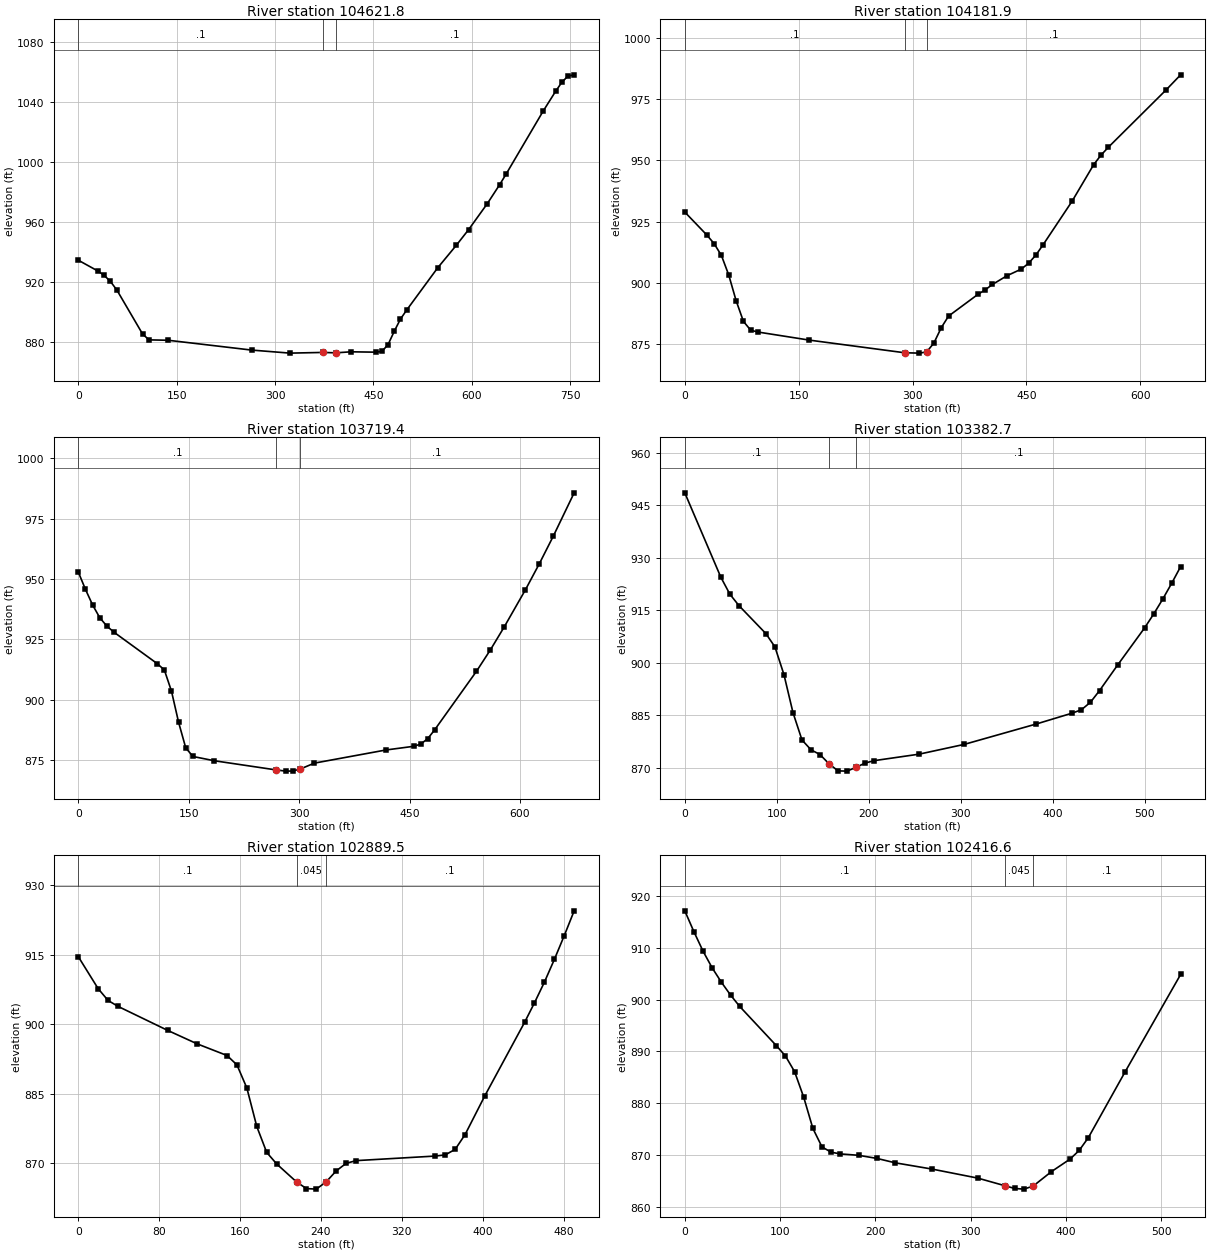
Type RM Length L Ch R = 1 ,104621.8,418,439.9,460.7
XS GIS Cut Line= 5
     1894753.267      499563.785     1894854.378      499860.451
     1894944.934       499954.34     1894981.375      500051.774
     1895131.253      500196.178
#Sta/Elev= 30
       0  934.49    29.4  927.42    39.2   924.5      49  920.35    58.8  914.62
    97.9  885.46   107.7  881.51   137.1  881.24   264.4  874.71   322.7  872.69
   372.7  873.15   392.7  872.89   415.9  873.57   453.3  873.33   462.8  873.82
   472.2  878.32   481.7  887.23   491.2  895.38   500.6  901.32   547.9  929.43
   576.3  944.42   595.2  954.93   623.6  972.16   642.5  984.82     652  991.62
   708.7 1033.68   727.6 1046.77   737.1 1052.81   746.6 1057.05     756 1057.83
#Mann= 3 , 0 , 0
       0      .1       0   372.7    .045       0   392.7      .1       0
Bank Sta=372.7,392.7
XS Rating Curve= 0 ,0
Exp/Cntr=0.3,0.1

Type RM Length L Ch R = 1 ,104181.9,433.8,462.4,491.4
XS GIS Cut Line= 3
     1894543.395      499633.096     1894470.478      500021.985
     1894559.888      500263.304
#Sta/Elev= 30
       0  928.87      29  919.48    38.6  915.96    48.2  911.14    57.9  903.09
    67.6   892.6    77.2  884.15    86.8  880.54    96.5  879.78   164.1  876.48
   289.5  871.31   308.8  871.16   318.5  871.63   328.1  875.32   337.8  881.59
   347.4  886.32     386  895.19   395.7  897.07   405.2  899.26   424.3  902.82
   443.3  905.56   452.8  907.94   462.4  911.28   471.9   915.5     510  933.28
   538.6  948.32   548.2  952.17   557.7  955.35     634  978.88     653  985.01
#Mann= 3 , 0 , 0
       0      .1       0   289.5    .045       0   318.5      .1       0
Bank Sta=289.5,318.5
XS Rating Curve= 0 ,0
Exp/Cntr=0.3,0.1

Type RM Length L Ch R = 1 ,103719.4,346.3,336.7,326.2
XS GIS Cut Line= 4
     1894445.575       499519.11     1894298.353      499646.332
     1894076.686      499670.776     1893861.409      499809.145
#Sta/Elev= 30
       0  952.84     9.7  945.69    19.5  939.19    29.2  933.94    38.9  930.46
    48.6  927.94     107  915.01   116.8  912.39   126.5  903.61   136.2  890.69
   145.9  880.11   155.7  876.55   184.8  874.78   268.8870.9803   281.8  870.49
   291.3  870.53   301.2  871.33   320.6   873.8   417.6  879.23   455.5  880.76
     465  881.67   474.5   883.9   483.9  887.53   540.8   911.8   559.8  920.71
   578.7  930.27   607.2  945.48   626.1  956.27   645.1  967.69   673.5  985.66
#Mann= 3 , 0 , 0
       0      .1       0   268.8    .045       0   301.2      .1       0
Bank Sta=268.8,301.2
XS Rating Curve= 0 ,0
Exp/Cntr=0.3,0.1

Type RM Length L Ch R = 1 ,103382.7,495.7,493.3,490.1
XS GIS Cut Line= 2
     1894271.344      499250.631     1893814.023      499536.076
#Sta/Elev= 30
       0  948.57    39.2  924.44      49  919.61    58.8  916.36    88.2  908.33
      98  904.54   107.8  896.63   117.6  885.79   127.4  877.95   137.2  875.14
     147  873.77   156.8  871.14   166.6  869.11   176.4  869.04   186.2  870.13
     196  871.34   205.8  872.03   254.8  873.89   303.8  876.68   382.3  882.52
   421.5  885.64   431.3  886.59   441.1  888.73   450.9  892.04   470.5  899.32
   499.9  909.96   509.7  913.89   519.5  918.13   529.3  922.68   539.1  927.48
#Mann= 3 , 0 , 0
       0      .1       0   156.8    .045       0   186.2      .1       0
Bank Sta=156.8,186.2
XS Rating Curve= 0 ,0
Exp/Cntr=0.3,0.1

Type RM Length L Ch R = 1 ,102889.5,484.7,472.9,460.8
XS GIS Cut Line= 2
     1893921.532      498915.576     1893555.559      499241.964
#Sta/Elev= 30
       0  914.59    19.6   907.7    29.4  905.16    39.2  903.88    88.3   898.7
   117.7  895.77   147.1  893.27   156.9  891.24   166.7  886.24   176.5  877.95
   186.3  872.36   196.2  869.86   215.8  865.99   225.6  864.55   235.4  864.43
   245.2  866.02     255  868.35   264.8  869.99   274.6  870.58   353.1  871.57
   362.9  871.82   372.7  873.01   382.5   876.2   402.1  884.59   441.3   900.4
   451.1  904.62     461  909.12   470.8     914   480.6  919.14   490.4   924.5
#Mann= 3 , 0 , 0
       0      .1       0   215.8    .045       0   245.2      .1       0
Bank Sta=215.8,245.2
XS Rating Curve= 0 ,0
Exp/Cntr=0.3,0.1

Type RM Length L Ch R = 1 ,102416.6,505.1,488.3,470.7
XS GIS Cut Line= 3
     1893497.052      498565.749     1893352.788      498803.854
     1893267.886      499030.333
#Sta/Elev= 30
       0  917.15     9.6   913.1    19.2  909.34    28.8  906.11    38.4  903.36
      48  900.89    57.6  898.69      96  891.13   105.6  889.12   115.2   886.1
   124.8  881.15   134.4  875.13     144  871.55   153.6  870.54   163.2  870.21
   182.4  869.94   201.6  869.34   220.8  868.49   259.2  867.29   307.4  865.54
   336.4  864.04   346.1  863.54   355.8  863.41   365.5  863.99   384.8   866.8
   404.2   869.2   413.8  870.87   423.5  873.36   462.2  886.11   520.3  904.86
#Mann= 3 , 0 , 0
       0      .1       0   336.4    .045       0   365.5      .1       0
Bank Sta=336.4,365.5
XS Rating Curve= 0 ,0
Exp/Cntr=0.3,0.1

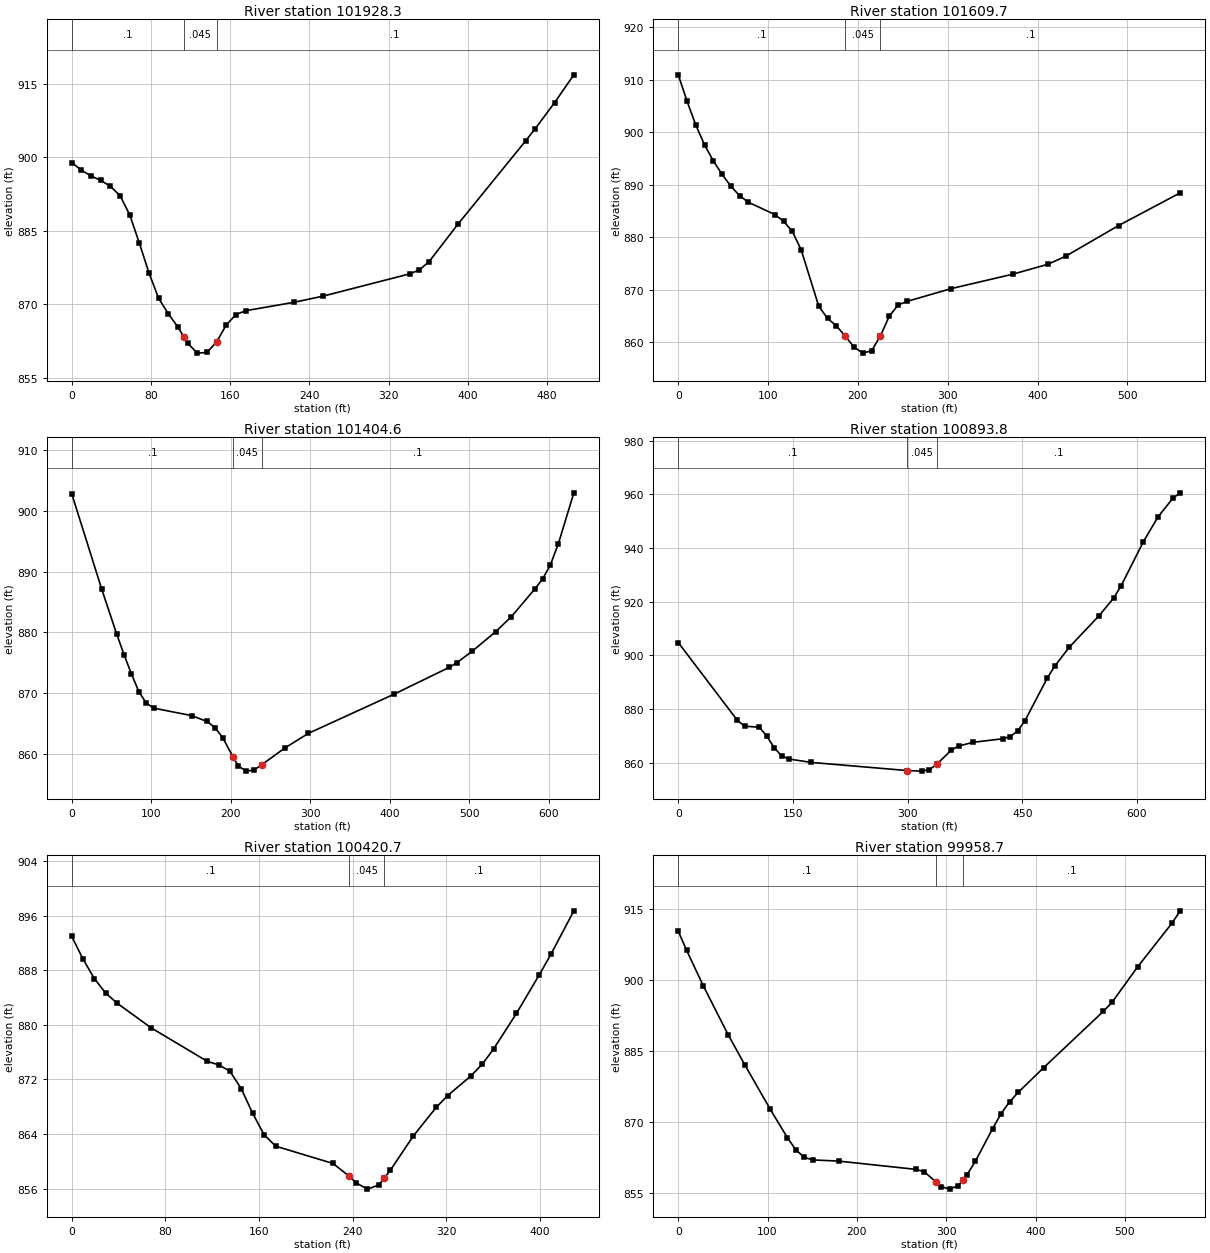
Type RM Length L Ch R = 1 ,101928.3,317.8,318.6,319.3
XS GIS Cut Line= 2
     1892858.382      498635.173     1893055.489       499102.32
#Sta/Elev= 30
       0  898.94     9.8  897.35    19.5  896.21    29.2  895.29      39  894.09
    48.8  892.17    58.5  888.28    68.2  882.52      78  876.38    87.8  871.19
    97.5  868.08   107.3  865.33   113.2 863.335     117  862.05   126.8  860.04
   136.5  860.18   146.3  862.35     156  865.79   165.8  867.91   175.5  868.69
   224.3  870.41   253.5  871.66   341.3  876.22     351  877.02   360.8  878.71
     390  886.37   458.3  903.36     468  905.85   487.5  911.15     507  916.84
#Mann= 3 , 0 , 0
       0      .1       0   113.2    .045       0   146.3      .1       0
Bank Sta=113.2,146.3
XS Rating Curve= 0 ,0
Exp/Cntr=0.3,0.1

Type RM Length L Ch R = 1 ,101609.7,207.7,205.1,201.8
XS GIS Cut Line= 4
     1892577.132      498675.798     1892578.834      498783.136
     1892638.382      498938.923     1892750.049      499200.798
#Sta/Elev= 30
       0  910.89     9.8  905.88    19.5  901.34    29.3  897.55      39  894.53
    48.8  891.95    58.6  889.69    68.3  887.88    78.1  886.64   107.4  884.31
   117.2  883.04     127  881.08   136.8   877.6   156.4  866.85   166.2  864.53
     176  863.12   185.8  861.18   195.6  859.08   205.5  857.93   215.3  858.39
   225.1  861.23   234.9  864.97   244.7  867.08   254.5  867.77   303.6   870.2
   372.3  872.95   411.6  874.85   431.2  876.37   490.1  882.21   558.8  888.44
#Mann= 3 , 0 , 0
       0      .1       0   185.8    .045       0   225.1      .1       0
Bank Sta=185.8,225.1
XS Rating Curve= 0 ,0
Exp/Cntr=0.3,0.1

Type RM Length L Ch R = 1 ,101404.6,477.5,510.8,543.3
XS GIS Cut Line= 4
     1892392.757      498691.076     1892386.681      498831.701
     1892494.858      499029.742     1892572.445      499283.089
#Sta/Elev= 30
       0  902.75    37.5  887.17    56.3   879.8    65.7  876.36    75.1  873.15
    84.4  870.27    93.8  868.37   103.2  867.56   150.6  866.34   170.2  865.37
     180  864.38   189.8  862.71   202.8859.5515   209.4  858.09   219.2  857.22
   229.1  857.39   238.9  858.27   268.3  861.05   297.7  863.43   405.7  869.88
   474.4  874.24   484.2  875.02   503.8  876.93   533.2  880.13   552.9  882.59
   582.3  887.12   592.1  888.77   601.9  891.09   611.8  894.52   631.4  902.92
#Mann= 3 , 0 , 0
       0      .1       0   202.8    .045       0   238.9      .1       0
Bank Sta=202.8,238.9
XS Rating Curve= 0 ,0
Exp/Cntr=0.3,0.1

Type RM Length L Ch R = 1 ,100893.8,504.7,473.1,439.8
XS GIS Cut Line= 4
     1892112.337      498641.349       1892088.9      498891.349
     1891942.198      499000.724     1891977.789      499220.342
#Sta/Elev= 30
       0  904.82    77.3  875.83    86.9  873.65   106.2  873.25   115.9  869.89
   125.6  865.62   135.2  862.56   144.9  861.41   173.8  860.15   299.2  857.12
   318.5   856.9   328.1   857.4   337.8  859.38     357   864.7   366.7  866.25
   385.9  867.65   424.4  868.96   434.1  869.76   443.8  871.86   453.4  875.67
   482.4  891.46   492.1   895.9   511.5  903.11   550.2  914.76   569.5  921.41
   579.2  925.97   608.2  942.32   627.6  951.71   646.9   958.6   656.6   960.6
#Mann= 3 , 0 , 0
       0      .1       0   299.2    .045       0   337.8      .1       0
Bank Sta=299.2,337.8
XS Rating Curve= 0 ,0
Exp/Cntr=0.3,0.1

Type RM Length L Ch R = 1 ,100420.7,432.7,462.1,490.6
XS GIS Cut Line= 3
     1891621.765      498743.182     1891657.911      498883.356
     1891790.133      499135.022
#Sta/Elev= 30
       0  892.96     9.6  889.65    19.3  886.78      29  884.66    38.6   883.2
    67.6  879.59   115.8  874.65   125.5  874.14   135.1  873.22   144.8  870.65
   154.6  867.02   164.4  863.88   174.2  862.22   223.2  859.68   237.2857.7971
   242.8  856.86   252.6  855.92   262.4  856.53   267.2857.5831   272.2  858.68
   291.8  863.71   311.4   867.9   321.2  869.64   340.8  872.48   350.6   874.2
   360.4  876.46     380  881.69   399.6  887.38   409.4  890.34     429  896.72
#Mann= 3 , 0 , 0
       0      .1       0   237.2    .045       0   267.2      .1       0
Bank Sta=237.2,267.2
XS Rating Curve= 0 ,0
Exp/Cntr=0.3,0.1

Type RM Length L Ch R = 1 ,99958.7 ,411.7,396.7,382
XS GIS Cut Line= 4
     1891505.793       498708.46     1891499.179      498792.099
     1891280.119      499006.029     1891220.675      499167.279
#Sta/Elev= 30
       0  910.36     9.3  906.35      28  898.84    55.9  888.48    74.6   882.1
     103  872.73   122.2  866.74   131.7  864.14   141.3  862.56   150.9  862.04
   179.6  861.79   265.7  860.05   275.3  859.55   288.7857.3478   294.4  856.38
     304  855.87   313.5  856.62   318.7857.8279   323.1  858.85   332.7  861.79
   351.8  868.62   361.4  871.82     371  874.34   380.5   876.3   409.2  881.56
     476  893.45   485.6  895.34   514.2  902.82   552.4  911.99     562  914.66
#Mann= 3 , 0 , 0
       0      .1       0   288.7    .045       0   318.7      .1       0
Bank Sta=288.7,318.7
XS Rating Curve= 0 ,0
Exp/Cntr=0.3,0.1