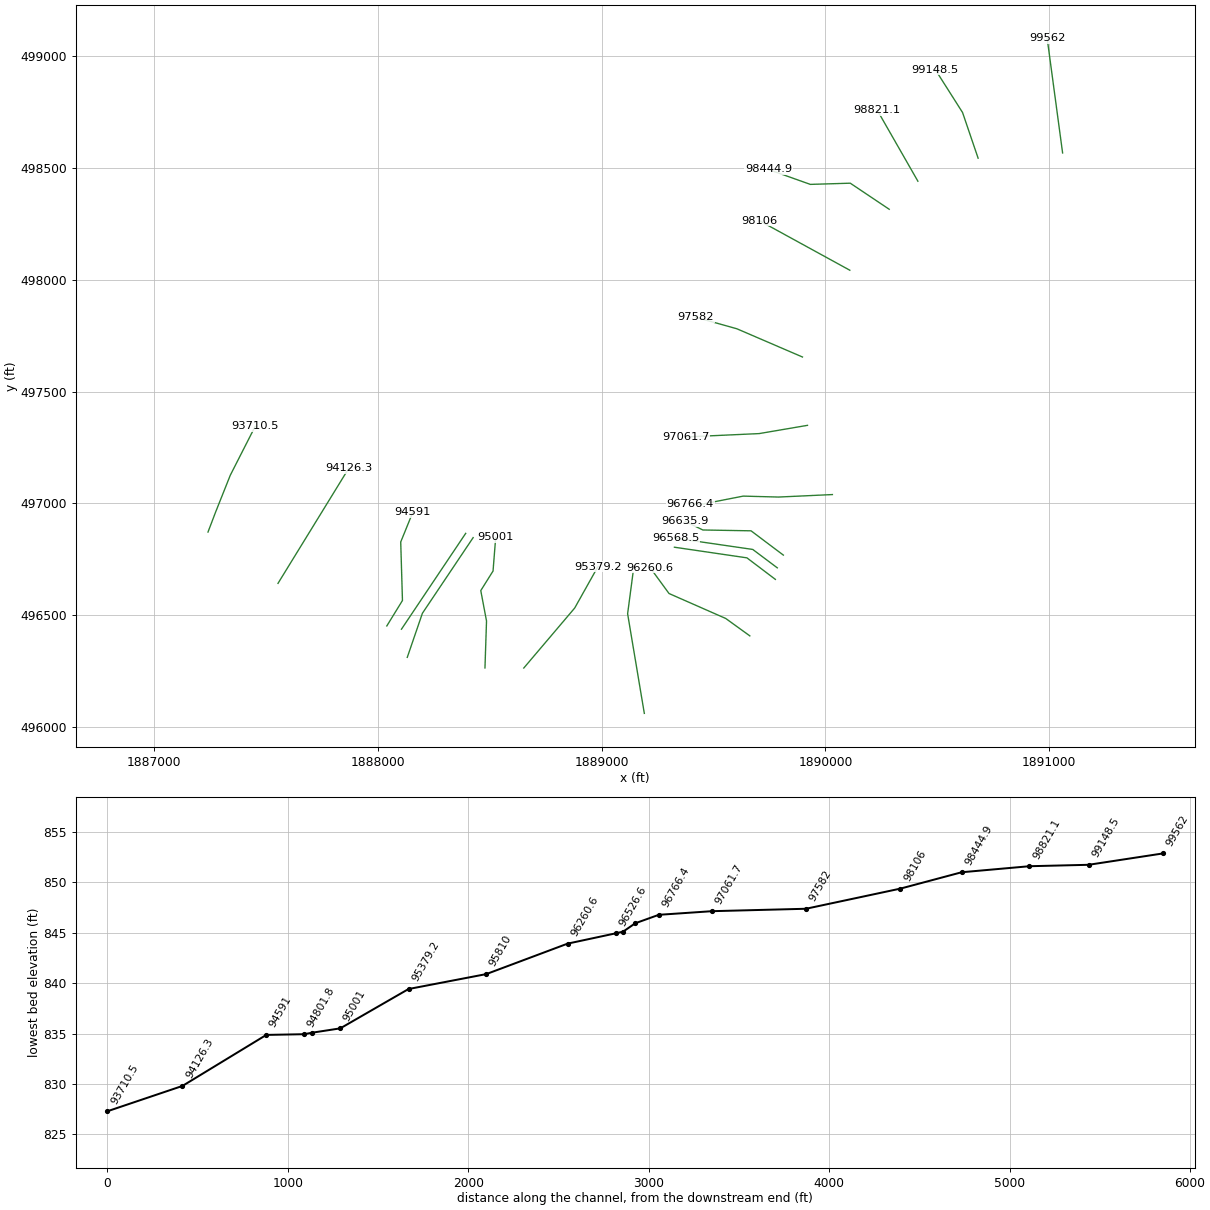
HEC-RAS study BLUECR.prj: BLUECR

--- BLUECR.g01 (geometry) --- (continued)

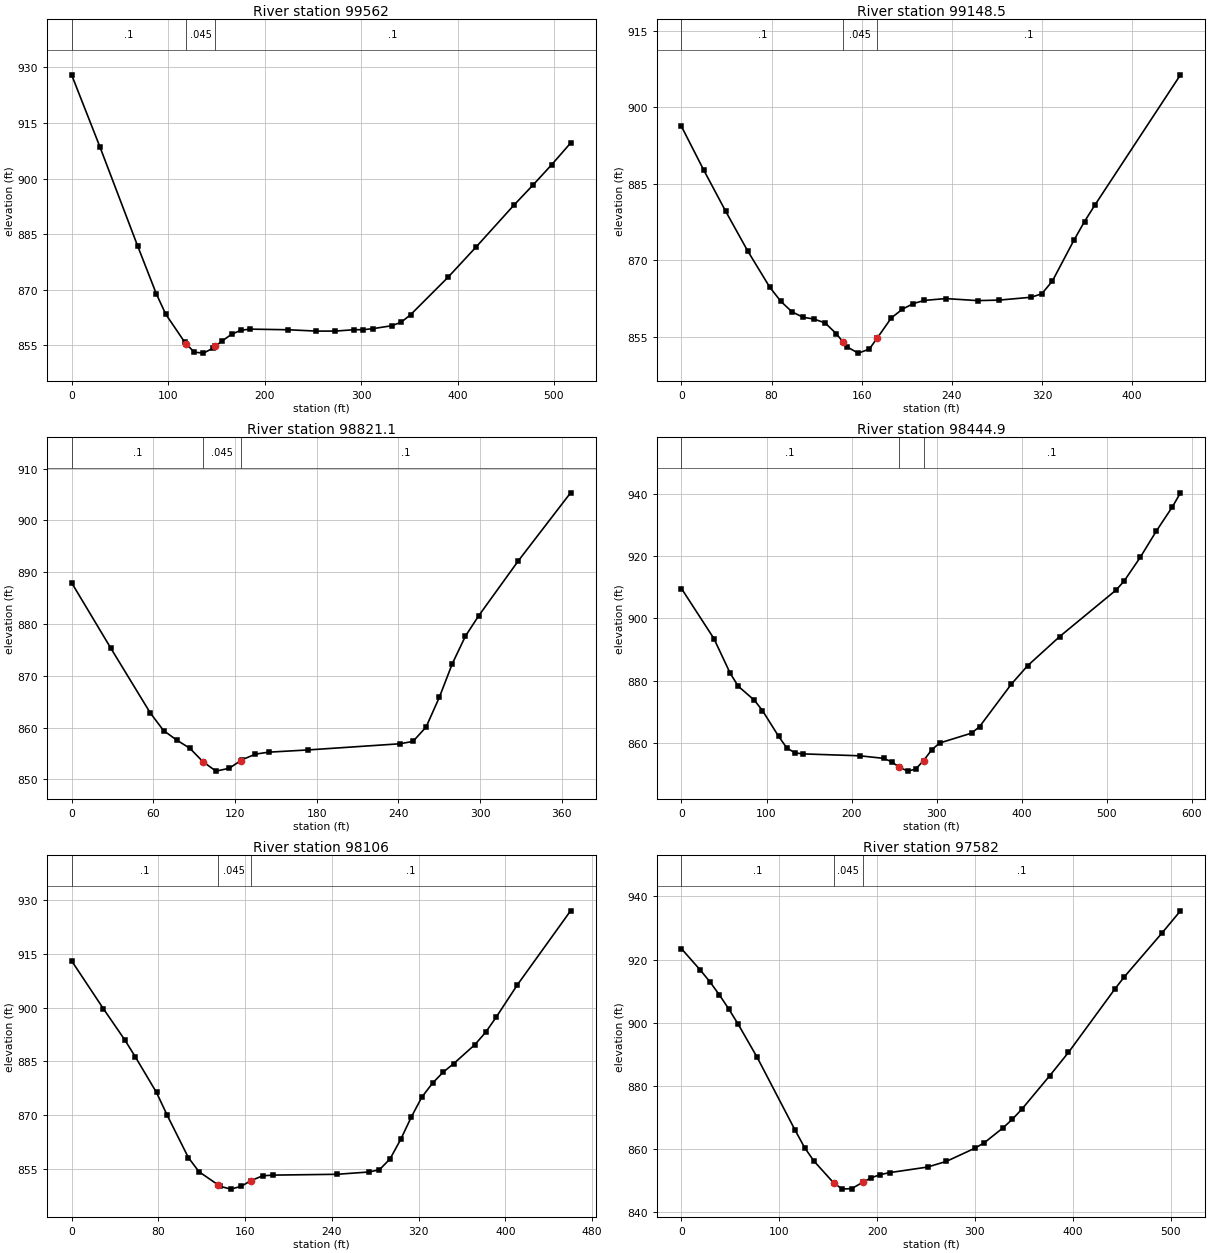
Type RM Length L Ch R = 1 ,99562   ,408.8,413.5,417.6
XS GIS Cut Line= 2
     1891059.968      498567.684     1890990.981      499080.251
#Sta/Elev= 30
       0  928.02    29.3  908.59    68.3   881.9    87.8  868.89    97.6  863.37
   117.1  855.88     119855.3484   126.9  853.14   136.6  852.87   146.4  854.17
     149854.7088   156.1  856.18   165.9  857.97   175.6  859.06   185.4  859.35
   224.4  859.18   253.7  858.82   273.2  858.82   292.8  859.19   302.5   859.2
   312.3  859.48   331.8  860.27   341.5   861.2   351.3  863.23   390.3  873.39
   419.6  881.63   458.6  892.87   478.2  898.25   497.7  903.78   517.2   909.6
#Mann= 3 , 0 , 0
       0      .1       0     119    .045       0     149      .1       0
Bank Sta=119,149
XS Rating Curve= 0 ,0
Exp/Cntr=0.3,0.1

Type RM Length L Ch R = 1 ,99148.5 ,322.8,327.4,331.5
XS GIS Cut Line= 3
     1890682.371      498544.344     1890612.859      498748.535
     1890491.031        498940.4
#Sta/Elev= 30
       0  896.24    19.6  887.74    39.2   879.6    58.8  871.79    78.4  864.67
    88.2  861.91      98  859.86   107.8  858.79   117.6  858.43   127.5  857.67
   137.3  855.58   143.6853.8893   147.1  852.95   156.9  851.74   166.7  852.52
   173.6854.6463   186.3  858.66   196.1  860.36   205.9  861.48   215.7  862.09
   234.6  862.45     263  862.05     282  862.15   310.4  862.71   319.9  863.39
   329.3   865.9   348.3  873.86   357.8  877.58   367.2  880.87     443  906.38
#Mann= 3 , 0 , 0
       0      .1       0   143.6    .045       0   173.6      .1       0
Bank Sta=143.6,173.6
XS Rating Curve= 0 ,0
Exp/Cntr=0.3,0.1

Type RM Length L Ch R = 1 ,98821.1 ,351,376.2,400.3
XS GIS Cut Line= 2
     1890413.266      498441.264     1890231.365      498759.285
#Sta/Elev= 23
       0  887.98    28.9  875.29    57.8  862.82    67.5  859.44    77.1  857.61
    86.8  856.02    96.4  853.43     106   851.6   115.7  852.15   124.2853.6282
   125.3  853.82     135  854.88   144.6  855.26   173.5  855.69     241  856.88
   250.7  857.34   260.3  860.12     270  865.84   279.6  872.38   289.2  877.67
   298.9  881.59   327.8  892.13   366.4  905.34
#Mann= 3 , 0 , 0
       0      .1       0    96.4    .045       0   124.2      .1       0
Bank Sta=96.4,124.2
XS Rating Curve= 0 ,0
Exp/Cntr=0.3,0.1

Type RM Length L Ch R = 1 ,98444.9 ,350.6,338.9,326.5
XS GIS Cut Line= 4
      1890285.09      498315.747     1890111.046      498432.425
     1889932.627      498427.077     1889745.385      498493.689
#Sta/Elev= 30
       0  909.56    38.1  893.53    57.2  882.43    66.7  878.24    85.7  873.74
    95.2  870.43   114.3  862.12   123.8  858.46   133.3  856.86   142.9  856.53
   209.5  855.92   237.7   855.1   247.1     854   255.3852.4036   265.9     851
   275.3  851.64   284.7  854.37   294.1  857.79   303.5  860.01   341.1  863.19
   350.5  865.26     388  878.94     407   884.8   444.8  894.18   511.1  909.09
   520.5  911.96   539.4  919.53   558.4     928   577.3  935.78   586.8  940.27
#Mann= 3 , 0 , 0
       0      .1       0   255.3    .045       0   284.7      .1       0
Bank Sta=255.3,284.7
XS Rating Curve= 0 ,0
Exp/Cntr=0.3,0.1

Type RM Length L Ch R = 1 ,98106   ,521.3,524,524.8
XS GIS Cut Line= 2
     1890108.936      498043.209     1889705.455      498264.464
#Sta/Elev= 30
       0  913.07    29.4  899.67      49  891.03    58.7  886.31    78.3  876.34
    88.1  870.02   107.7  858.17   117.5  854.23     135850.5914   137.1  850.15
   146.9  849.38   156.6  850.19     165851.6899   176.2   853.1     186  853.29
   244.8  853.52   274.1  854.16   283.9  854.78   293.7  857.82   303.5  863.24
   313.3   869.5   323.1  875.08   332.9  878.95   342.7  882.02   352.5  884.42
     372  889.71   381.8  893.11   391.6  897.36   411.2   906.4   460.2  927.02
#Mann= 3 , 0 , 0
       0      .1       0     135    .045       0     165      .1       0
Bank Sta=135,165
XS Rating Curve= 0 ,0
Exp/Cntr=0.3,0.1

Type RM Length L Ch R = 1 ,97582   ,509.6,520.3,530.6
XS GIS Cut Line= 3
     1889897.434       497655.08     1889604.251      497781.347
     1889420.499      497832.897
#Sta/Elev= 30
       0  923.41    19.4  916.61      29  912.97    38.7  908.84    48.4  904.33
      58  899.51    77.4  889.04   116.1  866.05   125.8  860.54   135.4  856.26
   155.4849.4052   164.4  847.38   174.1  847.57   185.4849.5489   193.5  850.91
   203.1  851.96   212.8   852.6   251.5  854.36   270.8  856.16   299.9  860.32
   309.5  862.04   328.8  866.78   338.3  869.51   347.8  872.62   376.5  883.27
   395.6  890.62   443.3  910.79   452.8  914.56     491  928.31   510.1  935.41
#Mann= 3 , 0 , 0
       0      .1       0   155.4    .045       0   185.4      .1       0
Bank Sta=155.4,185.4
XS Rating Curve= 0 ,0
Exp/Cntr=0.3,0.1

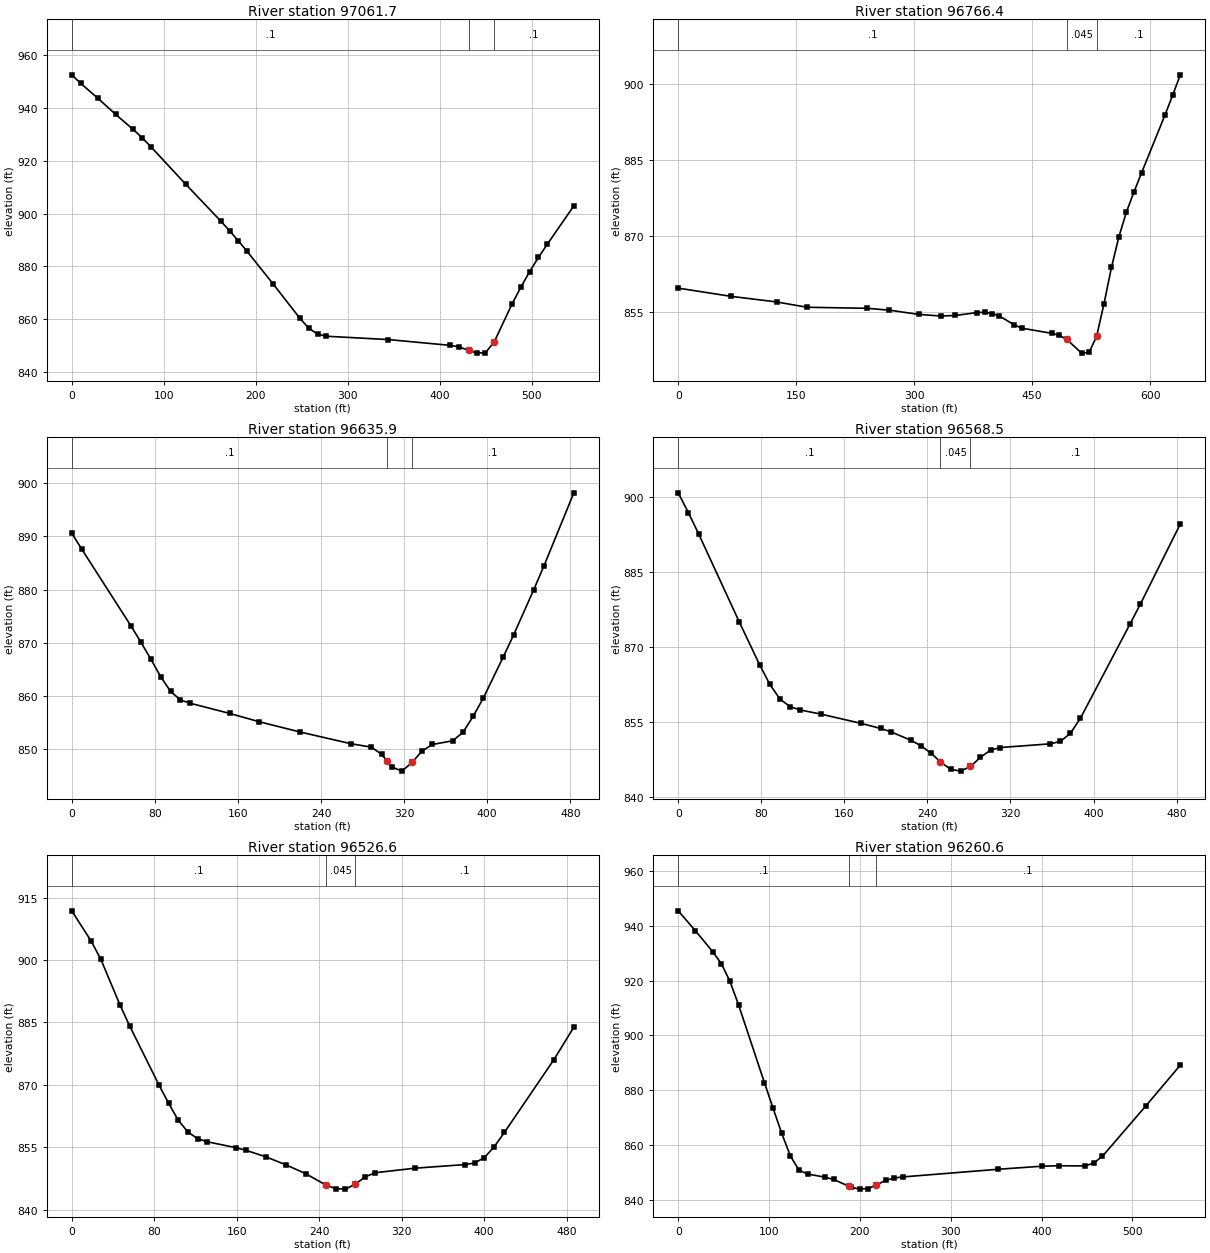
Type RM Length L Ch R = 1 ,97061.7 ,291.9,295.3,298.6
XS GIS Cut Line= 3
     1889919.862      497349.483     1889703.735       497312.57
     1889377.382      497297.683
#Sta/Elev= 30
       0  952.61     9.5  949.44    28.6  943.65    47.7  937.63    66.7  931.92
    76.3  928.85    85.8  925.44   123.9  911.15   162.1  897.16   171.6  893.51
   181.1  889.69   190.7  885.69   219.3   873.2   248.1  860.34   257.7  856.59
   267.3  854.35   276.9  853.54   344.2  852.28   411.4  850.09     421  849.51
   431.7848.1844   440.2  847.14   449.9  847.31   459.5  851.47   478.7   865.7
   488.3  872.08   497.9  878.02   507.5  883.41   517.1  888.39     546  902.95
#Mann= 3 , 0 , 0
       0      .1       0   431.7    .045       0   459.5      .1       0
Bank Sta=431.7,459.5
XS Rating Curve= 0 ,0
Exp/Cntr=0.3,0.1

Type RM Length L Ch R = 1 ,96766.4 ,135.3,130.6,125.8
XS GIS Cut Line= 5
     1890031.124      497039.899     1889790.847      497028.787
     1889632.513      497032.954      1889455.43      496998.232
     1889396.402      496998.926
#Sta/Elev= 30
       0  859.63    67.4     858   125.1   856.9   163.6  855.85   240.5  855.64
   268.5  855.27   305.8  854.44   333.7  854.12   352.3  854.22   380.3  854.81
   389.6  854.85   398.9  854.61   408.4   854.1   427.4  852.36   436.9  851.71
   474.9   850.7   484.4  850.31   493.9  849.51   512.9  846.78   522.4  846.91
   531.9  850.07   541.4  856.56   550.9  863.77   560.4  869.83   569.9  874.69
   579.4  878.61   589.2  882.45   618.7  893.78   628.6  897.73   638.4   901.8
#Mann= 3 , 0 , 0
       0      .1       0   493.9    .045       0   531.9      .1       0
Bank Sta=493.9,531.9
XS Rating Curve= 0 ,0
Exp/Cntr=0.3,0.1

Type RM Length L Ch R = 1 ,96635.9 ,70.3,67.3,64.1
XS GIS Cut Line= 4
     1889812.006      496769.108     1889667.603      496877.765
     1889452.145      496881.489     1889373.812      496919.822
#Sta/Elev= 30
       0   890.6     9.5  887.64    57.1  873.16    66.6  870.13    76.1  866.97
    85.6  863.67    95.1  860.92   104.6   859.3   114.1  858.68   152.2  856.76
   180.7   855.2   219.9  853.28   268.9  851.08   288.5  850.44   298.3   849.1
   303.3847.8835     308  846.74   317.8  845.94   327.6  847.56   337.4  849.74
   347.2  850.94   366.8  851.64   376.6  853.21   386.4   856.2   396.2  859.64
   415.6  867.44   425.3  871.46   444.7  879.96   454.4  884.36   483.4  898.18
#Mann= 3 , 0 , 0
       0      .1       0   303.3    .045       0   327.6      .1       0
Bank Sta=303.3,327.6
XS Rating Curve= 0 ,0
Exp/Cntr=0.3,0.1

Type RM Length L Ch R = 1 ,96568.5 ,41.8,41.9,42.2
XS GIS Cut Line= 3
     1889784.922      496712.163     1889675.153       496794.48
     1889332.423      496844.406
#Sta/Elev= 30
       0  900.86     9.8  896.88    19.6  892.66    58.8  874.99    78.4  866.42
    88.2  862.49      98  859.55   107.8  858.01   117.6  857.36   137.2  856.54
   175.7   854.7   194.9  853.66   204.6  853.01   223.8  851.32   233.4  850.23
     243  848.78   252.6  846.97   262.3  845.48   271.9  845.11   281.5  846.04
   291.1  847.88   300.8  849.32   310.4  849.84   358.5  850.58   368.1  851.07
   377.7  852.67   387.4  855.71   435.4  874.67   445.1  878.56   483.6  894.62
#Mann= 3 , 0 , 0
       0      .1       0   252.6    .045       0   281.5      .1       0
Bank Sta=252.6,281.5
XS Rating Curve= 0 ,0
Exp/Cntr=0.3,0.1

Type RM Length L Ch R = 1 ,96526.6 ,271.9,266,259.8
XS GIS Cut Line= 3
     1889776.312      496660.517     1889649.125       496756.87
     1889325.201      496804.406
#Sta/Elev= 30
       0  911.81    18.8  904.54    28.2  900.16    46.9  889.12    56.3  884.08
    84.5     870    93.9  865.58   103.2  861.54   112.6  858.67     122  857.07
   131.4  856.32   159.6  854.88   169.2  854.25   188.4  852.69   207.7  850.78
     227  848.64   246.2  845.96   255.9  845.05   265.5  844.94   275.1  846.14
   284.7   847.9   294.4  848.88   332.9  849.97     381  850.83   390.7  851.21
   400.3  852.53   409.9  855.17   419.6  858.55   467.7  876.07     487  883.86
#Mann= 3 , 0 , 0
       0      .1       0   246.2    .045       0   275.1      .1       0
Bank Sta=246.2,275.1
XS Rating Curve= 0 ,0
Exp/Cntr=0.3,0.1

Type RM Length L Ch R = 1 ,96260.6 ,472.9,450.6,427.4
XS GIS Cut Line= 4
     1889662.166      496407.892     1889554.486       496485.74
     1889301.055      496597.336     1889216.749      496712.753
#Sta/Elev= 30
       0  945.51      19   938.2      38  930.56    47.4  926.26      57  919.72
    66.4  911.19    94.9  882.77   104.4  873.46   113.9   864.3   123.4  856.09
   132.9  850.85   142.4  849.43   161.5  848.28   171.1  847.44   187.9844.9722
   190.2  844.62   199.7  843.92   209.3  844.14   217.9 845.425   228.4  847.12
   237.9  847.99   247.5  848.38   352.5  851.18   400.2  852.28   419.3  852.46
   447.9  852.38   457.4  853.45     467  855.93   514.6  874.24   552.7  889.18
#Mann= 3 , 0 , 0
       0      .1       0   187.9    .045       0   217.9      .1       0
Bank Sta=187.9,217.9
XS Rating Curve= 0 ,0
Exp/Cntr=0.3,0.1

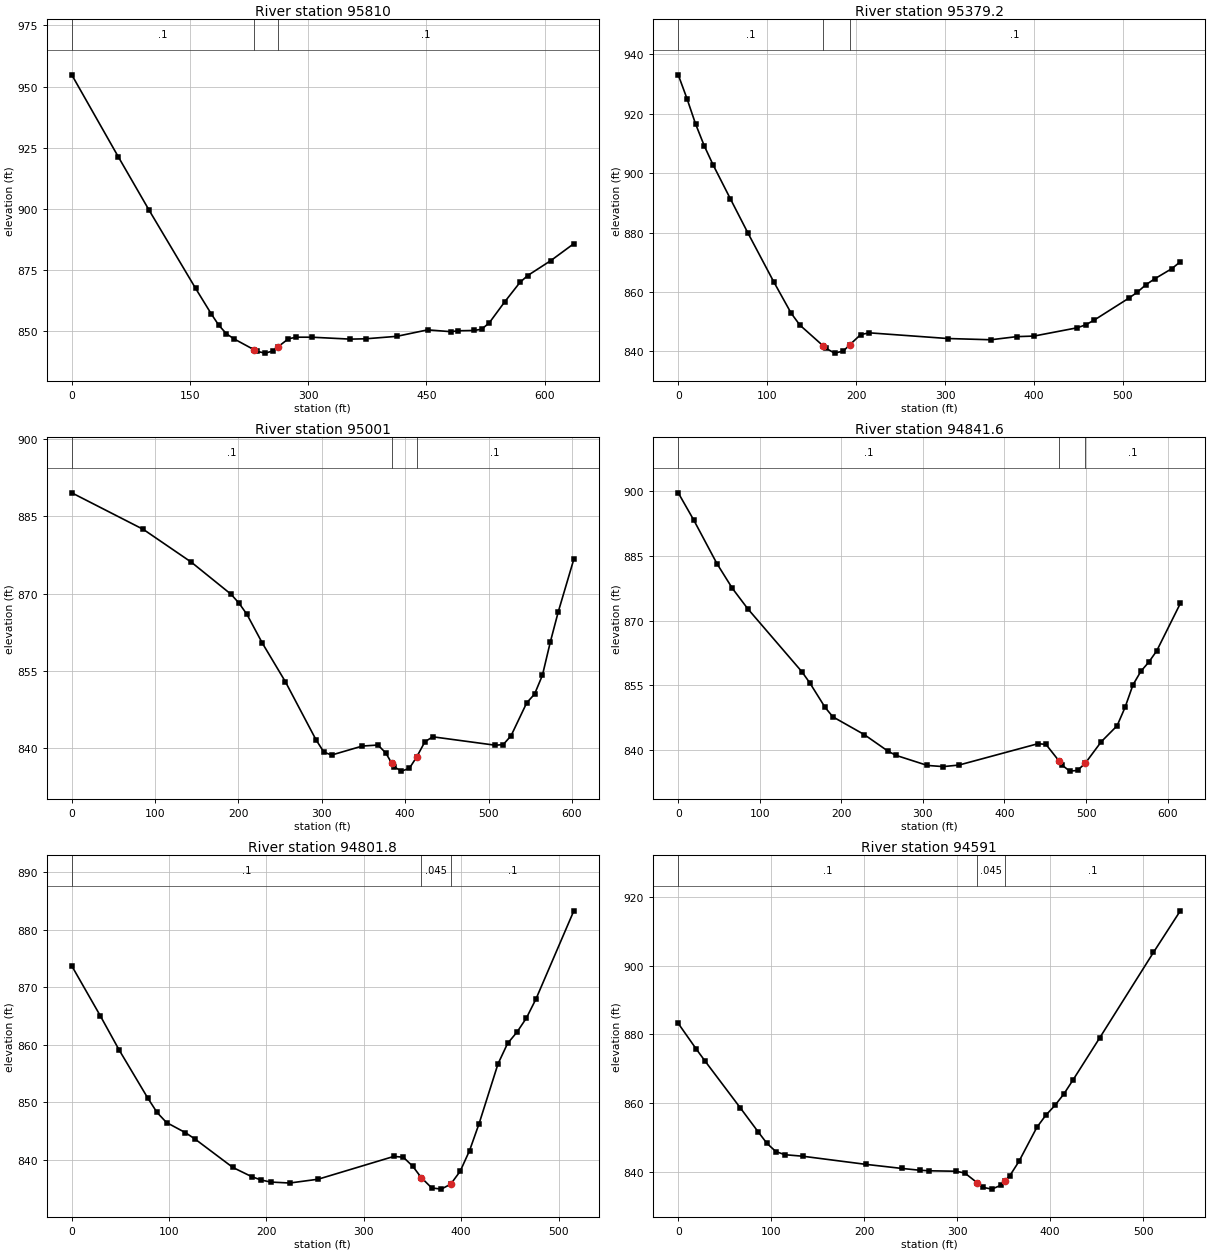
Type RM Length L Ch R = 1 ,95810   ,450.2,430.8,410.9
XS GIS Cut Line= 3
     1889190.636      496061.314     1889115.983      496506.626
     1889140.246      496690.543
#Sta/Elev= 30
       0   954.8    58.9  921.32    98.2  899.35     157  867.46   176.7   857.1
   186.5  852.32   196.3   848.8   206.1  846.69   231.4  842.27   235.6  841.58
   245.4   840.9   255.2  841.79   261.4843.4222   274.8  846.75   284.7  847.42
   304.3  847.42   353.4  846.63     373  846.77   412.3  847.77   451.5  850.42
   480.8  849.68   490.6  850.05   510.1  850.17   519.9  850.66   529.6  853.26
   549.2  861.85   568.7  869.87   578.4  872.64   607.8  878.77     637   885.7
#Mann= 3 , 0 , 0
       0      .1       0   231.4    .045       0   261.4      .1       0
Bank Sta=231.4,261.4
XS Rating Curve= 0 ,0
Exp/Cntr=0.3,0.1

Type RM Length L Ch R = 1 ,95379.2 ,374.9,378.2,381.3
XS GIS Cut Line= 3
     1888651.983      496264.154     1888879.413      496532.348
      1888983.58      496718.147
#Sta/Elev= 30
       0  933.08     9.8   925.1    19.5  916.54    29.3  909.16    39.1  902.84
    58.6  891.37    78.1     880   107.4  863.42     127  852.85   136.8  848.85
   163.2841.8032     166  841.07   175.8  839.42   185.6  840.12   193.2842.3073
   205.1  845.65   214.9  846.25   302.8  844.34   351.6  843.92   380.7  844.97
     400  845.16   448.5  847.94   458.2  848.94   467.8  850.54   506.6   857.9
   516.2  859.92   525.9  862.43   535.6  864.39     555  867.84   564.6  870.16
#Mann= 3 , 0 , 0
       0      .1       0   163.2    .045       0   193.2      .1       0
Bank Sta=163.2,193.2
XS Rating Curve= 0 ,0
Exp/Cntr=0.3,0.1

Type RM Length L Ch R = 1 ,95001   ,160.2,159.4,158.6
XS GIS Cut Line= 5
     1888478.465       496264.44     1888485.409       496474.51
     1888459.715      496610.447     1888514.576      496697.947
     1888526.381      496847.947
#Sta/Elev= 30
       0  889.59      86  882.47   143.3  876.13   191.1  869.88   200.6  868.16
   210.2  865.96   228.6  860.39   256.3  852.88   293.2  841.55   302.4  839.23
   311.6  838.64   348.5  840.39   367.3  840.59   376.7  839.05   383.6837.1121
   386.1  836.41   395.5  835.52   404.9  836.05   413.6838.2203   423.6  841.22
     433  842.19   508.2  840.55   517.6  840.68     527   842.4   545.8   848.8
   555.2  850.49   564.6  854.15   574.1  860.62   583.5  866.41   602.3  876.71
#Mann= 3 , 0 , 0
       0      .1       0   383.6    .045       0   413.6      .1       0
Bank Sta=383.6,413.6
XS Rating Curve= 0 ,0
Exp/Cntr=0.3,0.1

Type RM Length L Ch R = 1 ,94841.6 ,40.3,39.9,39.4
XS GIS Cut Line= 3
     1888131.242      496311.836     1888198.897      496509.102
     1888425.569      496847.263
#Sta/Elev= 30
       0  899.67      19  893.36    47.4  883.26    66.4  877.49    85.3  872.75
   151.7  858.13   161.2  855.59   180.1  849.86   189.6  847.68   227.9  843.58
     257  839.74   266.7  838.76   305.5   836.4   324.9  836.13   344.2  836.49
   441.2  841.45   450.9  841.28   467.1837.3892   470.2  836.54     480  835.08
   489.6  835.24   499.3  836.97   518.7  841.91   538.1  845.61   547.8  849.85
   557.5  855.08   567.2  858.24   576.9  860.37   586.6  862.97   615.6  873.99
#Mann= 3 , 0 , 0
       0      .1       0   467.1    .045       0   499.3      .1       0
Bank Sta=467.1,499.3
XS Rating Curve= 0 ,0
Exp/Cntr=0.3,0.1

Type RM Length L Ch R = 1 ,94801.8 ,196.1,210.8,225.2
XS GIS Cut Line= 2
     1888105.305      496437.821     1888392.235      496866.291
#Sta/Elev= 30
       0  873.71    29.2  865.07    48.6  859.12    77.8  850.83    87.6  848.25
    97.3  846.51   116.8  844.74   126.5  843.65   165.4  838.71   184.9   837.1
   194.6  836.52   204.3  836.17   223.8     836     253  836.66   330.8  840.62
   340.5  840.49   350.3   838.9   358.9836.9584   369.7  835.15   379.5  834.94
   389.2   835.8   398.9  838.03   408.6  841.64   418.4  846.33   437.8  856.69
   447.6  860.23   457.3  862.21     467  864.66   476.8  867.96   515.7  883.27
#Mann= 3 , 0 , 0
       0      .1       0   358.9    .045       0   389.2      .1       0
Bank Sta=358.9,389.2
XS Rating Curve= 0 ,0
Exp/Cntr=0.3,0.1

Type RM Length L Ch R = 1 ,94591   ,477.9,464.7,451.6
XS GIS Cut Line= 4
     1888039.749      496452.265     1888109.749      496566.154
     1888101.971      496827.821     1888156.416       496961.71
#Sta/Elev= 30
       0   883.2    19.1  875.82    28.6   872.3    66.8  858.55    85.9  851.59
    95.5  848.19     105  845.83   114.6  844.91   133.7  844.47   201.6   842.1
   240.3  840.91   259.7  840.38   269.4  840.22   298.5  840.09   308.2  839.57
   321.4836.7551   327.6   835.4   337.3  834.87     347     836   351.4837.2746
   356.7  838.81   366.4  842.93   385.8  852.93   395.5  856.47   405.1  859.26
   414.7  862.59   424.4  866.62   453.3  878.98   511.1  903.89     540  916.02
#Mann= 3 , 0 , 0
       0      .1       0   321.4    .045       0   351.4      .1       0
Bank Sta=321.4,351.4
XS Rating Curve= 0 ,0
Exp/Cntr=0.3,0.1

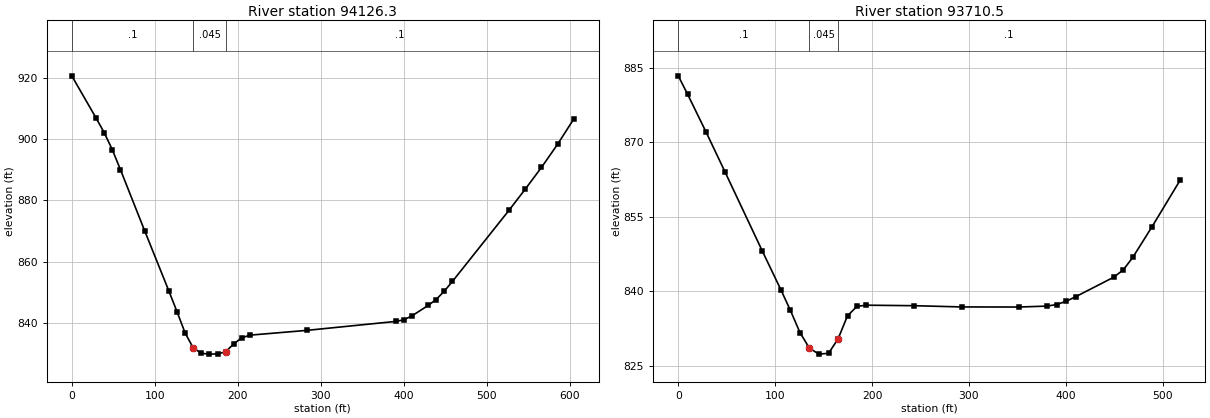
Type RM Length L Ch R = 1 ,94126.3 ,411.8,415.8,419.6
XS GIS Cut Line= 2
     1887553.466      496642.684     1887870.306      497158.309
#Sta/Elev= 30
       0  920.55    29.3  906.79      39  902.07    48.8  896.51    58.6     890
    87.8  870.07   117.1  850.36   126.9  843.61   136.7  836.66   146.4  831.84
   156.2  830.08   165.9  829.81   175.7  829.88   185.5  830.55   195.2  833.19
     205  835.12   214.8     836   283.1  837.55   390.4  840.47   400.2  840.98
     410  842.28   429.5  845.67   439.2  847.62     449  850.33   458.8   853.5
   527.1  876.73   546.6  883.59   566.2   890.7   585.7  898.27   605.2  906.52
#Mann= 3 , 0 , 0
       0      .1       0   146.4    .045       0   185.5      .1       0
Bank Sta=146.4,185.5
XS Rating Curve= 0 ,0
Exp/Cntr=0.3,0.1

Type RM Length L Ch R = 1 ,93710.5 ,265,262.1,258.9
XS GIS Cut Line= 4
     1887240.673      496872.232     1887274.936      496962.159
      1887340.19      497126.129     1887451.548      497344.884
#Sta/Elev= 27
       0  883.44     9.6  879.75    28.9  872.03    48.1  864.13    86.6  848.17
     106  840.26   115.8  836.11   125.6  831.66   135.4   828.5   145.2   827.3
   155.1  827.47   164.9  830.34   174.7  835.03   184.5  836.95   194.3  837.17
   243.3  837.07   292.4  836.82   351.3   836.8   380.7  836.99   390.5   837.3
   400.4  837.96   410.2  838.88   449.4  842.81   459.3  844.29   469.1   846.8
   488.7   852.9   518.2  862.44
#Mann= 3 , 0 , 0
       0      .1       0   135.4    .045       0   164.9      .1       0
Bank Sta=135.4,164.9
XS Rating Curve= 0 ,0
Exp/Cntr=0.3,0.1