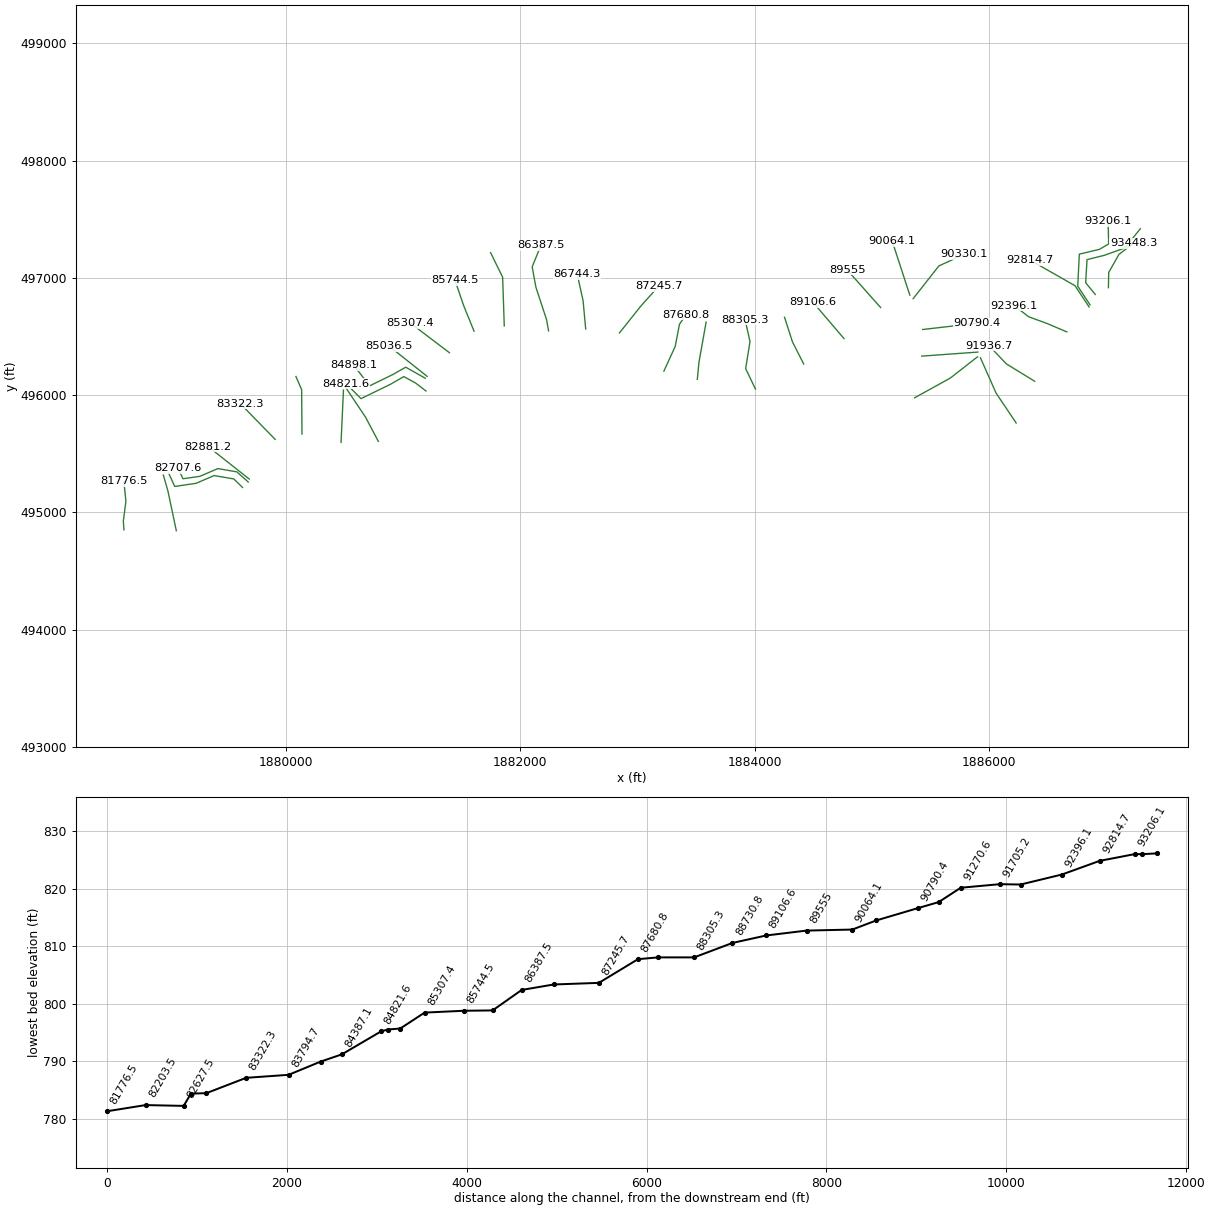
HEC-RAS study BLUECR.prj: BLUECR

--- BLUECR.g01 (geometry) --- (continued)

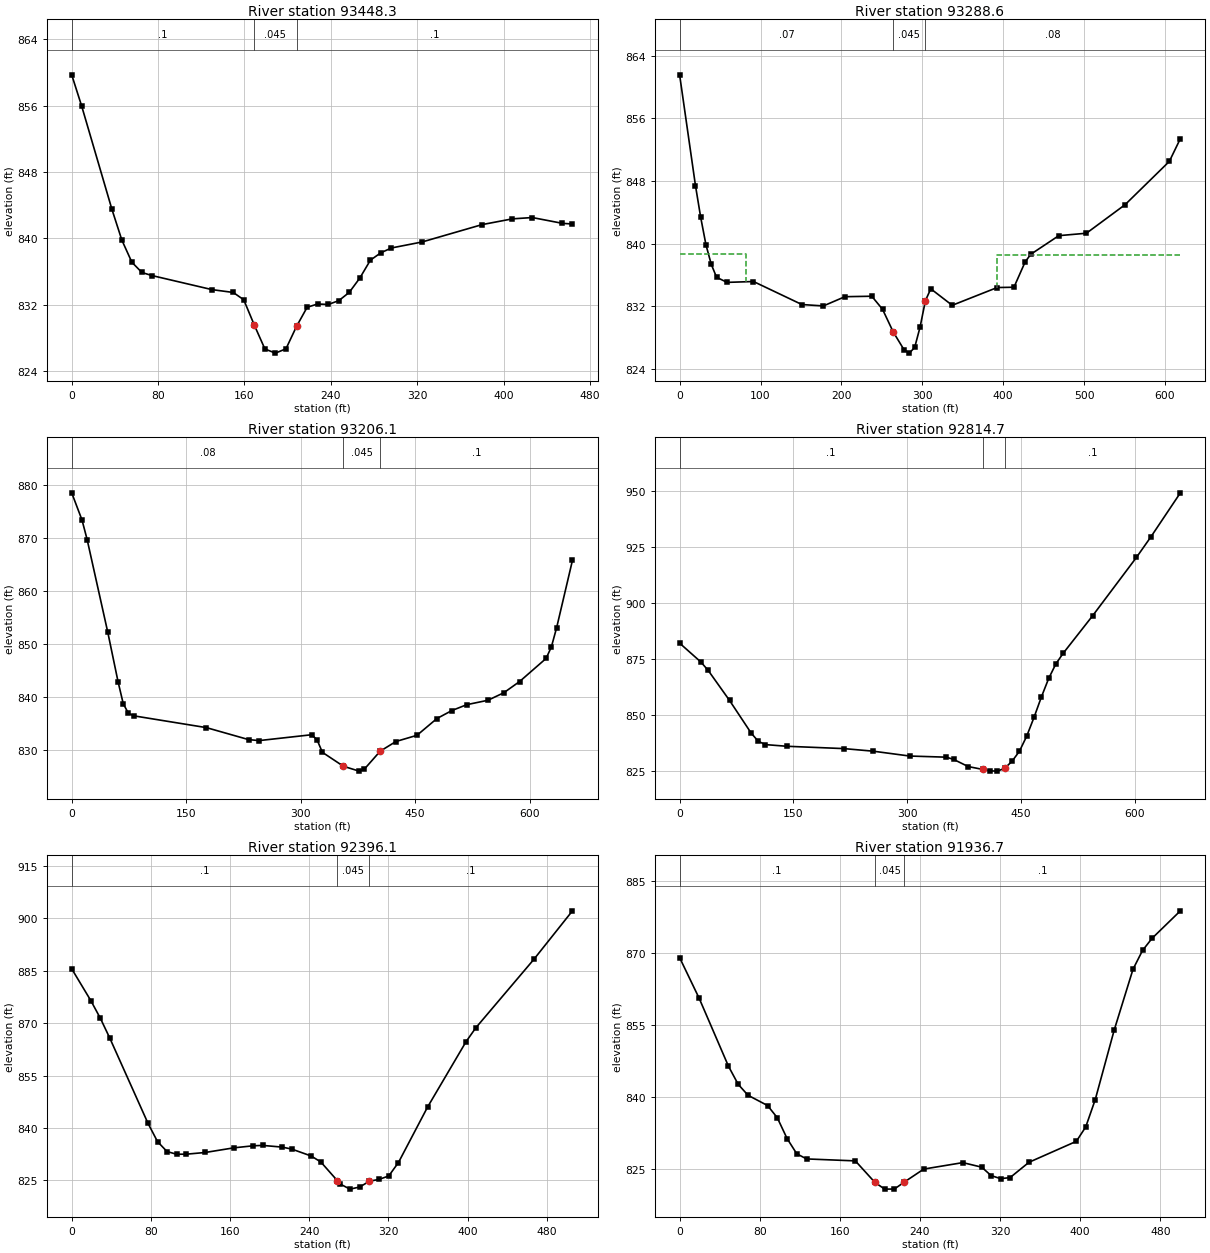
Type RM Length L Ch R = 1 ,93448.3 ,182.2,159.7,136.3
XS GIS Cut Line= 4
     1887017.661      496917.025     1887020.439      497047.025
      1887106.93      497200.131     1887232.277      497295.965
#Sta/Elev= 30
       0  859.72     9.3  855.92    37.2  843.51    46.4  839.79    55.7  837.11
      65  835.87    74.3   835.5     130   833.8   149.6  833.46   159.3  832.58
   169.1  829.52   178.9  826.64   188.6  826.14   198.4  826.66   208.2  829.37
     218  831.67   227.7  832.07   237.5  832.01   247.3  832.47     257  833.47
   266.8   835.2   276.6  837.36   286.3  838.25   296.1  838.83   324.4  839.55
   380.1  841.65     408  842.34   426.5   842.5   454.4   841.8   463.7  841.72
#Mann= 3 , 0 , 0
       0      .1       0   169.1    .045       0   208.2      .1       0
Bank Sta=169.1,208.2
XS Rating Curve= 0 ,0
Exp/Cntr=0.3,0.1

Type RM Length L Ch R = 1 ,93288.6 ,86.9,82.5,83.3
XS GIS Cut Line= 6
     1886905.416      496859.136     1886823.749      496959.136
     1886835.014      497156.251      1886980.57      497192.362
     1887156.072      497254.891     1887290.263      497419.576
#Sta/Elev= 30
       0  861.57  19.587  847.42  26.092  843.34  32.598  839.83  39.103  837.36
  45.679   835.7   58.69  835.05  91.287  835.16 151.109  832.22 177.696  832.04
 204.283  833.22 237.517  833.28 250.811  831.61 264.034  828.71 277.327  826.45
 283.903  826.01  290.55  826.74 297.197  829.34 303.773   832.7  310.42  834.23
 336.936  832.12 392.444  834.39 413.233  834.43 427.092  837.67 434.022  838.64
  468.67  841.02 502.824  841.33 550.624  844.98 605.283  850.51 618.931  853.42
#Mann= 3 , 0 , 0
       0     .07       0 264.034    .045       0 303.773     .08       0
#XS Ineff= 2 , 0
           82.05   838.7  392.31          838.59
Permanent Ineff=
       F       F
Bank Sta=264.034,303.773
XS Rating Curve= 0 ,0
Skew Angle= 45
Exp/Cntr=0.3,0.1

Type RM Length L Ch R = 1 ,93206.1 ,328.7,391.4,449.2
XS GIS Cut Line= 6
     1886860.971      496770.247     1886755.971      496929.691
     1886769.459      497202.918     1886940.014      497243.473
     1887019.814      497289.945     1887014.847      497485.687
#Sta/Elev= 30
       0  878.53  13.506   873.4  20.223  869.71  47.235  852.24   60.74  842.89
  67.529  838.74  74.246  836.95  81.034  836.46 176.423  834.23 231.719  831.97
 245.507  831.78 314.592  832.89 321.521  831.91 328.451  829.57 355.958  826.94
 376.605  826.02 383.535  826.41 404.182  829.78  424.83  831.61 452.407  832.78
 478.499  835.94 498.086  837.45 517.673  838.56 545.391  839.39  566.18  840.81
 586.899  842.93 621.547  847.28 628.477  849.45 635.406   853.1 656.124   865.8
#Mann= 3 , 0 , 0
       0     .08       0 355.958    .045       0 404.182      .1       0
Bank Sta=355.958,404.182
XS Rating Curve= 0 ,0
Skew Angle= 45
Exp/Cntr=0.3,0.1

Type RM Length L Ch R = 1 ,92814.7 ,414.8,418.6,422.4
XS GIS Cut Line= 3
     1886852.742      496752.816     1886733.072      496933.369
     1886347.605      497153.406
#Sta/Elev= 30
       0  881.98    28.2  873.51    37.7   869.8    65.9  856.38    94.2  841.92
   103.6   838.2     113  836.69   141.3  835.94   216.6   834.9   255.2  833.75
   303.4  831.58   351.7  831.07   361.3   830.1   380.6  826.88   399.9   825.6
   409.6  824.96   419.2  824.84   428.9  826.13   438.5  829.26   448.2  833.72
   457.8  840.44   467.5  848.87   477.1  857.88   486.8  866.23   496.4   872.8
   506.1  877.54   544.7  894.19   602.6  920.29   621.9  929.58   660.5   949.1
#Mann= 3 , 0 , 0
       0      .1       0   399.9    .045       0   428.9      .1       0
Bank Sta=399.9,428.9
XS Rating Curve= 0 ,0
Exp/Cntr=0.3,0.1

Type RM Length L Ch R = 1 ,92396.1 ,463.9,459.4,454.9
XS GIS Cut Line= 4
      1886663.07      496539.584     1886494.737      496611.251
      1886338.07      496668.473     1886214.181      496763.473
#Sta/Elev= 30
       0  885.56    19.3  876.46    28.9  871.42    38.5   865.7      77  841.36
    86.7  836.07    96.3  833.23   105.9  832.47   115.6  832.47   134.8  832.96
   163.7  834.29     183  834.87   192.8  834.99   212.4  834.51   222.2  833.95
   241.8  831.97   251.6  830.27   268.5824.8547   271.2  823.94   281.1  822.47
   290.9  823.07   300.7  824.73   310.5  825.26   320.3  826.24   330.1  830.09
   359.5  845.96   398.5  864.74   408.3  868.68   466.8  888.23   505.9  902.16
#Mann= 3 , 0 , 0
       0      .1       0   268.5    .045       0   300.7      .1       0
Bank Sta=268.5,300.7
XS Rating Curve= 0 ,0
Exp/Cntr=0.3,0.1

Type RM Length L Ch R = 1 ,91936.7 ,244.7,231.5,217.4
XS GIS Cut Line= 3
     1886388.834      496118.554     1886147.723      496266.332
     1885997.723      496423.554
#Sta/Elev= 30
       0  869.02    19.5  860.55    48.8  846.36    58.5  842.59    68.3  840.31
    87.8  838.17    97.5  835.64   107.3  831.29     117   828.1   126.8  827.03
   175.5  826.62     195  822.14   204.8  820.73   214.5  820.75   224.3  822.19
   243.8  824.91   282.8  826.26   301.7  825.31   311.1  823.55   320.6  822.92
     330  823.13   348.9  826.33   396.2   830.7   405.6  833.71   415.1  839.42
     434   853.9   452.8   866.6   462.3  870.51   471.8  873.04   500.1  878.78
#Mann= 3 , 0 , 0
       0      .1       0     195    .045       0   224.3      .1       0
Bank Sta=195,224.3
XS Rating Curve= 0 ,0
Exp/Cntr=0.3,0.1

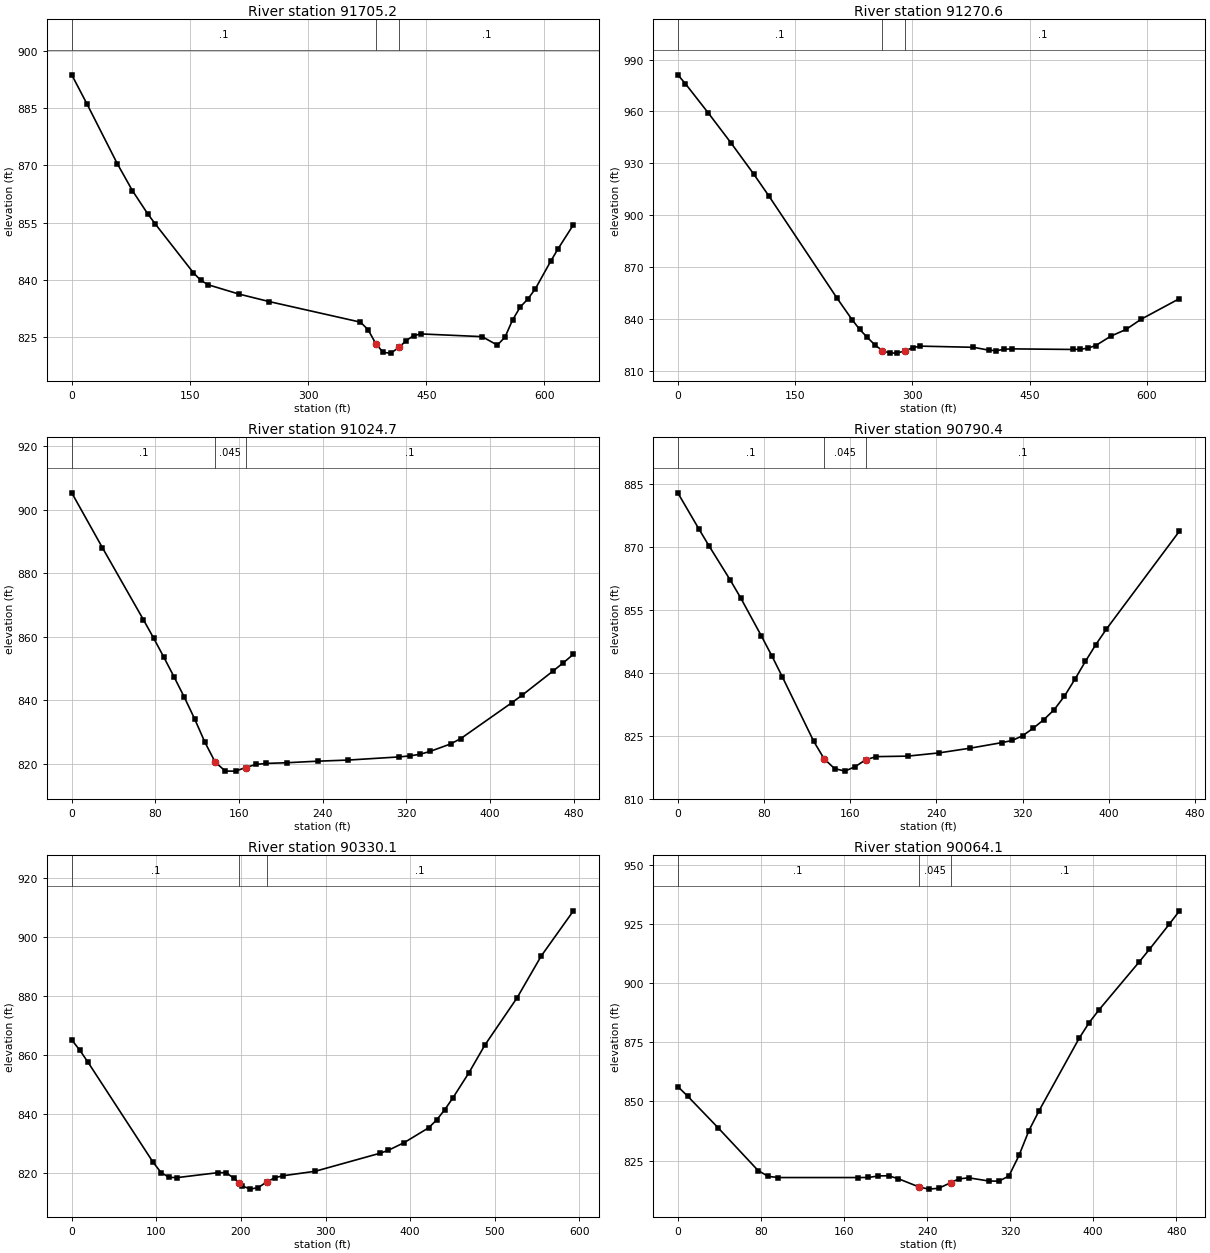
Type RM Length L Ch R = 1 ,91705.2 ,467.7,434.6,400.4
XS GIS Cut Line= 3
     1886230.732      495762.568     1886058.857      496018.644
     1885926.045      496318.991
#Sta/Elev= 30
       0  893.72    19.3   886.1    57.8  870.44    77.1  863.34    96.4   857.3
     106  854.64   154.2   841.9   163.8  839.85   173.5  838.68     212  836.28
   250.6   834.3   366.4  828.91     376  826.97   385.9823.3001   395.3  820.96
     405  820.79   415.9822.3775   424.3  824.04     434  825.39   443.6  825.82
   520.9  825.11   540.2  822.89   549.9  824.97   559.5  829.45   569.2  832.86
   578.9  834.96   588.5  837.65   607.8  844.82   617.5   848.2   636.8  854.44
#Mann= 3 , 0 , 0
       0      .1       0   385.9    .045       0   415.9      .1       0
Bank Sta=385.9,415.9
XS Rating Curve= 0 ,0
Exp/Cntr=0.3,0.1

Type RM Length L Ch R = 1 ,91270.6 ,255,245.9,235.4
XS GIS Cut Line= 3
     1885364.526      495977.628     1885669.804      496146.471
     1885900.533      496326.679
#Sta/Elev= 30
       0  981.21     9.7   976.1    38.8  959.26    67.8  941.97    96.9  923.92
   116.3  911.24   203.5   852.1   222.9  839.53   232.6  833.91   242.3  829.31
     252  824.96   261.6  821.58   271.3  820.17     281  820.26   290.7  821.52
   300.4  823.32   310.1  824.22   378.1  823.54   397.6  821.91   407.4  821.56
   417.2   822.4   426.9  822.63     505   822.3   514.8  822.43   524.5  823.04
   534.3   824.5   553.8  829.98   573.3  833.88   592.8  839.84   641.6  851.72
#Mann= 3 , 0 , 0
       0      .1       0   261.6    .045       0   290.7      .1       0
Bank Sta=261.6,290.7
XS Rating Curve= 0 ,0
Exp/Cntr=0.3,0.1

Type RM Length L Ch R = 1 ,91024.7 ,233.2,234.3,235.2
XS GIS Cut Line= 2
     1885425.268      496333.031     1885903.709      496367.534
#Sta/Elev= 29
       0  905.26    29.4  887.94    68.5  865.34    78.3  859.54    88.1   853.5
    97.9  847.29   107.7   840.9   117.5  834.11   127.3  826.77     137  820.59
   146.8  817.68   156.6  817.67   166.2818.7966   176.2  819.78     186   820.1
   205.6  820.31     235   820.8   264.3  821.15   313.3  822.15     323  822.46
   332.8  822.96   342.6  823.87   362.2  826.22     372  827.92     421  839.25
   430.7  841.58   460.1  849.15   469.9  851.73   479.7  854.45
#Mann= 3 , 0 , 0
       0      .1       0     137    .045       0   166.2      .1       0
Bank Sta=137,166.2
XS Rating Curve= 0 ,0
Exp/Cntr=0.3,0.1

Type RM Length L Ch R = 1 ,90790.4 ,442.2,460.3,477.8
XS GIS Cut Line= 2
      1885433.26      496560.128     1885895.687      496613.182
#Sta/Elev= 30
       0  882.83    19.4  874.31    29.1  870.16    48.5  862.15    58.2  857.91
    77.6  848.76    87.3  844.03      97  839.05   126.1  823.72   135.8  819.54
   145.5  817.21   155.2  816.61   164.8  817.71   174.6  819.34   184.2  820.06
   213.3  820.18   242.4  820.95   271.5  822.08   300.6  823.39   310.3   823.9
     320  825.04   329.7   826.8   339.4   828.8   349.1  831.18   358.8  834.45
   368.5  838.48   378.2  842.71   387.9  846.72   397.6  850.36   465.5  873.72
#Mann= 3 , 0 , 0
       0      .1       0   135.8    .045       0   174.6      .1       0
Bank Sta=135.8,174.6
XS Rating Curve= 0 ,0
Exp/Cntr=0.3,0.1

Type RM Length L Ch R = 1 ,90330.1 ,243.7,266,288.1
XS GIS Cut Line= 3
     1885352.193      496823.428     1885571.638      497102.595
     1885788.304      497201.206
#Sta/Elev= 30
       0  865.07     9.6  861.53    19.2   857.5      96  823.66   105.6  820.08
   115.2  818.46   124.8  818.39   172.8  820.06   182.3  820.04   191.9  818.16
     198816.5206   201.5  815.58   211.1  814.48   220.5  815.02   230.3  816.86
   239.9  818.32   249.5     819   287.9  820.54   364.6  826.66   374.1  827.62
   393.2  830.28   421.8  835.25   431.3   837.9   440.8  841.35   450.3  845.28
   469.4  853.85   488.4  863.31   526.5  879.34     555   893.5   593.1  908.82
#Mann= 3 , 0 , 0
       0      .1       0     198    .045       0   230.3      .1       0
Bank Sta=198,230.3
XS Rating Curve= 0 ,0
Exp/Cntr=0.3,0.1

Type RM Length L Ch R = 1 ,90064.1 ,498.4,509.1,516.9
XS GIS Cut Line= 2
      1885323.79      496853.023     1885173.802      497312.184
#Sta/Elev= 30
       0  856.31     9.7  852.14    38.6  838.96    77.3  820.78      87  818.31
    96.6   817.8   173.9   817.8   183.6  817.83   193.2  818.49   202.9  818.55
   212.5  817.28   231.9  813.88   241.5   812.9   251.2  813.26     263815.6682
   270.5  817.23   280.2  817.68   299.5  816.33   309.1  816.27   318.8  818.45
   328.5  827.13   338.1   837.7   347.8  846.04   386.4   876.7   396.1  883.37
   405.8  888.88   444.4  909.11   454.1  914.36   473.4   925.1     483  930.64
#Mann= 3 , 0 , 0
       0      .1       0   231.9    .045       0     263      .1       0
Bank Sta=231.9,263
XS Rating Curve= 0 ,0
Exp/Cntr=0.3,0.1

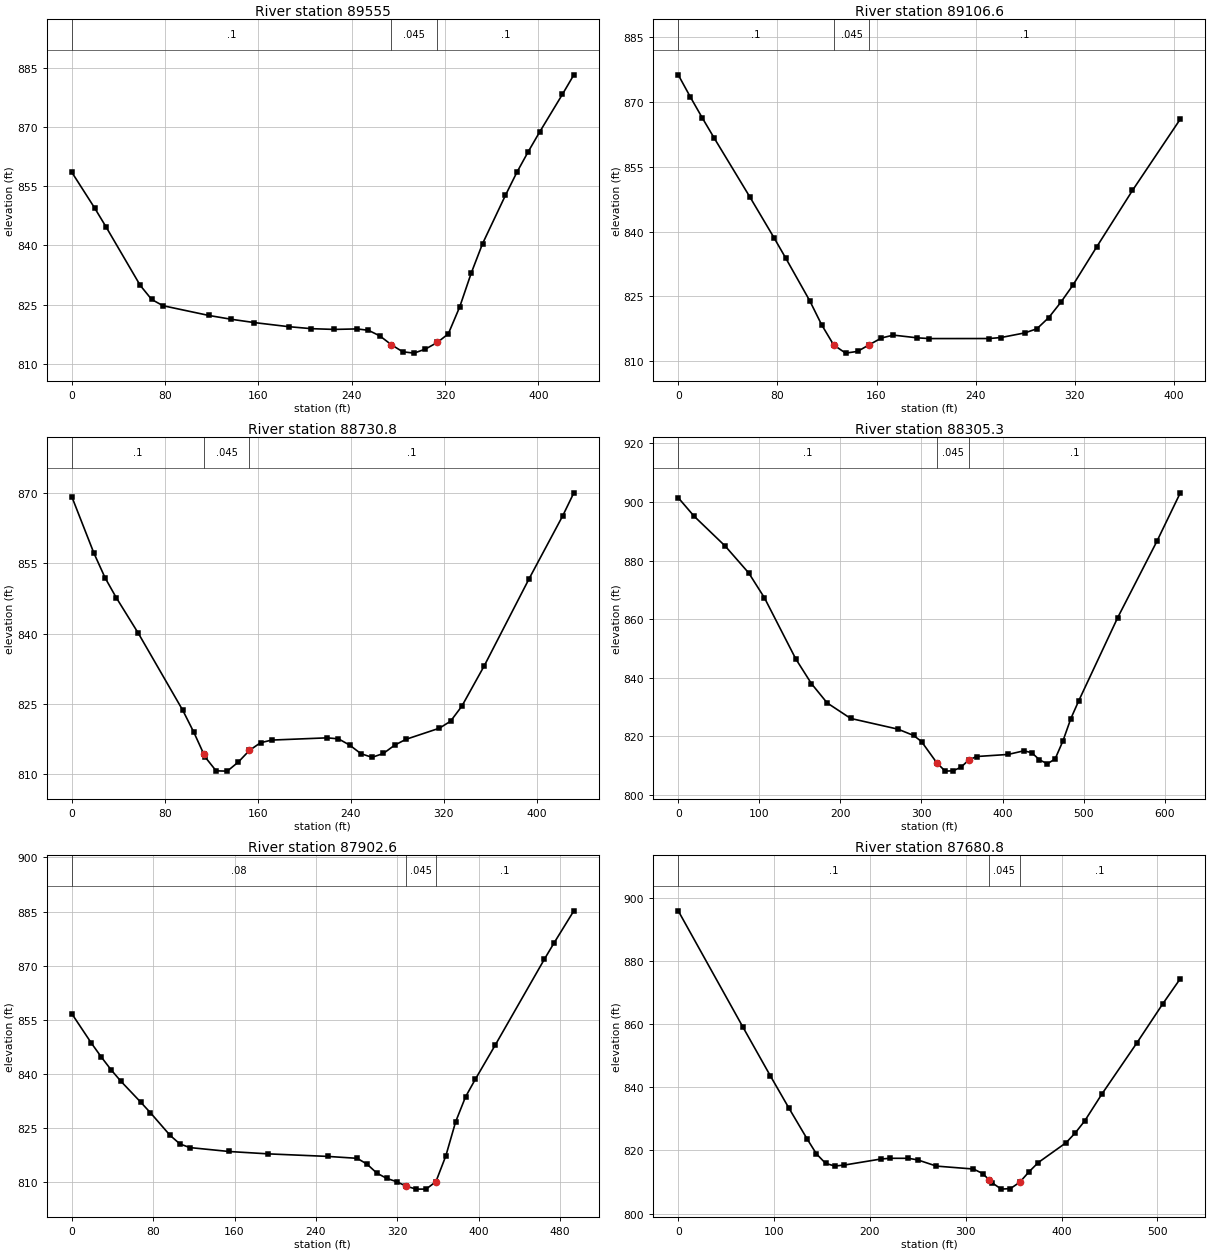
Type RM Length L Ch R = 1 ,89555   ,448.8,448.4,447.6
XS GIS Cut Line= 2
     1885074.589       496747.56     1884788.478      497069.088
#Sta/Elev= 30
       0  858.51    19.6  849.46    29.4  844.66    58.7  829.86    68.5   826.3
    78.2  824.72   117.4  822.26   136.9  821.28   156.5  820.45   185.8  819.42
   205.4  818.91     225  818.72   244.5  818.85   254.3   818.5   264.1  817.08
   273.9  814.86   283.7  813.06   293.4  812.72   303.2  813.75   313.5815.4463
   322.8  817.61   332.6  824.45   342.4  832.95   352.1   840.4   371.7  852.63
   381.5  858.45   391.3  863.71     401  868.65   420.6  878.22   430.4  883.16
#Mann= 3 , 0 , 0
       0      .1       0   273.9    .045       0   313.5      .1       0
Bank Sta=273.9,313.5
XS Rating Curve= 0 ,0
Exp/Cntr=0.3,0.1

Type RM Length L Ch R = 1 ,89106.6 ,381.2,375.9,370.6
XS GIS Cut Line= 2
     1884762.199       496482.74      1884499.04      496790.724
#Sta/Elev= 27
       0  876.32     9.6  871.28    19.3   866.4    28.9  861.73    57.9  847.98
    77.2  838.63    86.8  833.84   106.1     824   115.7  818.44   125.4  813.77
     135  811.87   144.7  812.27   154.3  813.84     164  815.38   173.6  816.04
   192.9  815.41   202.6  815.24   250.8  815.25   260.4  815.48   279.7  816.56
   289.4  817.51     299  820.12   308.6  823.61   318.3  827.55   337.6  836.46
   366.5  849.55   405.1  866.07
#Mann= 3 , 0 , 0
       0      .1       0   125.4    .045       0   154.3      .1       0
Bank Sta=125.4,154.3
XS Rating Curve= 0 ,0
Exp/Cntr=0.3,0.1

Type RM Length L Ch R = 1 ,88730.8 ,439.4,425.5,410.9
XS GIS Cut Line= 3
      1884418.28      496266.177     1884322.911      496453.509
     1884254.855       496664.62
#Sta/Elev= 30
       0  869.28    19.1  857.16    28.7   851.9    38.2   847.7    57.3  840.04
    95.6  823.54   105.1  818.84   113.7814.1458   114.7   813.6   124.2  810.63
   133.8  810.57   143.3  812.51   152.9  815.01   162.4  816.64     172  817.21
   219.8  817.69   229.5  817.47   239.1  816.14   248.8   814.3   258.4  813.52
   268.1  814.35   277.7   816.1   287.4  817.36   316.3  819.75   325.9  821.24
   335.6  824.45   354.9  833.09   393.4  851.67   422.4  865.16     432  870.09
#Mann= 3 , 0 , 0
       0      .1       0   113.7    .045       0   152.9      .1       0
Bank Sta=113.7,152.9
XS Rating Curve= 0 ,0
Exp/Cntr=0.3,0.1

Type RM Length L Ch R = 1 ,88305.3 ,402.9,402.6,402.2
XS GIS Cut Line= 4
     1884006.522      496052.398     1883923.188      496226.843
     1883960.411      496456.843     1883918.188      496645.176
#Sta/Elev= 30
       0  901.47    19.3  895.23      58  884.93      87  875.74   106.3  867.29
     145  846.39   164.3  837.95   183.7  831.36   212.7  826.06     271   822.4
   290.4  820.24   300.1  818.15   318.7810.9864   329.2  808.06     339  808.17
   348.7  809.38   358.4  811.89   368.1  813.05   406.9  813.76   426.3     815
     436  814.36   445.6  811.92   455.3  810.56   464.9  812.23   474.6  818.43
   484.2  825.96   493.9  832.03   542.1  860.53   590.4  886.57   619.3  903.14
#Mann= 3 , 0 , 0
       0      .1       0   318.7    .045       0   358.4      .1       0
Bank Sta=318.7,358.4
XS Rating Curve= 0 ,0
Exp/Cntr=0.3,0.1

Type RM Length L Ch R = 1 ,87902.6 ,222.1,221.9,221.5
XS GIS Cut Line= 3
     1883510.972      496135.304      1883524.76      496279.614
     1883585.891      496622.895
#Sta/Elev= 30
       0   856.7    19.3  848.52      29  844.69    38.7  841.12    48.3  837.96
    67.6  832.22    77.3  829.24    96.6  822.98   106.3  820.59     116  819.58
   154.6  818.49   193.4  817.83   251.5  817.13   280.6   816.6   290.2     815
   299.9  812.51   309.6  811.04   319.3  810.13     329  808.85   338.7  808.06
   348.4  808.07     358  810.13   367.7  817.24   377.4  826.73   387.1  833.62
   396.8  838.54   416.2  847.93   464.6  871.77   474.3  876.37   493.6   885.2
#Mann= 3 , 0 , 0
       0     .08       0     329    .045       0     358      .1       0
Bank Sta=329,358
XS Rating Curve= 0 ,0
Exp/Cntr=0.3,0.1

Type RM Length L Ch R = 1 ,87680.8 ,445.9,435.1,424.1
XS GIS Cut Line= 4
     1883225.758      496205.176     1883321.973      496414.725
     1883358.623      496604.639     1883414.994      496686.947
#Sta/Elev= 30
       0  895.83    67.2  859.19    96.1   843.6   115.3  833.48   134.5  823.62
   144.1  818.94   153.7  815.91   163.3  815.06   172.9  815.35   211.4  817.28
     221  817.51   240.2   817.5   249.9     817   269.3  815.04     308  814.11
   317.6  812.69   324.2810.7168   327.3  809.79     337  807.75   346.6  807.93
   356.3  809.93     366  813.25   375.6  816.16   404.7  822.46   414.3  825.58
     424  829.31   442.1  837.89   478.4  853.99   505.6  866.44   523.8  874.36
#Mann= 3 , 0 , 0
       0      .1       0   324.2    .045       0   356.3      .1       0
Bank Sta=324.2,356.3
XS Rating Curve= 0 ,0
Exp/Cntr=0.3,0.1

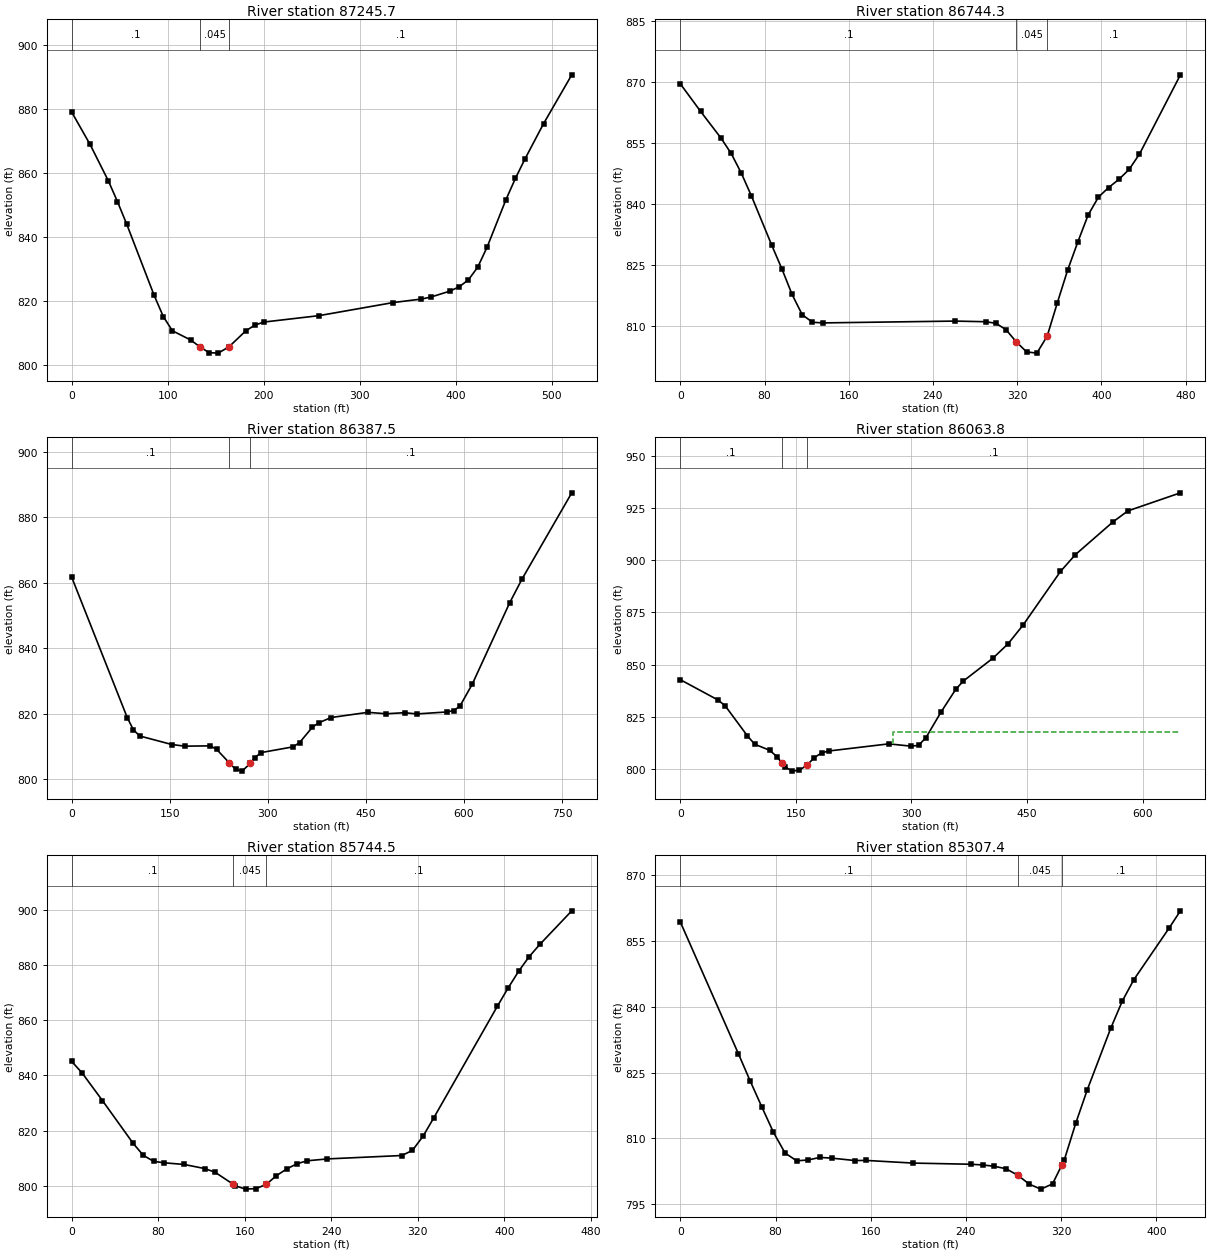
Type RM Length L Ch R = 1 ,87245.7 ,481.1,501.4,521.3
XS GIS Cut Line= 3
     1882846.758      496531.037     1883031.036      496762.259
     1883181.591      496929.481
#Sta/Elev= 30
       0  879.09    19.1  868.98    38.2  857.55    47.7  851.04    57.2  844.08
    85.8  821.77    95.4  815.07   104.9  810.63     124  807.72   133.9805.5146
   143.1  803.78   152.6  803.63   163.9805.6362   181.2  810.58   190.8  812.42
   200.3  813.36   257.5  815.36   334.8  819.46   364.2  820.56   373.9  821.17
   393.5  823.01   403.3  824.36   413.1  826.57   422.8  830.54   432.6  836.85
   452.2  851.69     462  858.31   471.8  864.31   491.3  875.44   520.7  890.74
#Mann= 3 , 0 , 0
       0      .1       0   133.9    .045       0   163.9      .1       0
Bank Sta=133.9,163.9
XS Rating Curve= 0 ,0
Exp/Cntr=0.3,0.1

Type RM Length L Ch R = 1 ,86744.3 ,354.5,356.9,359
XS GIS Cut Line= 3
     1882558.782      496564.433      1882536.56      496804.711
     1882486.213      497033.044
#Sta/Elev= 30
       0  869.49    19.3  862.71    38.6  856.18    48.3   852.4    57.9  847.58
    67.6  841.93    86.9  829.83    96.5  824.04   106.2  817.75   115.8  812.79
   125.5  810.94   135.1  810.77   260.8  811.22     290  811.06   299.8  810.69
   309.5  809.09   319.2  806.11     329  803.65   338.7  803.35   348.5   807.5
   358.2  815.73     368  823.77   377.7  830.69   387.4  837.25   397.2  841.66
   406.9  844.02   416.7  846.03   426.4  848.48   436.2  852.23   475.1   871.7
#Mann= 3 , 0 , 0
       0      .1       0   319.2    .045       0   348.5      .1       0
Bank Sta=319.2,348.5
XS Rating Curve= 0 ,0
Exp/Cntr=0.3,0.1

Type RM Length L Ch R = 1 ,86387.5 ,329.8,323.6,317
XS GIS Cut Line= 5
     1882241.872       496548.53     1882225.727      496641.586
     1882134.234      496920.058     1882102.116      497094.537
     1882177.636      497279.433
#Sta/Elev= 30
       0  861.72      85  818.76    94.4  815.02   104.2  813.14   153.1  810.54
   172.6  810.04   211.7  810.12   221.5  809.09     241  804.94   250.8  802.92
   260.6   802.4   273.4 804.824   280.1  806.54   289.9  808.08   338.7  809.83
   348.5  811.13     368  815.81   377.8  817.19   396.9  818.79   452.9  820.38
   480.9  819.94     509  820.27   527.6  819.89   574.5   820.5     584  820.92
   593.5  822.21   612.5  828.98   669.6  853.81   688.6  861.13   764.7   887.5
#Mann= 3 , 0 , 0
       0      .1       0     241    .045       0   273.4      .1       0
Bank Sta=241,273.4
XS Rating Curve= 0 ,0
Exp/Cntr=0.3,0.1

Type RM Length L Ch R = 1 ,86063.8 ,311.4,319.3,327.2
XS GIS Cut Line= 3
     1881864.129      496590.763      1881850.24      497006.041
     1881747.462      497215.763
#Sta/Elev= 30
       0  842.74    48.3  833.11      58  830.32      87  815.81    96.6  811.74
     116  808.84   125.6  805.72   132.1802.5906   135.3  801.05     145  798.84
   154.6   799.3   164.3  801.69   173.9  805.32   183.6  807.64   193.3  808.53
   270.6  811.93   299.6  810.82   309.2   811.2   318.9  814.95   338.2  827.09
   357.5  838.09   367.2  842.04   405.8  853.08   425.2  859.88   444.7  868.86
   493.4  894.68   512.8  902.77   561.5  918.46   580.9  923.76   649.1  932.44
#Mann= 3 , 0 , 0
       0      .1       0   132.1    .045       0   164.3      .1       0
#XS Ineff= 2 , 0
                          275.64          817.57
Permanent Ineff=
       F       F
Bank Sta=132.1,164.3
XS Rating Curve= 0 ,0
Exp/Cntr=0.3,0.1

Type RM Length L Ch R = 1 ,85744.5 ,424.8,437.1,449.1
XS GIS Cut Line= 3
     1881606.435      496545.627     1881517.369      496764.744
     1881444.512      496978.492
#Sta/Elev= 30
       0  845.08     9.5  840.99    28.4  830.92    56.8   815.4    66.2  811.04
    75.7  808.87    85.2  808.34   104.1  807.72     123  806.24   132.5  804.92
   149.2800.5867   151.4  799.98   160.8  798.78   170.3  798.97   179.8  800.46
   189.2  803.62   198.7  806.07   208.1  807.95   217.6  809.05   236.5  809.74
   305.3  810.97   315.1  812.84   324.9  817.98   334.7  824.56   393.6   865.1
   403.4  871.63   413.3  877.81   423.1  883.14   432.9  887.54   462.4  899.71
#Mann= 3 , 0 , 0
       0      .1       0   149.2    .045       0   179.8      .1       0
Bank Sta=149.2,179.8
XS Rating Curve= 0 ,0
Exp/Cntr=0.3,0.1

Type RM Length L Ch R = 1 ,85307.4 ,271.4,270.9,270.3
XS GIS Cut Line= 2
     1881396.351      496362.152     1881061.351      496616.041
#Sta/Elev= 30
       0  859.28    48.9  829.23    58.6  823.15    68.4  817.24    78.2  811.43
      88  806.69    97.8   804.9   107.5   805.1   117.3  805.68   127.1  805.52
   146.6  804.97   156.4  804.99   195.5  804.39   244.4  804.12   254.2  803.96
   263.9  803.66   273.7   803.1   283.5  801.64   293.3  799.59     303  798.46
   312.8  799.64   320.5803.8594   322.6  805.01   332.4  813.51   342.1  821.12
   361.7  835.05   371.5  841.29   381.2  846.16   410.6   857.8   420.3  861.81
#Mann= 3 , 0 , 0
       0      .1       0   283.5    .045       0   320.5      .1       0
Bank Sta=283.5,320.5
XS Rating Curve= 0 ,0
Exp/Cntr=0.3,0.1

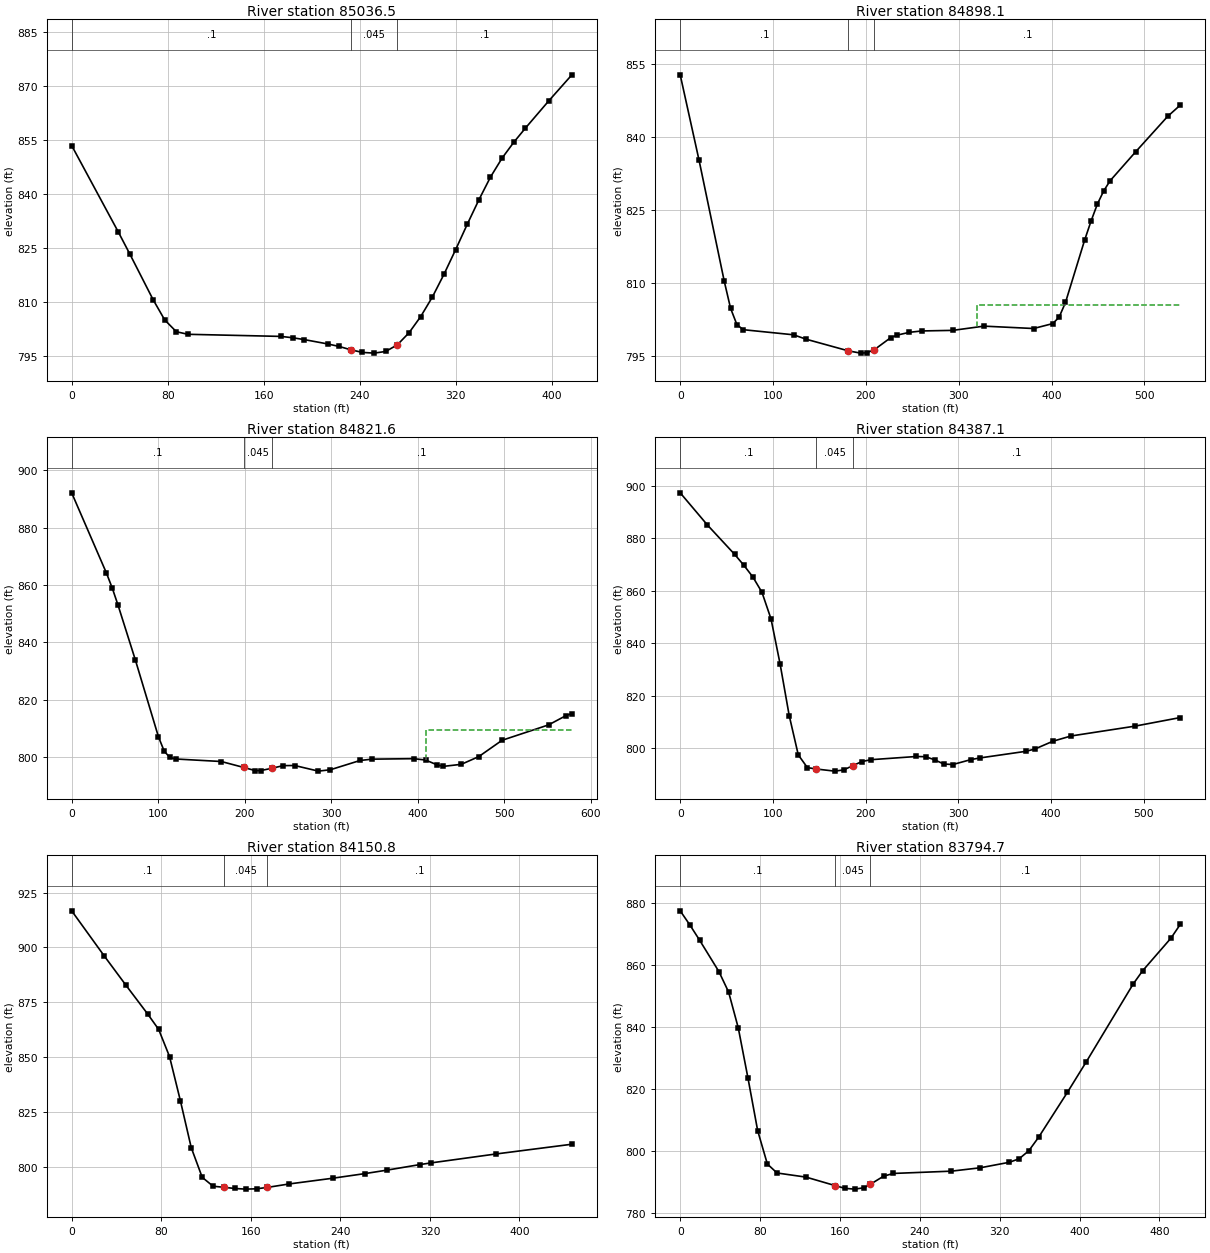
Type RM Length L Ch R = 1 ,85036.5 ,106,138.4,167.9
XS GIS Cut Line= 2
     1881206.174      496160.611      1880879.79      496419.586
#Sta/Elev= 30
       0  853.46    38.8  829.43    48.4  823.29    67.8  810.58    77.5  804.92
    87.2  801.64    96.9  800.93   174.4  800.34   184.1  799.97   193.8  799.45
   213.2  798.25   222.9  797.54   232.6   796.6   242.2  795.89   251.9  795.69
   261.6  796.16   271.3  798.02     281  801.37   290.7  805.87   300.4   811.3
   310.1  817.65   319.8   824.5   329.4  831.51   339.1  838.32   348.8  844.69
   358.5  849.98   368.2  854.37   377.9  858.31   397.3  865.88   416.6  873.14
#Mann= 3 , 0 , 0
       0      .1       0   232.6    .045       0   271.3      .1       0
Bank Sta=232.6,271.3
XS Rating Curve= 0 ,0
Exp/Cntr=0.3,0.1

Type RM Length L Ch R = 1 ,84898.1 ,80.1,76.5,76
XS GIS Cut Line= 5
     1881190.342      496144.271     1881023.403      496238.629
     1880911.248      496174.806     1880715.886       496079.54
     1880579.105      496256.442
#Sta/Elev= 30
       0  852.74  20.365  835.13  47.447   810.3  54.235  804.75  61.023   801.4
  67.812  800.34 122.047  799.29 135.623  798.38 181.231  795.98 194.242  795.52
 200.748  795.59 208.809  796.19  226.84  798.72 233.487  799.22 246.922   799.8
 260.215  800.08 293.661   800.2 327.108  801.07 380.565  800.58 401.142  801.59
 408.001  802.89  414.93  805.94 435.507  818.74 442.437  822.67 449.296  826.18
 456.155   828.9 463.013  830.97  490.52  836.92 524.885  844.18 538.674  846.54
#Mann= 3 , 0 , 0
       0      .1       0 181.231    .045       0 208.809      .1       0
#XS Ineff= 2 , 0
                         320.143          805.47
Permanent Ineff=
       F       F
Bank Sta=181.231,208.809
XS Rating Curve= 0 ,0
Skew Angle= 45
Exp/Cntr=0.3,0.1

Type RM Length L Ch R = 1 ,84821.6 ,472.3,434.5,395.8
XS GIS Cut Line= 6
     1881196.307      496035.767     1881105.902      496104.844
     1881007.016      496158.418     1880895.743      496094.121
     1880642.091      495970.431      1880514.51      496098.523
#Sta/Elev= 30
       0  892.13  40.234  864.15  46.952  858.91  53.599     853  73.751  833.78
 100.338  807.12 106.985  802.12 113.561  799.93 120.208  799.41 172.958  798.53
 198.909  796.46  211.92  795.38 218.425  795.37 231.365  796.16 244.376  797.09
  257.74  797.14 285.247  795.18 299.035  795.66 333.401  798.89 347.189  799.35
 395.343  799.52 409.132  799.05  422.85  797.31 429.779  796.84 450.427  797.55
  470.58  800.23  497.52  805.92 551.331  811.29 571.484  814.52 578.272  815.24
#Mann= 3 , 0 , 0
       0      .1       0 198.909    .045       0 231.365      .1       0
#XS Ineff= 2 , 0
                         409.238          809.34
Permanent Ineff=
       F       F
Bank Sta=198.909,231.365
XS Rating Curve= 0 ,0
Skew Angle= 45
Exp/Cntr=0.3,0.1

Type RM Length L Ch R = 1 ,84387.1 ,248,236.2,224
XS GIS Cut Line= 3
     1880789.996      495605.454     1880680.132      495813.415
     1880510.647      496066.348
#Sta/Elev= 30
       0  897.33    29.4  885.05    58.8  873.84    68.6  869.74    78.4  865.24
    88.2  859.41      98  849.24   107.8  832.05   117.6  812.41   127.4   797.4
   137.2  792.55     147     792   166.6   791.2   176.4  791.65   186.2  793.29
     196  794.84   205.8  795.56   254.8  796.78   264.7   796.7   274.5  795.52
   284.3  793.92   294.1  793.71   313.8  795.61   323.6  796.24   372.7  798.74
   382.5   799.6   402.2  802.61   421.8  804.61   490.6  808.35   539.7  811.64
#Mann= 3 , 0 , 0
       0      .1       0     147    .045       0   186.2      .1       0
Bank Sta=147,186.2
XS Rating Curve= 0 ,0
Exp/Cntr=0.3,0.1

Type RM Length L Ch R = 1 ,84150.8 ,354.8,356.2,357.2
XS GIS Cut Line= 2
     1880471.834      495597.354     1880492.534      496043.707
#Sta/Elev= 23
       0   916.7    29.1  896.14    48.6  882.72      68  869.63    77.7  862.68
    87.4  850.33    97.1   830.2   106.8  808.83   116.6  795.31   126.3  791.27
     136  790.77   145.7  790.24   155.4  789.94   165.1  790.09   174.8  790.72
   194.3   792.3   233.1   794.9   262.3  797.04   281.7   798.6   310.8   801.1
   320.6  801.86   378.8  805.94   446.8  810.39
#Mann= 3 , 0 , 0
       0      .1       0     136    .045       0   174.8      .1       0
Bank Sta=136,174.8
XS Rating Curve= 0 ,0
Exp/Cntr=0.3,0.1

Type RM Length L Ch R = 1 ,83794.7 ,454.5,472.3,489.2
XS GIS Cut Line= 3
     1880138.463       495668.35     1880135.686      496046.683
     1880087.213      496159.391
#Sta/Elev= 30
       0  877.63     9.7  873.06    19.4  868.16    38.8  857.97    48.5  851.36
    58.2  839.73    67.9  823.52    77.6  806.55    87.3  795.76      97  792.86
   126.1  791.52   155.2  788.78   164.9   787.9   174.6  787.64   184.3  788.09
   190.2789.1605   203.7  791.82   213.4  792.71   271.6  793.45   300.7  794.55
   329.8  796.33   339.5  797.46   349.2  800.06   358.9  804.37   387.8  818.93
   406.7  828.79   453.8  854.02   463.3   858.3   491.6  868.82     501  873.31
#Mann= 3 , 0 , 0
       0      .1       0   155.2    .045       0   190.2      .1       0
Bank Sta=155.2,190.2
XS Rating Curve= 0 ,0
Exp/Cntr=0.3,0.1

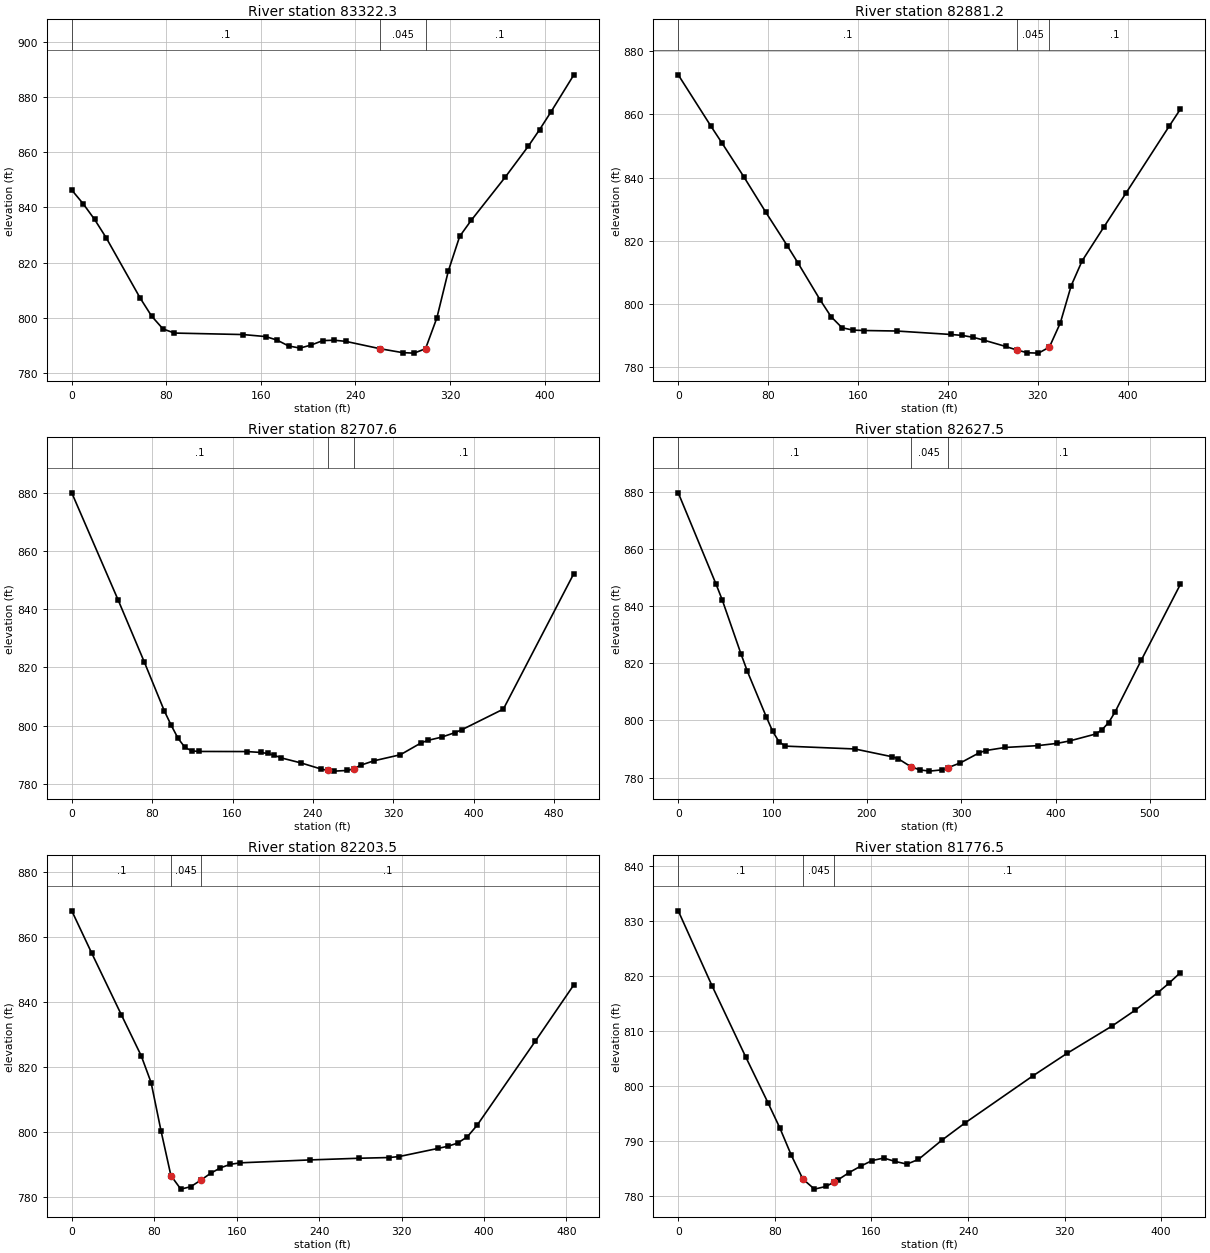
Type RM Length L Ch R = 1 ,83322.3 ,438.3,441.2,444.1
XS GIS Cut Line= 2
     1879909.748      495622.875      1879613.22      495927.042
#Sta/Elev= 30
       0  846.29     9.6  841.34    19.3  835.64      29  829.06    57.9  807.08
    67.6  800.53    77.2  795.89    86.9   794.4   144.8  793.86   164.1  793.13
   173.8  791.83   183.4  789.72   193.1  788.95   202.7  790.08   212.4  791.67
     222   791.8   231.7   791.4   260.7  788.73     280  787.29   289.6  787.12
   299.3  788.71   308.9   799.9   318.6  816.91   328.2  829.48   337.9  835.27
   366.9  851.06   386.2  862.16   395.8   868.2   405.5  874.68   424.8   888.1
#Mann= 3 , 0 , 0
       0      .1       0   260.7    .045       0   299.3      .1       0
Bank Sta=260.7,299.3
XS Rating Curve= 0 ,0
Exp/Cntr=0.3,0.1

Type RM Length L Ch R = 1 ,82881.2 ,138.1,173.5,211.3
XS GIS Cut Line= 2
      1879688.69       495284.43     1879337.995      495561.339
#Sta/Elev= 29
       0  872.54    29.1  856.29    38.9  850.98    58.3  840.31    77.7  829.18
    97.1  818.41   106.8  812.86   126.3   801.3     136     796   145.7  792.51
   155.4  791.74   165.1  791.62   194.3  791.46   242.8  790.36   252.6  790.07
   262.3  789.48     272  788.57   291.4  786.57   301.1  785.47   310.8  784.57
   320.6  784.46   330.3  786.37     340     794   349.7  805.81   359.4  813.65
   378.8  824.39   398.3  835.02   437.1  856.39   446.8  861.64
#Mann= 3 , 0 , 0
       0      .1       0   301.1    .045       0   330.3      .1       0
Bank Sta=301.1,330.3
XS Rating Curve= 0 ,0
Exp/Cntr=0.3,0.1

Type RM Length L Ch R = 1 ,82707.6 ,77.7,80.1,77.7
XS GIS Cut Line= 6
     1879680.132      495259.013     1879583.143      495345.812
     1879420.653      495373.555     1879266.764      495307.444
     1879123.362      495286.958     1879081.762      495377.077
#Sta/Elev= 30
       0  879.97  46.033  843.24  72.337  821.72  92.065  805.08  98.854  800.17
 105.783  795.63 112.571  792.53  119.43  791.32 126.289  791.12 174.302  791.08
  188.02  790.78 194.879  790.42 201.738  789.78 208.596  788.89 228.325  787.16
 248.053  785.09 254.629  784.63 261.205  784.36 274.357  784.59 280.934  785.22
  287.58   786.4 300.733  787.91 327.037  789.99 347.543  794.04 354.331  794.92
 367.978  796.03 381.696  797.63 388.484  798.63 429.497  805.67 499.642  852.24
#Mann= 3 , 0 , 0
       0      .1       0 254.629    .045       0 280.934      .1       0
Bank Sta=254.629,280.934
XS Rating Curve= 0 ,0
Skew Angle= 45
Exp/Cntr=0.3,0.1

Type RM Length L Ch R = 1 ,82627.5 ,477.2,424,372.5
XS GIS Cut Line= 6
     1879631.243      495212.902      1879557.21      495285.389
     1879388.986       495314.11     1879235.097      495247.999
      1879052.91      495221.235     1879000.512      495336.799
#Sta/Elev= 30
       0   879.7  39.952  847.83  46.598  842.25  66.609  823.22  73.256  817.22
  93.338  801.26 100.056  796.23 106.773  792.56 113.491     791 187.242     790
  226.84  787.27 233.416  786.54 246.568   783.8 256.043  782.68 266.296  782.24
 279.449  782.68 286.025  783.45 299.248  785.14 319.188  788.67 326.047  789.45
 346.624  790.53 380.918  791.16 401.495  791.95 415.142  792.83 442.578  795.24
 449.508   796.8 456.367  799.26 463.296  803.06 490.874  821.06  532.31  847.61
#Mann= 3 , 0 , 0
       0      .1       0 246.568    .045       0 286.025      .1       0
Bank Sta=246.568,286.025
XS Rating Curve= 0 ,0
Skew Angle= 45
Exp/Cntr=0.3,0.1

Type RM Length L Ch R = 1 ,82203.5 ,434.7,427.1,419.5
XS GIS Cut Line= 3
     1879066.484      494843.743     1878994.969      495182.635
     1878956.068      495318.049
#Sta/Elev= 25
       0  868.17    19.2  855.23    48.1  836.13    67.4  823.48      77  815.22
    86.6  800.36    96.2  786.56   105.8  782.38   115.4  783.12   125.1  785.12
   134.7  787.25   144.3  788.95   153.9  790.03   163.6  790.49   230.9  791.38
     279   791.9   307.9  792.12   317.5  792.41   355.8  794.96   365.1  795.61
   374.5  796.58   383.9  798.54   393.3  802.05   449.7  827.94   487.2  845.36
#Mann= 3 , 0 , 0
       0      .1       0    96.2    .045       0   125.1      .1       0
Bank Sta=96.2,125.1
XS Rating Curve= 0 ,0
Exp/Cntr=0.3,0.1

Type RM Length L Ch R = 1 ,81776.5 ,478.2,491.1,503.8
XS GIS Cut Line= 4
     1878620.095      494851.382      1878614.54      494925.688
     1878636.762      495096.521     1878618.706      495264.577
#Sta/Elev= 27
       0  831.93    27.9  818.34    55.9  805.35    74.5  796.94    84.1  792.46
    93.6   787.5   103.2  783.15   112.8  781.31   122.4   781.8   129.2 782.616
   131.9  782.94   141.5  784.32   151.1  785.49   160.6  786.51   170.2  786.96
   179.8  786.34   189.4  785.86   198.9  786.71   218.1  790.17   237.2   793.3
   293.7  801.91   321.9  805.99   359.5  811.01   378.2  813.82     397  817.02
   406.4  818.76   415.8  820.68
#Mann= 3 , 0 , 0
       0      .1       0   103.2    .045       0   129.2      .1       0
Bank Sta=103.2,129.2
XS Rating Curve= 0 ,0
Exp/Cntr=0.3,0.1