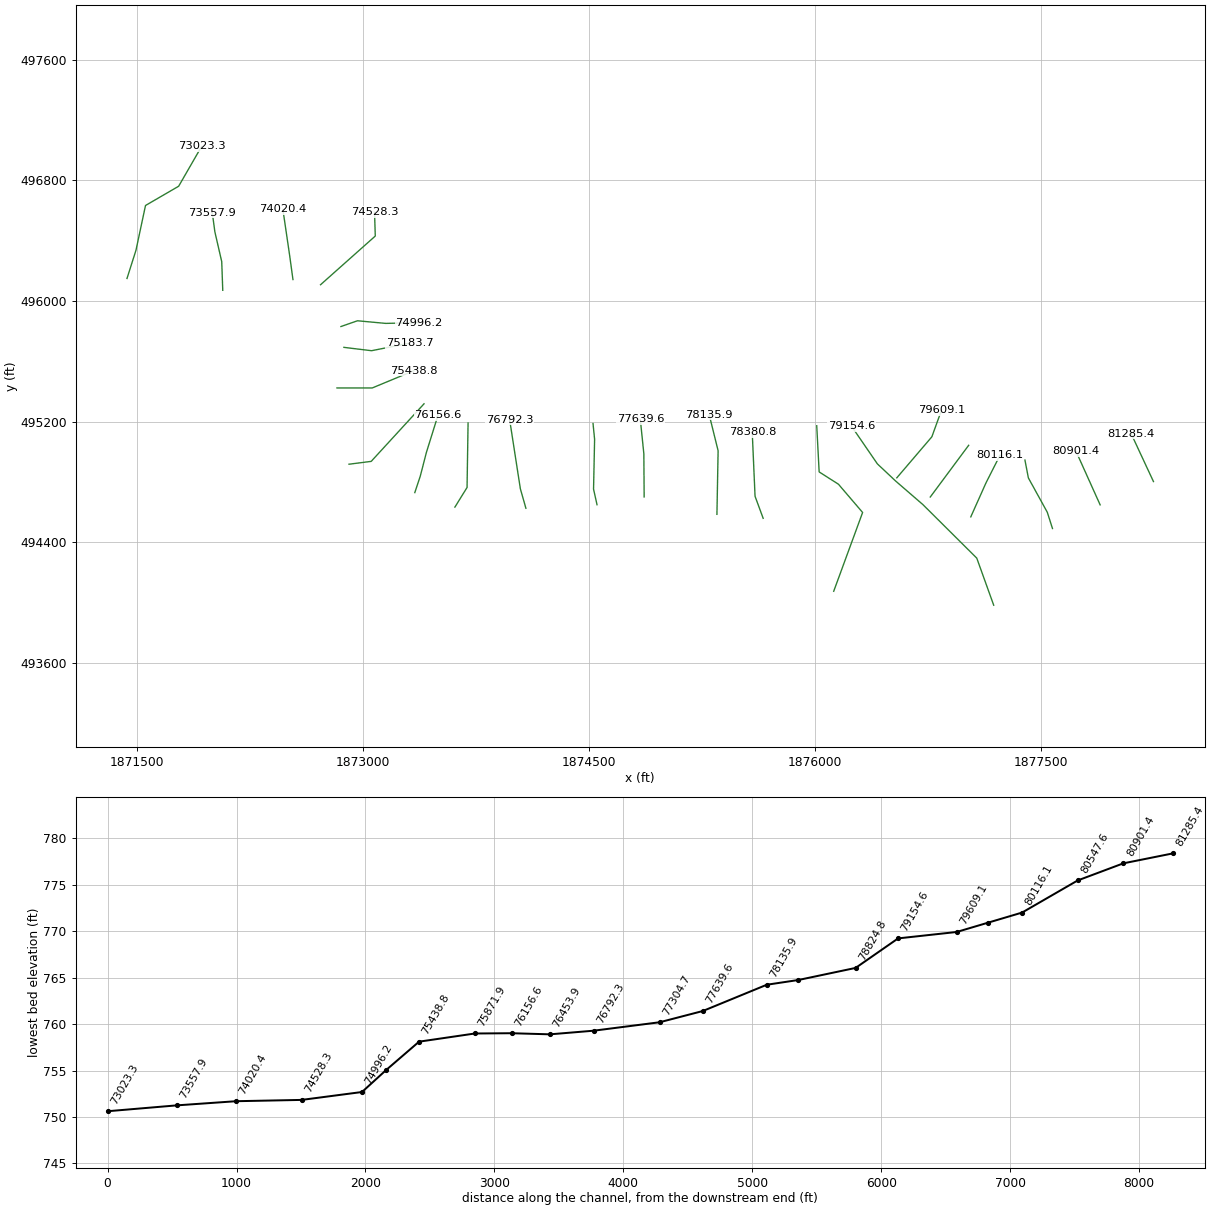
HEC-RAS study BLUECR.prj: BLUECR

--- BLUECR.g01 (geometry) --- (continued)

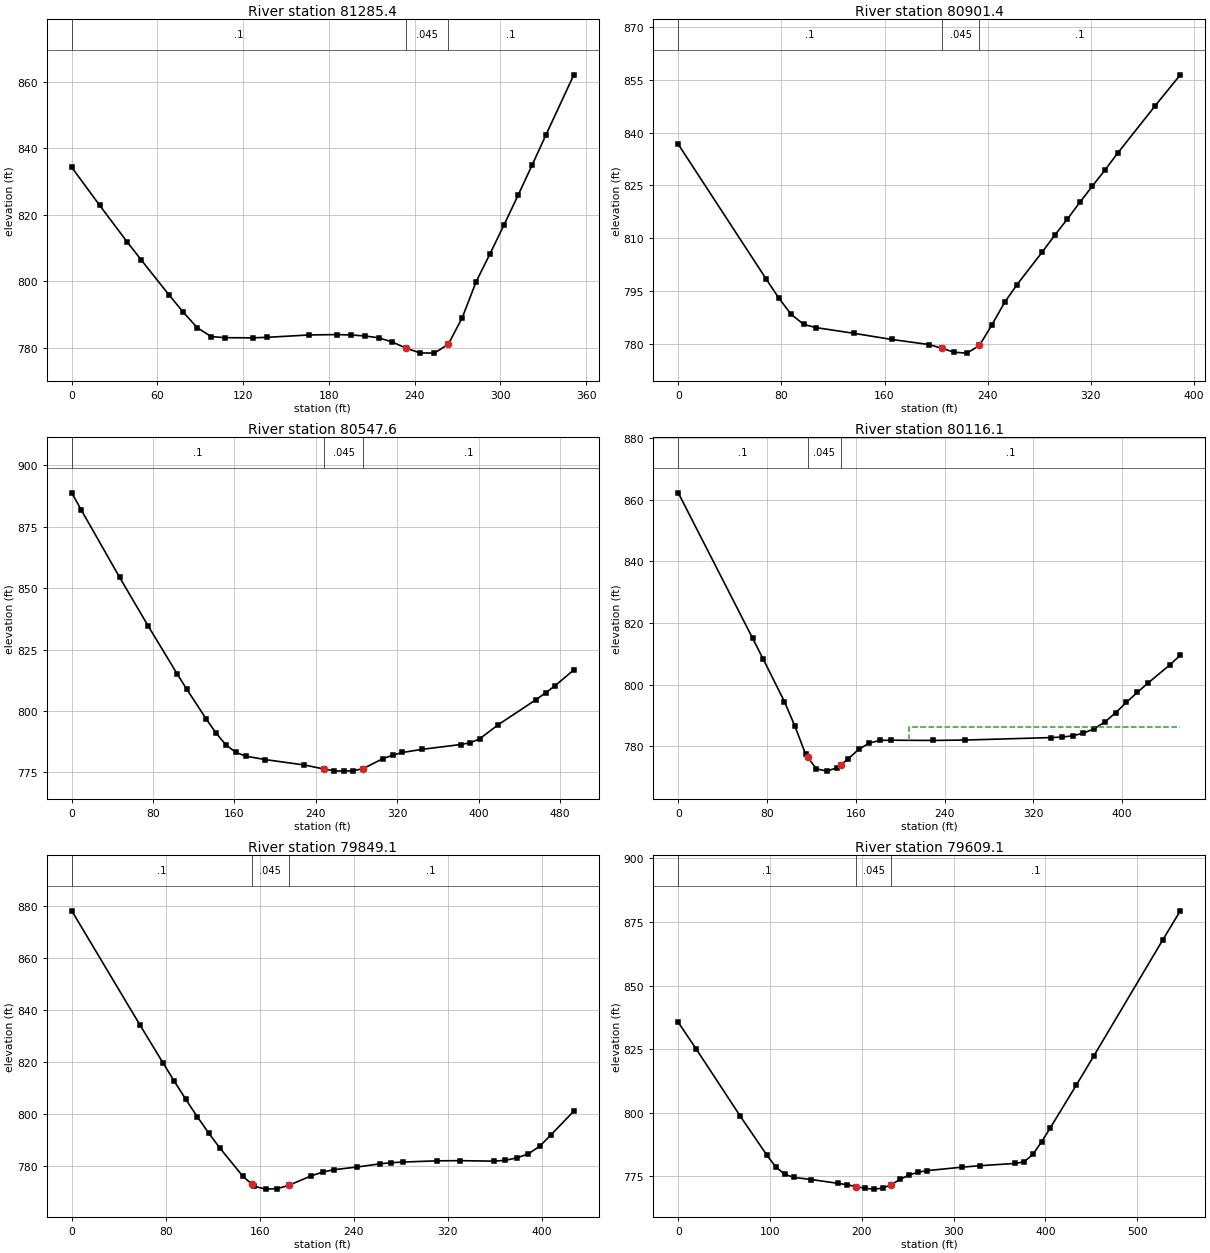
Type RM Length L Ch R = 1 ,81285.4 ,384.2,384,383.6
XS GIS Cut Line= 2
     1878245.443       494802.25     1878097.005      495120.827
#Sta/Elev= 29
       0  834.24    19.5  822.85      39   811.7    48.8  806.31    68.3  795.77
    78.1  790.68    87.9     786    97.6  783.36   107.4  783.02   126.9  782.98
   136.7  783.13     166  783.84   185.5  783.96   195.3  783.84     205  783.55
   214.8     783   224.5  781.71   234.3  779.83   243.9  778.44   253.8  778.38
   263.6  781.04   273.4  789.07   283.1  799.87   292.9  808.33   302.6  816.93
   312.4  825.81   322.2  834.86   331.9  843.95   351.5  862.08
#Mann= 3 , 0 , 0
       0      .1       0   234.3    .045       0   263.6      .1       0
Bank Sta=234.3,263.6
XS Rating Curve= 0 ,0
Exp/Cntr=0.3,0.1

Type RM Length L Ch R = 1 ,80901.4 ,351.9,353.7,355.5
XS GIS Cut Line= 2
     1877891.554      494647.667     1877731.554      495002.667
#Sta/Elev= 25
       0   836.7    68.1  798.44    77.9  793.02    87.6  788.32    97.4  785.47
   107.1  784.55   136.3  782.94   165.5   781.2   194.7  779.74   204.4  778.68
   214.2  777.55   223.9  777.31   233.6  779.48   243.4  785.42   253.1  791.73
   262.8  796.81   282.3  806.05     292  810.83   301.8  815.43   311.5   820.2
   321.2  824.82     331  829.38   340.7  834.12   369.9  847.64   389.4  856.44
#Mann= 3 , 0 , 0
       0      .1       0   204.4    .045       0   233.6      .1       0
Bank Sta=204.4,233.6
XS Rating Curve= 0 ,0
Exp/Cntr=0.3,0.1

Type RM Length L Ch R = 1 ,80547.6 ,452.4,431.6,410.3
XS GIS Cut Line= 4
     1877575.165         494491.      1877540.72      494598.778
     1877415.165      494826.556     1877392.387      494944.889
#Sta/Elev= 30
       0  888.81     9.4  881.78    47.1  854.35    75.4  834.39   103.7  815.03
   113.2  808.73   132.4  796.59     142  790.87   151.7  786.11   161.3  783.11
     171  781.58   190.2  780.17   228.7  777.97     248  776.33   257.5   775.6
   267.3  775.47   276.9  775.64   286.5  776.49   305.8  780.52   315.4  781.93
   325.1  783.06   344.3  784.33   382.5  786.31   391.8  787.03     401   788.6
   419.6  794.44   456.7  804.63   465.9  807.38   475.2  810.23   493.7  816.72
#Mann= 3 , 0 , 0
       0      .1       0     248    .045       0   286.5      .1       0
Bank Sta=248,286.5
XS Rating Curve= 0 ,0
Exp/Cntr=0.3,0.1

Type RM Length L Ch R = 1 ,80116.1 ,271.9,267,262.1
XS GIS Cut Line= 3
     1877032.971      494568.195     1877134.668      494795.241
     1877226.901      494976.903
#Sta/Elev= 30
       0  862.17      67  815.08    76.6  808.29    95.7  794.55   105.2  786.55
   114.8  777.47   116.5776.6385   124.4  772.77     134  772.01   143.5  773.15
   146.5774.0282   153.1  775.96   162.7  779.08   172.2  781.11   181.8  781.96
   191.4  782.03   229.6  781.95   258.5  782.08   336.1  782.88   345.8  783.04
   355.5  783.44   365.2  784.33   374.9  785.72   384.6  787.96   394.3  790.96
     404  794.31   413.7  797.52   423.4  800.55   442.8  806.35   452.5  809.55
#Mann= 3 , 0 , 0
       0      .1       0   116.5    .045       0   146.5      .1       0
#XS Ineff= 2 , 0
                          207.88          786.35
Permanent Ineff=
       F       F
Bank Sta=116.5,146.5
XS Rating Curve= 0 ,0
Exp/Cntr=0.3,0.1

Type RM Length L Ch R = 1 ,79849.1 ,241.6,240,238.5
XS GIS Cut Line= 2
     1876764.054       494699.82     1877018.915      495042.875
#Sta/Elev= 30
       0  878.04    58.3   833.9    77.7  819.48    87.4  812.37    97.1  805.44
   106.8  798.82   116.6  792.45   126.3   786.6   145.7  775.83   153.6772.7189
   155.4  772.01   165.1  770.91   174.8  771.09   184.5  772.33     204  776.05
   213.7  777.47   223.4   778.4   242.8  779.42   262.2  780.64     272  781.09
   281.7  781.33   310.8   781.8   330.2  781.87   359.4  781.68   369.1     782
   378.8  782.94   388.5  784.44   398.2  787.37   407.9  791.78   427.4  800.96
#Mann= 3 , 0 , 0
       0      .1       0   153.6    .045       0   184.5      .1       0
Bank Sta=153.6,184.5
XS Rating Curve= 0 ,0
Exp/Cntr=0.3,0.1

Type RM Length L Ch R = 1 ,79609.1 ,424.5,454.5,484
XS GIS Cut Line= 3
     1876542.033      494827.188     1876774.608       495099.21
     1876839.054      495276.903
#Sta/Elev= 30
       0  835.58    19.4  825.14    67.7  798.56    96.7   783.2   106.4  778.59
   116.1  775.73   125.8  774.55   145.1  773.68   174.1   772.2   183.8  771.63
   193.5  770.94   203.1  770.27   212.8  769.92   222.5  770.26   232.2  771.69
   241.8   773.8   251.5  775.48   261.2  776.57   270.8  777.19   309.5  778.57
   328.9  779.14   367.3  780.04   376.8  780.66   386.2  783.58   395.7  788.47
   405.2  793.98   433.5  810.78   452.4  822.15     528   868.1   546.9  879.41
#Mann= 3 , 0 , 0
       0      .1       0   193.5    .045       0   232.2      .1       0
Bank Sta=193.5,232.2
XS Rating Curve= 0 ,0
Exp/Cntr=0.3,0.1

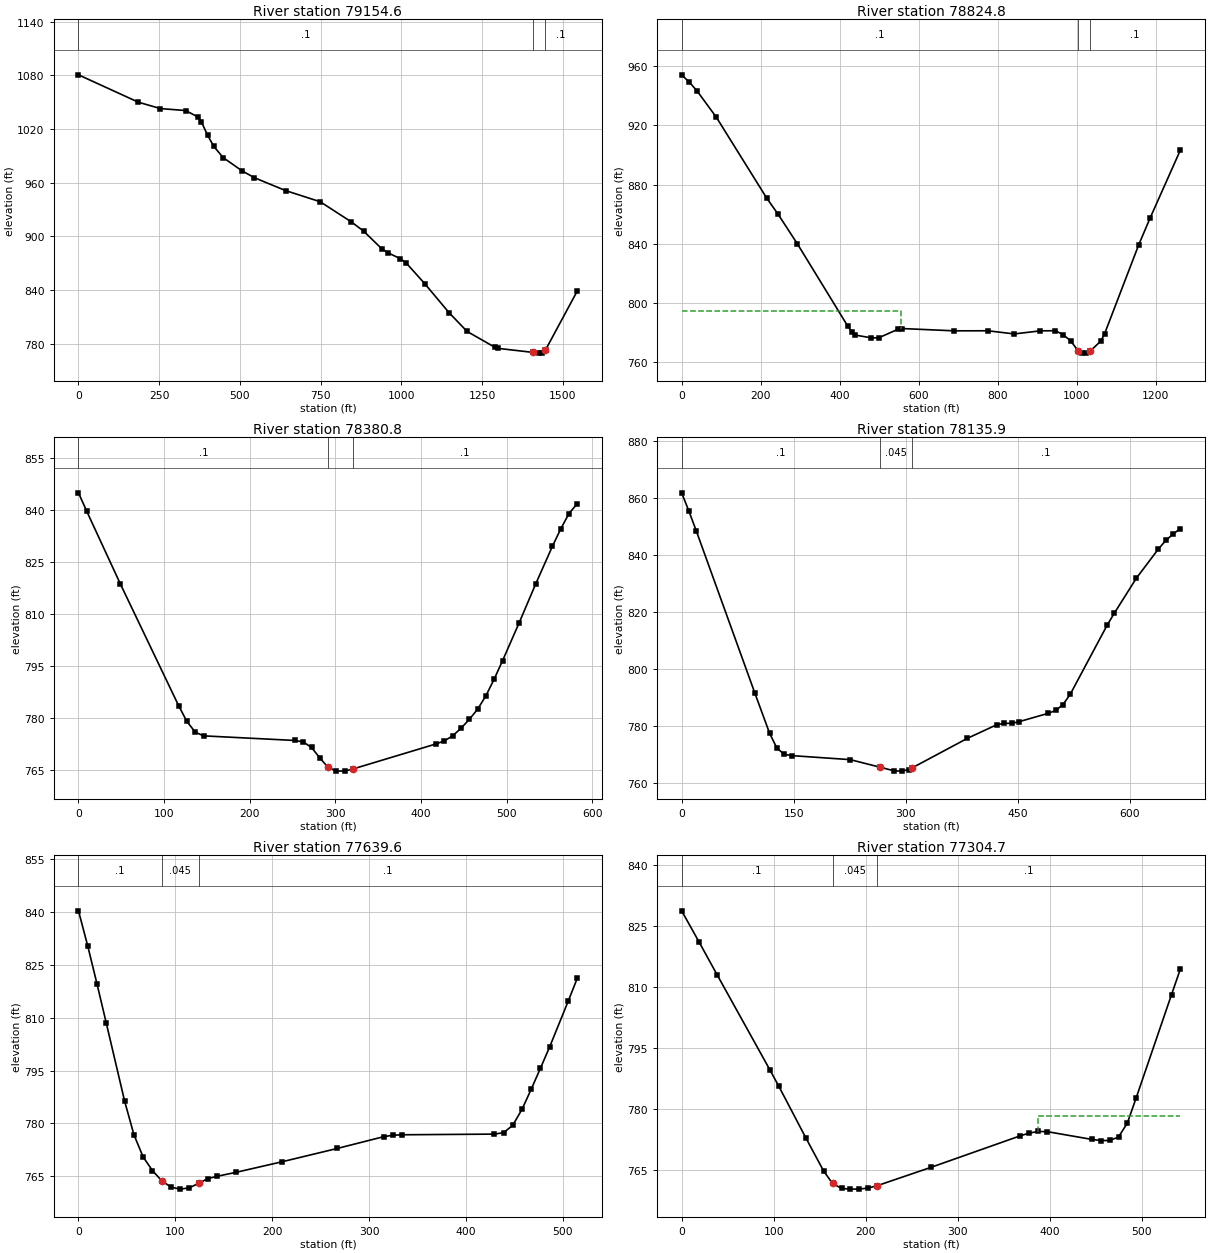
Type RM Length L Ch R = 1 ,79154.6 ,342.3,329.8,317.4
XS GIS Cut Line= 6
       1877185.1      493982.084      1877072.61      494294.578
      1876715.23      494649.421     1876536.049      494804.109
     1876413.133      494919.387      1876240.91      495170.082
#Sta/Elev= 30
       0 1080.64   185.6 1049.99     254 1042.86   332.1 1040.68   370.9 1033.27
   380.6 1028.16   399.9 1013.03   419.3 1000.48   448.3  987.96   506.4  973.27
   545.2  965.46     642  951.04   748.6  938.65   845.2  916.08   883.1  905.78
   939.9  885.85   958.8  881.47   996.7  874.97  1015.6   869.9  1072.5  846.99
  1147.4  814.67  1203.5  793.55    1290  775.74  1299.8  774.54  1407.8  770.05
  1427.4  769.23  1437.2  769.77  1444.9772.3244    1447  773.02  1545.1  838.79
#Mann= 3 , 0 , 0
       0      .1       0  1407.8    .045       0  1444.9      .1       0
Bank Sta=1407.8,1444.9
XS Rating Curve= 0 ,0
Exp/Cntr=0.3,0.1

Type RM Length L Ch R = 1 ,78824.8 ,443.9,443.9,443.5
XS GIS Cut Line= 5
     1876123.052      494074.653     1876314.979      494597.286
     1876154.562      494784.671     1876026.461      494866.242
     1876010.465      495172.691
#Sta/Elev= 30
       0  954.16    19.5  949.17    39.1  943.23    87.9  925.43   214.9  870.97
   244.2  859.86     293  839.84     420  784.44   429.8  780.62   439.6  778.24
   478.6  776.44   498.2  776.35     547  782.14   556.8  782.68   689.6  781.12
     775  781.16   841.4  779.03   907.8  781.11   945.8   781.2   964.9  778.57
   984.1  774.42  1003.2  767.64  1012.8  766.05  1022.4  766.09  1033.2767.2975
  1060.8  774.23  1070.4  779.29  1156.7  839.37  1185.4   857.4  1262.2  903.44
#Mann= 3 , 0 , 0
       0      .1       0  1003.2    .045       0  1033.2      .1       0
#XS Ineff= 2 , 0
          555.13   794.2
Permanent Ineff=
       F       F
Bank Sta=1003.2,1033.2
XS Rating Curve= 0 ,0
Exp/Cntr=0.3,0.1

Type RM Length L Ch R = 1 ,78380.8 ,246.2,244.9,243.5
XS GIS Cut Line= 3
     1875654.799      494558.623      1875600.98      494704.873
      1875582.23      495131.262
#Sta/Elev= 30
       0  844.91     9.7  839.57    48.7  818.77   116.9  783.64   126.6  779.07
   136.4  775.97   146.1  774.91   252.8  773.58   262.5  773.16   272.2  771.56
   281.9  768.54   291.6  765.81   301.3  764.79     311  764.75   320.7  765.38
   417.7  772.59   427.4  773.47   437.1  774.93   446.8   777.1   456.5  779.66
   466.2  782.59   475.9  786.47   485.6   791.3   495.3  796.56   514.7  807.48
   534.1  818.72   553.5  829.49   563.2  834.49   572.9  838.95   582.6  841.81
#Mann= 3 , 0 , 0
       0      .1       0   291.6    .045       0   320.7      .1       0
Bank Sta=291.6,320.7
XS Rating Curve= 0 ,0
Exp/Cntr=0.3,0.1

Type RM Length L Ch R = 1 ,78135.9 ,495.7,496.3,496.9
XS GIS Cut Line= 3
     1875347.982      494584.936     1875355.838      495006.742
     1875296.722      495245.373
#Sta/Elev= 30
       0  861.93     9.8  855.43    19.6  848.55    98.1  791.55   117.7  777.54
   127.5  772.31   137.4  770.14   147.2  769.69   225.7  768.27   264.9  765.66
   284.5  764.34   294.3  764.24   304.1   764.8   307.8765.2784   382.6  775.77
   421.9  780.54   431.7     781   441.6  781.03   451.4  781.58   490.7  784.53
   500.6  785.54   510.4  787.57   520.2  791.24   569.4   815.4   579.2   819.7
   608.7  831.98   638.2  842.23   648.1  845.22   657.9  847.48   667.7  849.39
#Mann= 3 , 0 , 0
       0      .1       0   264.9    .045       0   307.8      .1       0
Bank Sta=264.9,307.8
XS Rating Curve= 0 ,0
Exp/Cntr=0.3,0.1

Type RM Length L Ch R = 1 ,77639.6 ,335.3,334.9,334
XS GIS Cut Line= 3
      1874864.93      494700.332     1874862.847       494986.79
     1874839.484      495214.255
#Sta/Elev= 30
       0  840.22     9.6  830.22    19.1  819.55    28.6  808.55    47.7  786.27
    57.3  776.78    66.8   770.5    76.4  766.66    85.9  763.79    95.5  761.99
     105  761.41   114.6  761.78   124.1  763.08   133.7  764.39   143.2  765.05
   162.3  766.14   210.1  769.15   267.4  772.94     315  776.25   324.6  776.67
   334.1   776.8   429.4  776.99   438.9  777.39   448.4  779.46     458  784.01
   467.5   789.7     477  795.62   486.6  801.72   505.6  814.57   515.1  821.14
#Mann= 3 , 0 , 0
       0      .1       0    85.9    .045       0   124.1      .1       0
Bank Sta=85.9,124.1
XS Rating Curve= 0 ,0
Exp/Cntr=0.3,0.1

Type RM Length L Ch R = 1 ,77304.7 ,508.3,512.4,516.2
XS GIS Cut Line= 4
       1874552.1       494648.67     1874529.014      494751.724
     1874536.039      495082.215     1874525.559      495187.382
#Sta/Elev= 26
       0  828.64    19.2  820.86    38.4  812.96      96  789.47   105.6  785.47
   134.8  772.85   154.2  764.67   163.9  761.59   173.7  760.38   183.4   760.2
   193.1  760.22   202.8  760.47   212.6  761.06   270.9  765.56   368.1  773.33
   377.8     774   387.6  774.38   397.3  774.33   445.8  772.42   455.4  772.15
     465  772.16   474.6  773.02   484.2  776.46   493.8  782.66   532.2  808.05
   541.9   814.4
#Mann= 3 , 0 , 0
       0      .1       0   163.9    .045       0   212.6      .1       0
#XS Ineff= 2 , 0
                          387.36          778.27
Permanent Ineff=
       F       F
Bank Sta=163.9,212.6
XS Rating Curve= 0 ,0
Exp/Cntr=0.3,0.1

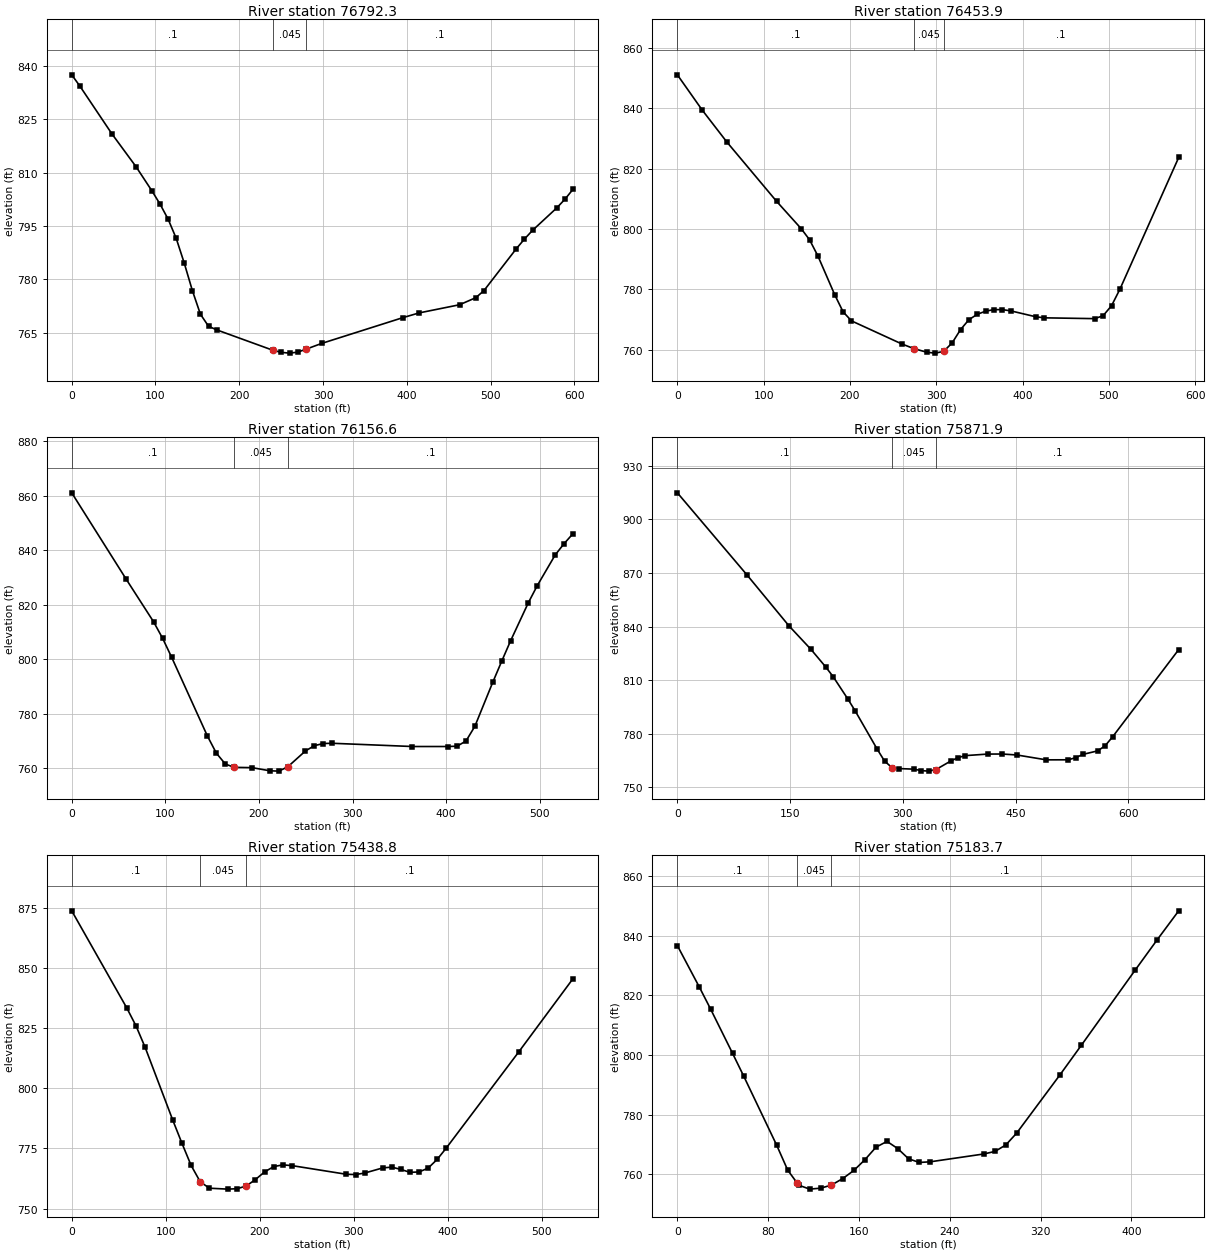
Type RM Length L Ch R = 1 ,76792.3 ,342.1,338.4,334.4
XS GIS Cut Line= 3
     1874080.062      494625.144     1874043.256      494754.311
     1873972.076      495212.991
#Sta/Elev= 30
       0  837.44     9.6  834.32      48  820.85    76.8  811.63    95.9  804.79
   105.5  801.11   115.1  796.89   124.7  791.54   134.3  784.59     144  776.87
   153.6  770.23   163.3  766.84     173  765.83   240.7  760.05   250.4   759.5
     260  759.29   269.7  759.56   279.4  760.37   298.7  762.04   395.4  769.26
   414.7  770.58   463.1  772.88   482.4  774.86   492.1  776.84   530.8  788.62
   540.5  791.33   550.1  793.76   579.1  800.08   588.8  802.51   598.5  805.31
#Mann= 3 , 0 , 0
       0      .1       0   240.7    .045       0   279.4      .1       0
Bank Sta=240.7,279.4
XS Rating Curve= 0 ,0
Exp/Cntr=0.3,0.1

Type RM Length L Ch R = 1 ,76453.9 ,302.6,297.3,291.9
XS GIS Cut Line= 3
     1873608.725      494632.794     1873689.421      494763.017
      1873696.19      495190.711
#Sta/Elev= 30
       0  851.07    28.7  839.43    57.4   828.8   114.9   809.2   143.6  800.09
   153.2  796.44   162.9  791.06   182.4  778.21   192.1  772.56   201.8  769.58
   260.1  761.94   274.3760.3772   289.3  759.18     299   758.9   308.7  759.49
   318.5  762.31   328.2   766.7   337.9  769.98   347.6  771.77   357.4  772.81
   367.1  773.31   376.8   773.3   386.5  772.89   415.7  770.92   425.4  770.59
   483.7  770.32   493.4  771.29   503.2  774.61   512.9  780.09     581   823.7
#Mann= 3 , 0 , 0
       0      .1       0   274.3    .045       0   308.7      .1       0
Bank Sta=274.3,308.7
XS Rating Curve= 0 ,0
Exp/Cntr=0.3,0.1

Type RM Length L Ch R = 1 ,76156.6 ,295.8,284.7,273.7
XS GIS Cut Line= 4
     1873342.659      494729.142     1873379.326      494839.697
     1873419.757      494996.351     1873496.548      495241.919
#Sta/Elev= 30
       0  861.03    58.2  829.36    87.4  813.78    97.1  807.71   106.8  800.71
     145  771.85   154.5  765.61   164.1  761.62   173.6   760.4   192.6   760.3
   211.6  759.15   221.2  759.02   230.7  760.56   249.7  766.42   259.2  768.35
   268.8  769.14   278.3  769.23     364  768.04   402.2  768.04   411.7  768.16
   421.2  770.05   430.7  775.45   449.8  791.58   459.3  799.25   468.8  806.74
   487.9   820.8   497.4  827.04   516.5  838.25     526   842.4   535.6  846.09
#Mann= 3 , 0 , 0
       0      .1       0   173.6    .045       0   230.7      .1       0
Bank Sta=173.6,230.7
XS Rating Curve= 0 ,0
Exp/Cntr=0.3,0.1

Type RM Length L Ch R = 1 ,75871.9 ,451.7,433.1,414.2
XS GIS Cut Line= 3
     1872905.913      494917.378     1873053.135      494936.128
     1873403.829      495318.072
#Sta/Elev= 30
       0  914.92    92.8  868.82   148.4  840.41   177.8  827.17   197.3  817.38
   207.1     812   226.7  799.45   236.5  792.76   265.8   771.3   275.6  764.63
   285.4  760.99   295.2  760.42   314.7  760.09   324.5  759.28   334.3  758.99
   344.1   759.9   363.6  764.64   373.4  766.57   383.2  767.68   412.6  768.54
   432.1  768.58   451.7  768.03   490.8  765.31   520.2  765.34     530  766.57
   539.8   768.4   559.3  770.36   569.1  773.24   578.9  778.16   666.9  827.08
#Mann= 3 , 0 , 0
       0      .1       0   285.4    .045       0   344.1      .1       0
Bank Sta=285.4,344.1
XS Rating Curve= 0 ,0
Exp/Cntr=0.3,0.1

Type RM Length L Ch R = 1 ,75438.8 ,257.8,255.1,252.4
XS GIS Cut Line= 3
     1872825.913      495423.142     1873060.288      495423.142
     1873336.329      495537.725
#Sta/Elev= 30
       0  873.63    58.6  833.28    68.4  825.84    78.1  816.93   107.4  786.81
   117.2  777.17     127  767.93   136.7  761.13   146.5  758.49     166  758.11
   175.8  758.28   185.6   759.4   195.3  762.06   205.1  765.25   214.8  767.46
   224.6  768.18   234.4  767.86   292.2  764.27   301.9  764.16   311.5  764.78
   330.8  766.92   340.4  767.24   350.1  766.29   359.7  765.08   369.4  765.24
     379  766.82   388.6  770.42   398.3  775.13   475.4  815.05   533.2   845.5
#Mann= 3 , 0 , 0
       0      .1       0   136.7    .045       0   185.6      .1       0
Bank Sta=136.7,185.6
XS Rating Curve= 0 ,0
Exp/Cntr=0.3,0.1

Type RM Length L Ch R = 1 ,75183.7 ,186.8,187.5,188
XS GIS Cut Line= 3
     1872871.989      495692.378     1873055.322      495670.156
     1873307.406      495720.156
#Sta/Elev= 30
       0  836.69    19.4  822.76    29.2  815.48    48.6   800.6    58.3  793.06
    87.5  769.79    97.2  761.44   105.7757.0148   106.9  756.39   116.6  755.06
   126.4  755.39   135.7 756.416   145.8  758.62   155.5  761.33   165.2   764.9
     175  769.12   184.7  771.06   194.2  768.64   203.7  765.23   213.2     764
   222.8  764.22   270.3  766.86   279.9  767.71   289.4  769.88   298.9  773.82
     337  793.32     356  803.32   403.6  828.61   422.6  838.57   441.7  848.35
#Mann= 3 , 0 , 0
       0      .1       0   105.7    .045       0   135.7      .1       0
Bank Sta=105.7,135.7
XS Rating Curve= 0 ,0
Exp/Cntr=0.3,0.1

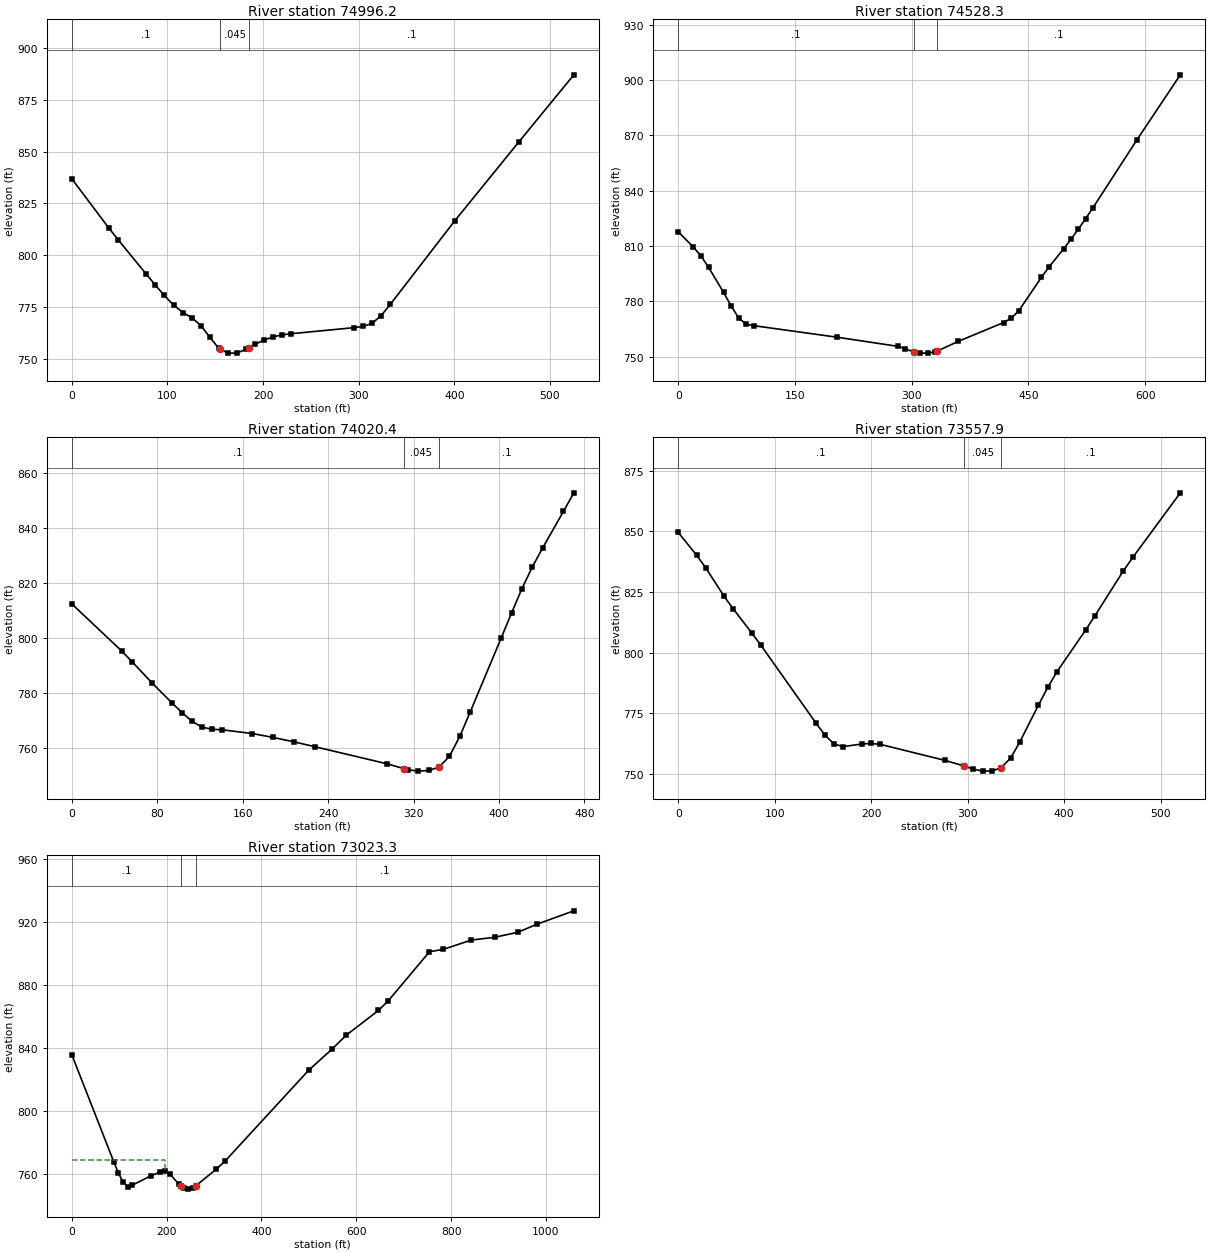
Type RM Length L Ch R = 1 ,74996.2 ,449.1,467.9,486.1
XS GIS Cut Line= 4
     1872852.276      495830.507     1872961.998      495868.702
     1873149.498      495851.341     1873369.915      495856.063
#Sta/Elev= 30
       0  836.96    38.7  813.17    48.4  807.52    77.4  791.15    87.1  785.72
    96.8  780.54   106.5  775.92   116.2   772.3   125.6  769.79     135  766.02
   144.4  760.33   153.8  755.03   155.1754.7095   163.3  752.69   172.7  752.72
   182.1  754.54   185.1755.3027   191.5  756.93   200.9  758.94   210.3  760.55
   219.8   761.5   229.2  762.06   295.1     765   304.5  765.58   314.1  767.11
   323.6  770.87   333.2  776.33   400.3  816.53   467.4   854.7     525  887.17
#Mann= 3 , 0 , 0
       0      .1       0   155.1    .045       0   185.1      .1       0
Bank Sta=155.1,185.1
XS Rating Curve= 0 ,0
Exp/Cntr=0.3,0.1

Type RM Length L Ch R = 1 ,74528.3 ,485.5,507.9,530.4
XS GIS Cut Line= 3
     1872717.033      496107.764     1873080.228      496430.681
     1873075.366      496589.709
#Sta/Elev= 30
       0  817.72    19.4  809.44    29.2  804.61    38.9  798.46    58.3   784.8
      68  777.45    77.8  770.82    87.5   767.5    97.2  766.74   204.1  760.48
   281.9  755.55   291.6  754.29   302.5752.4617     311  751.84   320.8  751.87
   330.5  752.54   332.5752.8967   359.6  758.19     418  768.44   427.7  770.76
   437.4  774.73   466.6  792.98   476.3  798.58   495.4  808.58   504.7  813.76
   514.1  819.17   523.4  824.82   532.8  830.74   588.9  867.34   645.1  902.94
#Mann= 3 , 0 , 0
       0      .1       0   302.5    .045       0   332.5      .1       0
Bank Sta=302.5,332.5
XS Rating Curve= 0 ,0
Exp/Cntr=0.3,0.1

Type RM Length L Ch R = 1 ,74020.4 ,460.6,462.5,464.3
XS GIS Cut Line= 3
     1872533.873      496141.966     1872512.172      496299.952
     1872467.033      496607.244
#Sta/Elev= 30
       0  812.41    46.9  795.24    56.3  791.48      75  783.77    93.8  776.47
   103.2  772.95   112.6  769.78     122  767.65   131.3  766.89   140.7  766.71
   169.2  765.33   188.6  763.92     208  762.33   227.4  760.59   295.4  754.34
   310.7752.6281   314.8  752.18   324.5   751.7   334.2  751.94   343.9  753.16
   353.6  757.07   363.3  764.29     373   773.1   402.1  800.05   411.8  809.12
   421.5  817.94   431.2  825.79   440.9  832.72   460.4  845.98   470.1  852.71
#Mann= 3 , 0 , 0
       0      .1       0   310.7    .045       0   343.9      .1       0
Bank Sta=310.7,343.9
XS Rating Curve= 0 ,0
Exp/Cntr=0.3,0.1

Type RM Length L Ch R = 1 ,73557.9 ,544.5,534.7,524.8
XS GIS Cut Line= 4
     1872067.901      496070.785     1872061.091      496260.774
     1872015.631      496458.079     1871998.457      496584.674
#Sta/Elev= 30
       0  849.62      19  840.26    28.5  835.02    47.5   823.3      57  818.11
      76  808.29    85.6  803.16   142.6  771.12   152.1  766.06   161.6  762.38
   171.1  761.36   190.1  762.42   199.8  762.65   209.4  762.28   276.9  755.63
   296.1753.3824   305.8  752.08   315.4  751.25   325.1  751.29   334.7  752.67
   344.4   756.6     354  763.29   373.3  778.48   382.9  785.75   392.6  792.29
   422.1  809.32   431.9  815.32   461.4  833.86   471.2  839.38   520.3  865.93
#Mann= 3 , 0 , 0
       0      .1       0   296.1    .045       0   334.7      .1       0
Bank Sta=296.1,334.7
XS Rating Curve= 0 ,0
Exp/Cntr=0.3,0.1

Type RM Length L Ch R = 1 ,73023.3 ,453.6,454.3,454.8
XS GIS Cut Line= 5
     1871432.253      496149.315     1871491.975      496336.815
      1871555.17      496633.343      1871775.17       496760.99
     1871927.253      497024.706
#Sta/Elev= 30
       0  835.92    88.6  767.92    98.4  760.84   108.2  754.98   118.1  752.28
   127.9  753.17   167.3  759.14   186.9  761.52   196.8  761.89   206.6  760.28
   226.1  753.68   231.1752.4759   235.9  751.32   245.7  750.62   255.5   751.4
   261.1752.6066   304.4  763.18   323.9  768.61     500  826.12   548.9   839.4
   578.2  848.04   646.7  863.91   666.3  869.61   754.3   901.1   783.8  902.65
   842.7  908.51   891.8  910.26   940.9  913.46   980.2  918.47  1058.7  927.03
#Mann= 3 , 0 , 0
       0      .1       0   231.1    .045       0   261.1      .1       0
#XS Ineff= 2 , 0
           196.7  769.34
Permanent Ineff=
       F       F
Bank Sta=231.1,261.1
XS Rating Curve= 0 ,0
Exp/Cntr=0.3,0.1