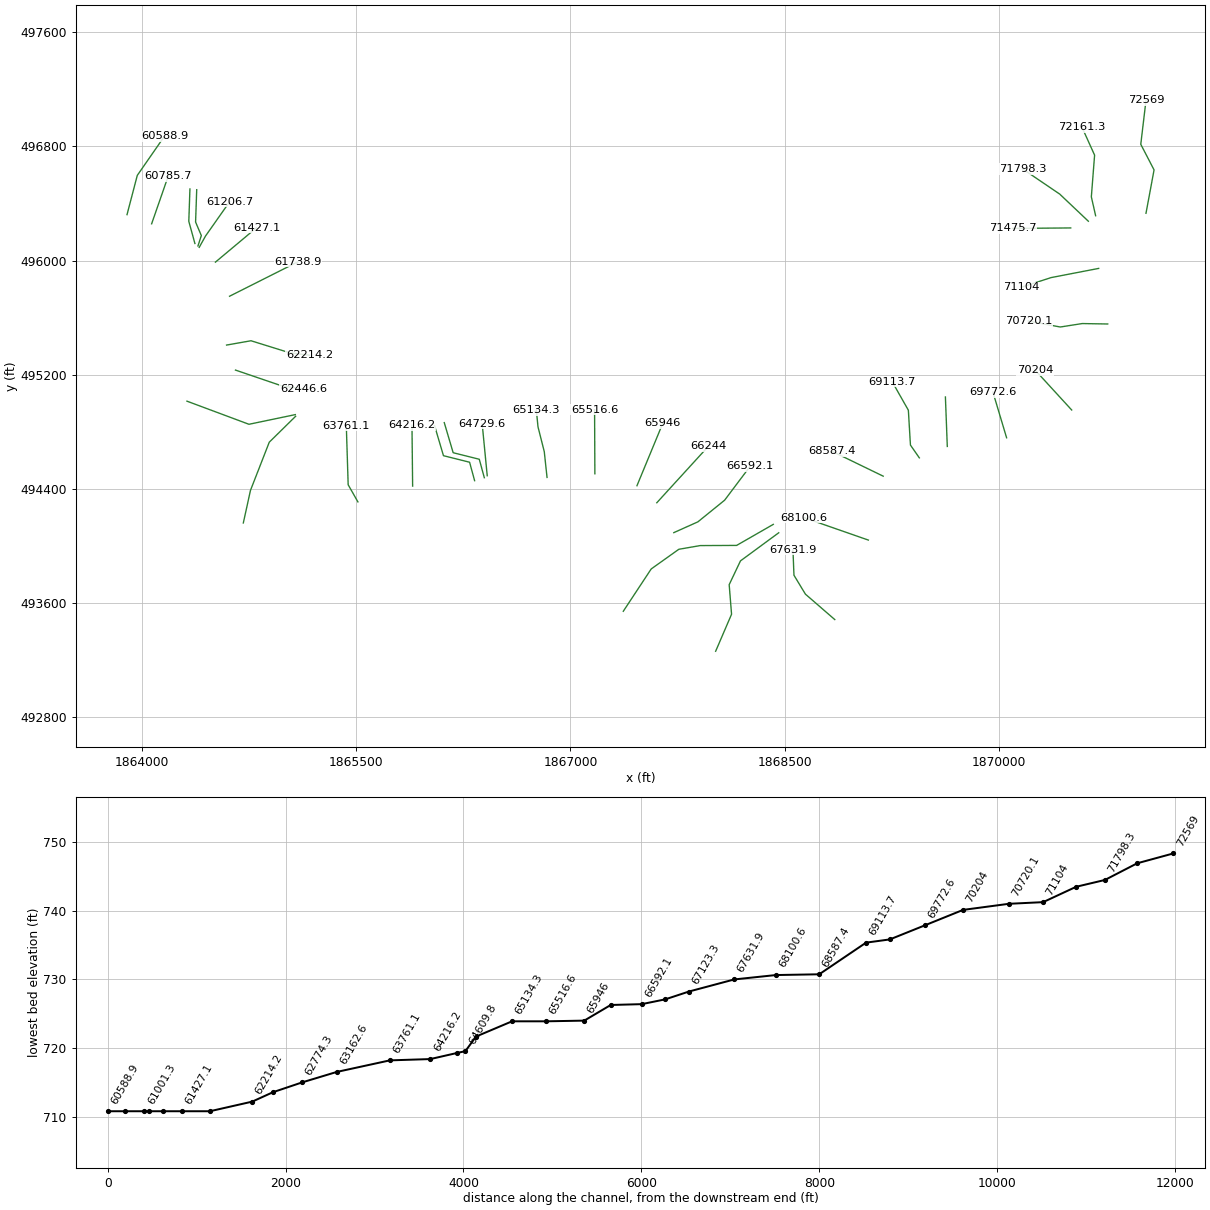
HEC-RAS study BLUECR.prj: BLUECR

--- BLUECR.g01 (geometry) --- (continued)

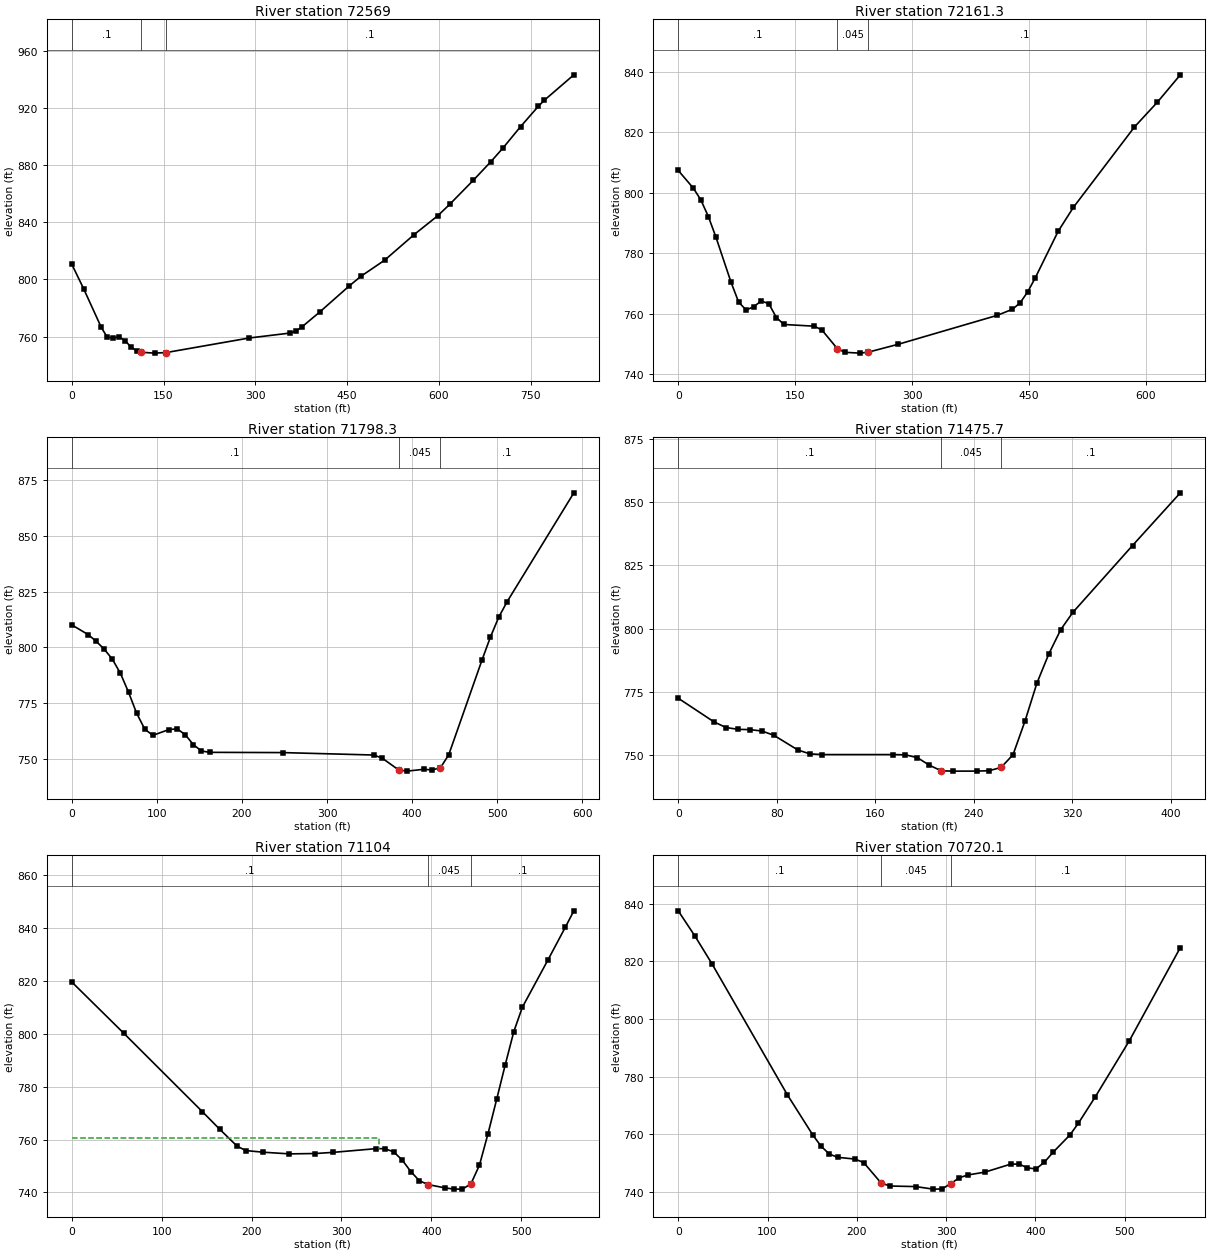
Type RM Length L Ch R = 1 ,72569   ,405.3,407.7,410.1
XS GIS Cut Line= 4
     1871030.427      496330.863      1871086.97       496634.86
      1870993.92      496814.289     1871030.378      497121.581
#Sta/Elev= 30
       0  810.67    19.3  793.56    48.3  766.34      58  759.49    67.6  759.06
    77.3  759.78      87  757.15    96.6  752.72   106.3  749.81   113.8748.9518
   135.3  748.36   154.6  748.78   289.9  758.95   357.3  762.44     367  763.93
   376.6  766.83   405.5  777.21   453.6  795.43   472.8  802.22   511.3  813.41
   559.7   831.4   598.4  844.63   617.7  852.54   656.4  869.43   685.4   882.6
   704.7  891.95   733.8  907.08   762.8  921.31   772.4  925.46   820.8  943.33
#Mann= 3 , 0 , 0
       0      .1       0   113.8    .045       0   154.6      .1       0
Bank Sta=113.8,154.6
XS Rating Curve= 0 ,0
Exp/Cntr=0.3,0.1

Type RM Length L Ch R = 1 ,72161.3 ,338.9,363,386.7
XS GIS Cut Line= 4
     1870677.718      496313.919     1870647.718      496446.141
     1870670.496      496738.363     1870581.781      496934.613
#Sta/Elev= 30
       0  807.37    19.4  801.51      29  797.62    38.7  792.09    48.4  785.27
    67.8  770.32    77.5   763.8    87.2  761.17    96.8  762.29   106.5  764.17
   116.2  763.28   125.9   758.7   135.6   756.4   174.7  755.83   184.4  754.55
     204  748.43   213.8  747.18   233.3  746.92     244 747.254   282.1  749.84
   409.2  759.42   428.7  761.43   438.5  763.53   448.3  767.18   458.1  771.87
   487.4  787.24     507  795.18   585.3  821.76   614.7  829.96   644.1  839.01
#Mann= 3 , 0 , 0
       0      .1       0     204    .045       0     244      .1       0
Bank Sta=204,244
XS Rating Curve= 0 ,0
Exp/Cntr=0.3,0.1

Type RM Length L Ch R = 1 ,71798.3 ,308.8,322.5,336.1
XS GIS Cut Line= 3
     1870626.769       496275.25     1870426.248      496465.354
       1870166.7      496641.569
#Sta/Elev= 30
       0  810.05    19.1  805.72    28.6  802.73    38.1  799.16    47.6  794.71
    57.2  788.31    66.7  779.87    76.2  770.46    85.8  763.29    95.3  760.53
   114.3  763.14   123.9  763.42   133.4   760.8   142.9  756.36   152.4  753.52
     162  752.91   247.7   752.8   354.7  751.71   364.5  750.39   384.2     745
     394  744.49   413.6  745.31   423.4  745.03   433.2  745.98     443  751.83
   482.2  794.43     492  804.61   501.8  813.56   511.6  820.44     590  869.24
#Mann= 3 , 0 , 0
       0      .1       0   384.2    .045       0   433.2      .1       0
Bank Sta=384.2,433.2
XS Rating Curve= 0 ,0
Exp/Cntr=0.3,0.1

Type RM Length L Ch R = 1 ,71475.7 ,364.6,371.7,378.4
XS GIS Cut Line= 2
     1870503.332      496228.201     1870095.693      496224.903
#Sta/Elev= 27
       0  772.39    29.1  762.99    38.8  760.78    48.5  760.06    58.2  759.94
    67.9   759.4    77.6  757.71    97.1  751.88   106.8  750.35   116.5  750.06
   174.7  750.06   184.4  749.96   194.1  748.85   203.8  745.87   213.5  743.63
   223.2   743.5   242.6  743.51   252.4  743.67   262.1  744.96   271.8  750.01
   281.5  763.32   291.2  778.39   300.9     790   310.6  799.62   320.3  806.37
   368.8   832.9   407.6  853.78
#Mann= 3 , 0 , 0
       0      .1       0   213.5    .045       0   262.1      .1       0
Bank Sta=213.5,262.1
XS Rating Curve= 0 ,0
Exp/Cntr=0.3,0.1

Type RM Length L Ch R = 1 ,71104   ,387.3,383.9,379.9
XS GIS Cut Line= 3
     1870698.991      495944.579     1870366.236      495880.316
     1870157.325      495812.634
#Sta/Elev= 30
       0  819.55    58.1  800.09   145.2  770.56   164.6  763.88     184  757.47
   193.7  755.83     213  755.21   242.1  754.58   271.1  754.72   290.5  755.15
   338.9  756.57   348.4  756.52     358  755.36   367.6  752.26   377.1  747.91
   386.6  744.46   396.2  742.99   415.3  741.72   424.8  741.28   434.4  741.26
   443.9  743.17   453.5  750.33     463  762.18   472.6  775.14   482.1  788.15
   491.7  800.77   501.2  809.99   529.9  828.01     549  840.22   558.5  846.44
#Mann= 3 , 0 , 0
       0      .1       0   396.2    .045       0   443.9      .1       0
#XS Ineff= 2 , 0
          342.31  760.72
Permanent Ineff=
       F       F
Bank Sta=396.2,443.9
XS Rating Curve= 0 ,0
Exp/Cntr=0.3,0.1

Type RM Length L Ch R = 1 ,70720.1 ,538,516.1,493.8
XS GIS Cut Line= 4
     1870762.498      495555.065     1870583.887       495558.12
     1870430.276      495533.954     1870205.832       495575.62
#Sta/Elev= 30
       0  837.53    18.8  828.74    37.6  819.26   122.2  773.75   150.4  759.96
   159.8  755.97   169.2   753.2   178.6  752.05   198.1  751.44   207.8  750.21
   227.2  743.16     237   742.1   266.1   741.9   285.5  741.02   295.3  741.07
     305  742.86   314.7  744.95   324.4  745.93   343.6  746.92   372.2  749.67
   381.7  749.72   391.2   748.4   400.7  748.01   410.2  750.37   419.7  753.75
   438.8  759.82   448.3  763.91   467.3  773.09   505.4  792.53   562.4  824.78
#Mann= 3 , 0 , 0
       0      .1       0   227.2    .045       0     305      .1       0
Bank Sta=227.2,305
XS Rating Curve= 0 ,0
Exp/Cntr=0.3,0.1

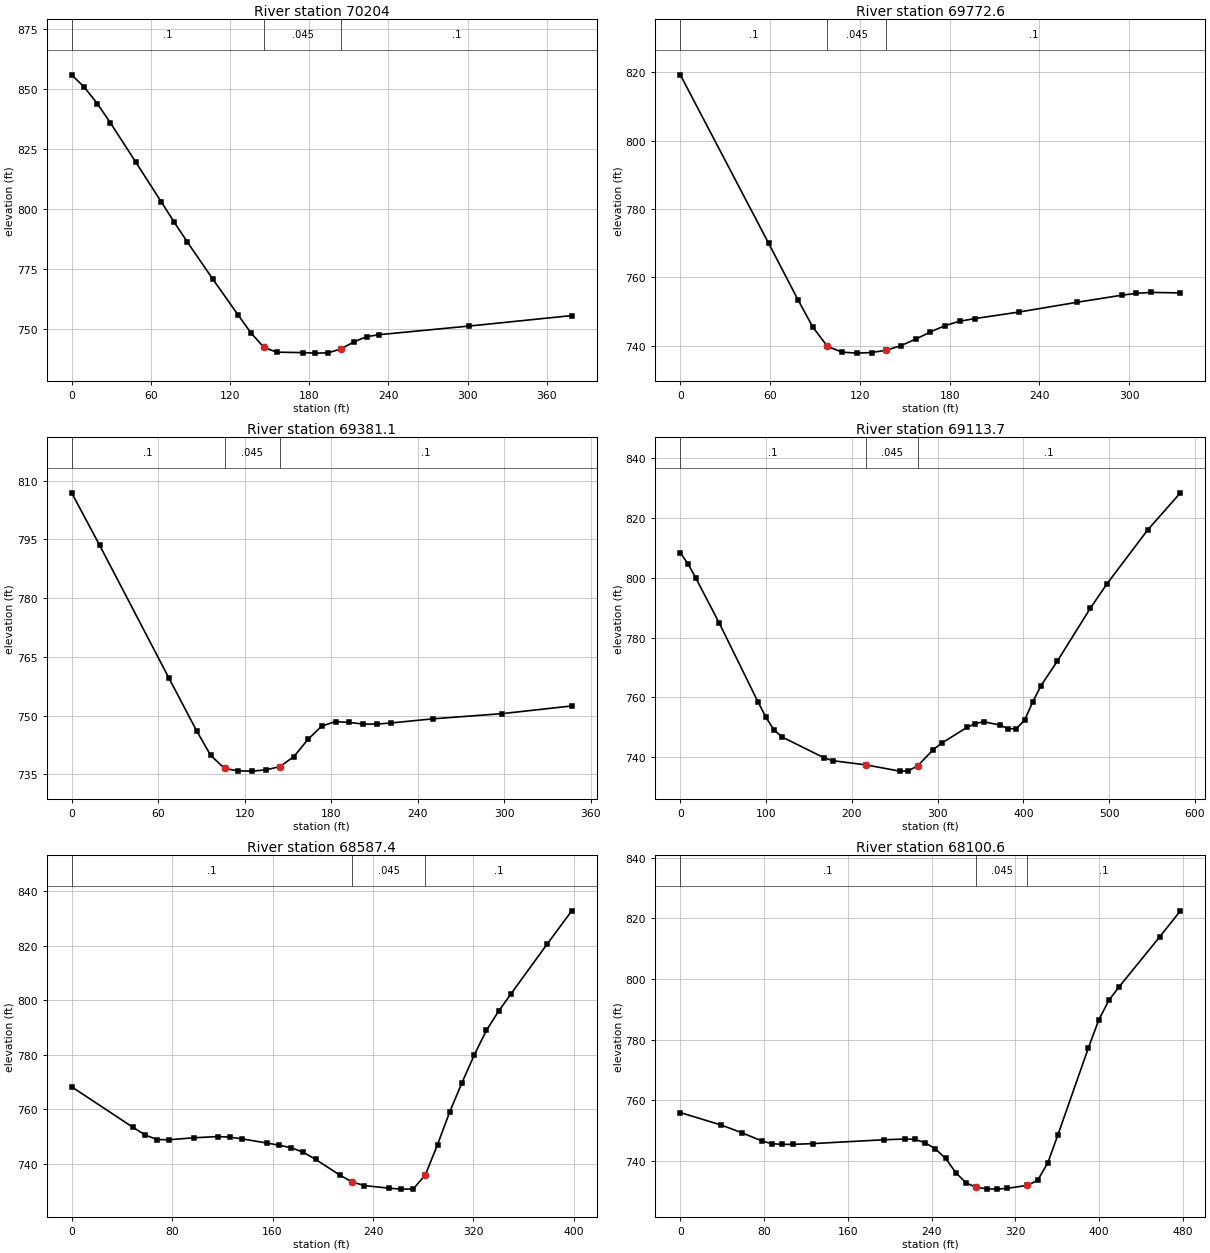
Type RM Length L Ch R = 1 ,70204   ,441.5,431.4,421.2
XS GIS Cut Line= 2
     1870510.038      494952.378      1870254.07      495231.775
#Sta/Elev= 22
       0  855.82     9.7  850.58    19.4  843.88    29.2  835.97    48.6   819.5
      68  802.92    77.7  794.55    87.4   786.5   106.9  770.92   126.3  755.84
     136  748.45   145.7  742.47   155.5  740.52   174.9  740.35   184.6  740.13
   194.3  740.24     204  741.88   213.8  744.79   223.5  746.98   233.2  747.81
   301.2  751.39   378.9  755.74
#Mann= 3 , 0 , 0
       0      .1       0   145.7    .045       0     204      .1       0
Bank Sta=145.7,204
XS Rating Curve= 0 ,0
Exp/Cntr=0.3,0.1

Type RM Length L Ch R = 1 ,69772.6 ,397.2,391.5,385.8
XS GIS Cut Line= 2
     1870054.243      494757.643      1869958.41      495077.782
#Sta/Elev= 21
       0   819.3      59  770.02    78.6  753.51    88.5  745.52    98.3  739.84
   108.1  738.16   117.9  737.87   127.8  738.04   137.6  738.73   147.4  740.06
   157.3  741.97   167.1  744.05   176.9  745.93   186.7   747.2   196.6  747.96
   226.1  749.88   265.4  752.77   294.9  754.81   304.7  755.36   314.5  755.63
   334.2  755.49
#Mann= 3 , 0 , 0
       0      .1       0    98.3    .045       0   137.6      .1       0
Bank Sta=98.3,137.6
XS Rating Curve= 0 ,0
Exp/Cntr=0.3,0.1

Type RM Length L Ch R = 1 ,69381.1 ,266.7,267.4,267.7
XS GIS Cut Line= 2
     1869638.861      494696.966     1869625.667      495043.494
#Sta/Elev= 21
       0  806.88    19.3  793.56    67.4  759.61    86.7  746.09    96.3  739.91
     106  736.51   115.6   735.9   125.2  735.83   134.9  736.16   144.5     737
   154.1  739.53   163.8  743.91   173.4  747.33     183  748.49   192.6  748.26
   202.3  747.84   211.9  747.85   221.6  748.13   250.4  749.18   298.6  750.51
   346.8  752.47
#Mann= 3 , 0 , 0
       0      .1       0     106    .045       0   144.5      .1       0
Bank Sta=106,144.5
XS Rating Curve= 0 ,0
Exp/Cntr=0.3,0.1

Type RM Length L Ch R = 1 ,69113.7 ,502.2,526.3,550
XS GIS Cut Line= 4
     1869443.007      494617.068     1869380.785      494706.512
     1869366.188      494950.881     1869253.007      495150.401
#Sta/Elev= 30
       0   808.4     9.1  804.55    18.2  799.82    45.4  784.85    90.8  758.37
    99.9  753.36     109   749.2   118.8  746.75   167.7  739.81   177.5  738.86
   216.7  737.44   255.8  735.36   265.6  735.39   276.9 737.147     295  742.57
   304.8  744.71   334.2  749.96     344  751.24   353.8  751.88   372.9  750.73
   382.4  749.52     392  749.56   401.6  752.46   411.1  758.57   420.7  763.97
   439.8  772.19     478  789.74   497.1  797.79   544.9  815.94   583.2  828.39
#Mann= 3 , 0 , 0
       0      .1       0   216.7    .045       0   276.9      .1       0
Bank Sta=216.7,276.9
XS Rating Curve= 0 ,0
Exp/Cntr=0.3,0.1

Type RM Length L Ch R = 1 ,68587.4 ,484.1,486.8,489.4
XS GIS Cut Line= 2
     1869189.898      494488.682     1868831.635      494662.722
#Sta/Elev= 30
       0  768.24    48.6  753.46    58.3  750.65      68   748.9    77.7  748.85
    97.2  749.56   116.6  750.02   126.3  749.78     136  749.14   155.4  747.64
   165.2  746.84   174.9  745.93   184.6  744.22   194.3  741.65   213.7  735.85
   223.4  733.36   233.2  732.05   252.6   731.1   262.3  730.75     272   730.8
   281.7  735.96   291.4  747.09   301.2  759.17   310.9   769.8   320.6  779.86
   330.3   788.9     340  795.92   349.7  802.18   378.9  820.67   398.3  832.73
#Mann= 3 , 0 , 0
       0      .1       0   223.4    .045       0   281.7      .1       0
Bank Sta=223.4,281.7
XS Rating Curve= 0 ,0
Exp/Cntr=0.3,0.1

Type RM Length L Ch R = 1 ,68100.6 ,484.3,468.6,452.9
XS GIS Cut Line= 2
     1869086.044      494040.771     1868635.002      494198.063
#Sta/Elev= 30
       0  755.91      39   751.8    58.5  749.29      78  746.52    87.7  745.61
    97.5  745.43   107.2  745.41   126.7  745.67     195  746.95   214.5  747.16
   224.2  747.06     234  745.92   243.7   743.9   253.5  740.75   263.2  736.04
     273  732.68   282.4 731.304   292.5  730.74   302.2  730.64     312  730.89
   331.4  731.88   341.2   733.5     351  739.28   360.7  748.58   389.9  777.35
   399.7  786.48   409.4  792.99   419.2  797.44   458.2  814.02   477.7   822.5
#Mann= 3 , 0 , 0
       0      .1       0   282.4    .045       0   331.4      .1       0
Bank Sta=282.4,331.4
XS Rating Curve= 0 ,0
Exp/Cntr=0.3,0.1

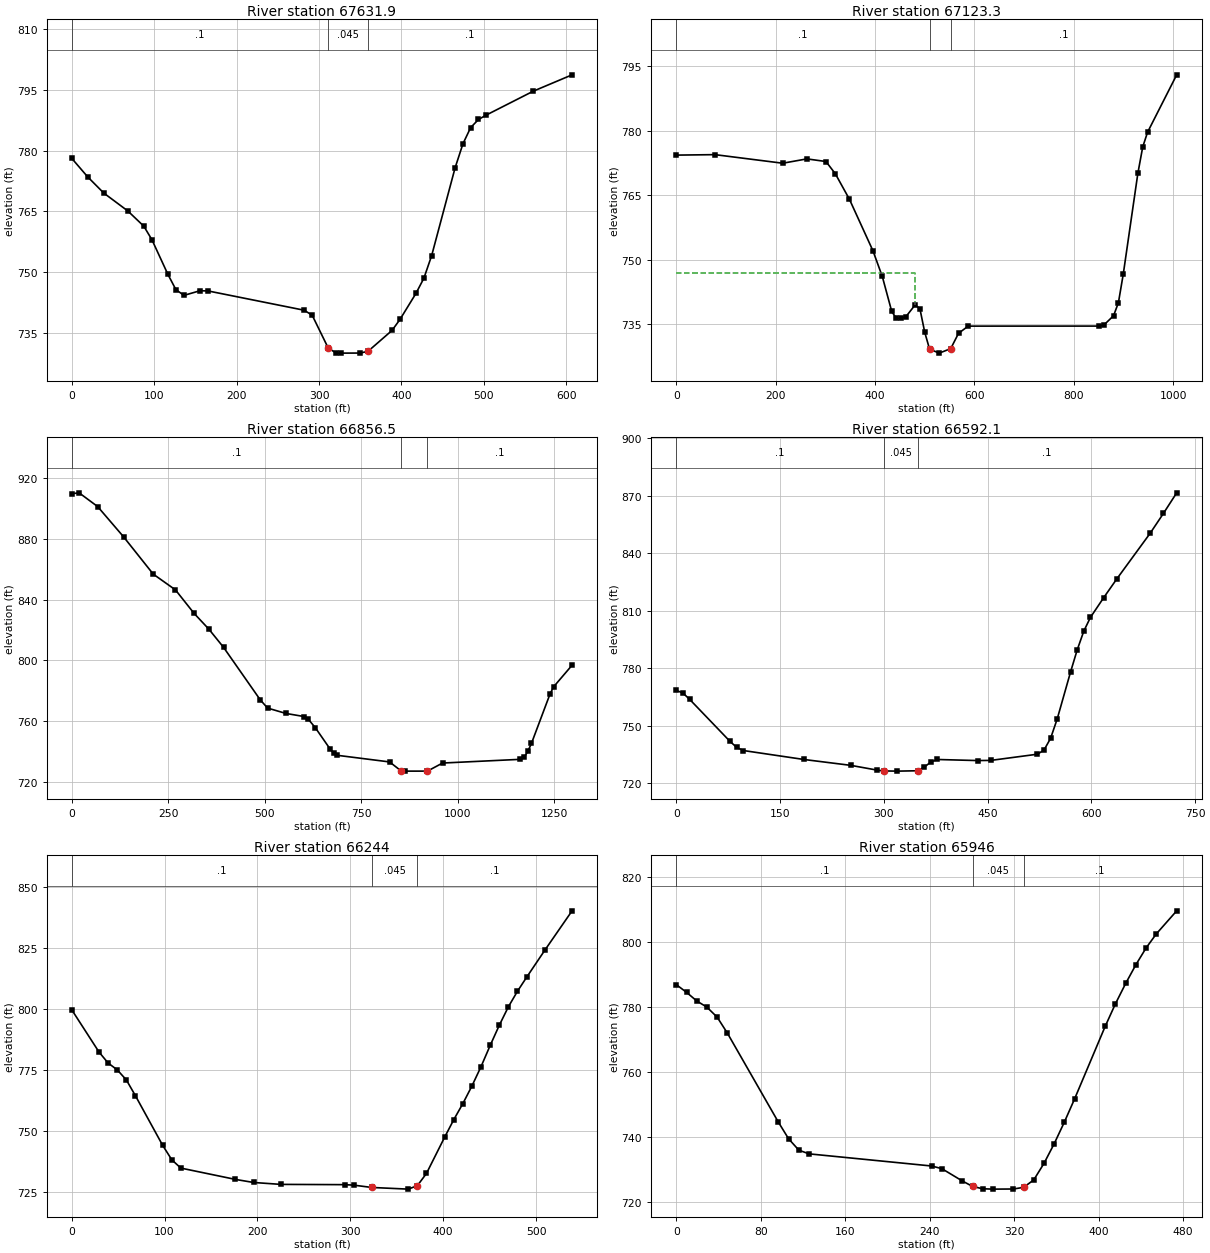
Type RM Length L Ch R = 1 ,67631.9 ,530.8,508.6,486.3
XS GIS Cut Line= 4
     1868850.992      493483.651      1868645.14      493661.975
     1868564.999      493794.457     1868557.936      493974.058
#Sta/Elev= 30
       0   778.1    19.4  773.51    38.9  769.52    68.1  765.09    87.5  761.33
    97.3     758   116.7  749.44   126.4  745.67   136.2  744.26   155.6   745.4
   165.4  745.35     282  740.59   291.7  739.35   311.1  731.27   320.7  730.01
   326.4     730   349.8  730.02   359.4  730.45   388.5   735.6   398.2  738.32
   417.5  744.73   427.2  748.51   436.6  754.08     465  775.73   474.5  781.66
   483.9  785.68   493.4  787.68   502.9  788.78   559.6  794.64   606.9   798.7
#Mann= 3 , 0 , 0
       0      .1       0   311.1    .045       0   359.4      .1       0
Bank Sta=311.1,359.4
XS Rating Curve= 0 ,0
Exp/Cntr=0.3,0.1

Type RM Length L Ch R = 1 ,67123.3 ,292.2,266.9,241.3
XS GIS Cut Line= 5
      1868016.53      493261.667     1868127.988      493521.042
     1868111.321      493728.334     1868190.488         493895.
     1868458.196      494091.875
#Sta/Elev= 30
       0  774.36    77.9  774.47   214.2  772.47   262.8  773.48   301.2  772.87
   320.1  770.01   348.5  764.06   395.7   752.1   414.6  746.09   433.6  737.94
     443  736.31   452.5  736.34   461.9   736.7   480.8  739.49   490.3  738.57
     500   733.1   509.7  729.18   529.1  728.24   552.3729.2864     568  732.85
   587.4  734.53   850.7  734.54   860.5  734.78     880  736.95   889.8  739.98
   899.6  746.67   928.9  770.08   938.7  776.24   948.4  779.68  1007.1  793.06
#Mann= 3 , 0 , 0
       0      .1       0   509.7    .045       0   552.3      .1       0
#XS Ineff= 2 , 0
          481.04   746.9
Permanent Ineff=
       F       F
Bank Sta=509.7,552.3
XS Rating Curve= 0 ,0
Exp/Cntr=0.3,0.1

Type RM Length L Ch R = 1 ,66856.5 ,249,264.4,279.7
XS GIS Cut Line= 6
     1867369.655      493541.875      1867565.26      493838.448
     1867758.735      493976.268     1867908.717      494002.292
     1868163.405      494003.334     1868420.349      494150.903
#Sta/Elev= 30
       0  909.74    19.2  910.32    67.2  901.28   134.4  881.35   211.2   856.8
   268.8  846.41   316.9  830.99   355.3  820.56   393.3  808.61   488.3  774.06
   507.3  768.62   554.8  765.08   602.3  763.02   611.8  761.56   630.9  755.73
   668.9   741.8   678.4  738.95     688  737.51   823.4  733.15   852.8  727.31
   862.6   727.1   921.4  727.11   960.5  732.42  1162.2  734.87  1171.8  736.16
  1181.3  740.08  1190.9  745.42  1238.7  777.77  1248.2  782.62    1296  796.84
#Mann= 3 , 0 , 0
       0      .1       0   852.8    .045       0   921.4      .1       0
Bank Sta=852.8,921.4
XS Rating Curve= 0 ,0
Exp/Cntr=0.3,0.1

Type RM Length L Ch R = 1 ,66592.1 ,344.6,348.1,351.4
XS GIS Cut Line= 4
     1867723.648      494092.917      1867892.05      494168.438
      1868079.55      494320.347      1868258.37      494558.195
#Sta/Elev= 30
       0  768.53     9.7  767.11    19.4  763.81    77.7   741.9    87.4  738.74
    97.1  737.14   184.6  732.47   252.1  729.42   290.7   726.9   300.4   726.5
   319.7   726.4   348.7  726.59   358.3  728.44     368  731.16   377.6  732.47
   435.5  731.91   454.7     732   521.9  735.22   531.5  737.35   541.1  743.52
   550.7  753.68   569.9  778.06   579.5  789.58   589.1  799.45   598.7  806.62
   617.9  816.93     637  826.78     685  850.49   704.2  860.86   723.4  871.61
#Mann= 3 , 0 , 0
       0      .1       0   300.4    .045       0   348.7      .1       0
Bank Sta=300.4,348.7
XS Rating Curve= 0 ,0
Exp/Cntr=0.3,0.1

Type RM Length L Ch R = 1 ,66244   ,290.1,297.9,305.8
XS GIS Cut Line= 2
      1867604.55      494302.431     1867967.745      494700.347
#Sta/Elev= 30
       0  799.76    29.4  782.43    39.2  777.92      49  775.14    58.8  771.03
    68.6  764.55      98  744.18   107.8  738.29   117.5   734.9   176.3  730.26
   195.9     729   225.3  728.22   293.9  728.11   303.7  727.91   323.2  726.96
   362.4  726.28   372.2   727.7     382   732.7   401.6  747.56   411.4  754.72
   421.2  761.31     431  768.54   440.8  776.47   450.6  785.11   460.4  793.36
   470.2  800.93     480  807.32   489.8     813   509.4  824.08   538.8  840.24
#Mann= 3 , 0 , 0
       0      .1       0   323.2    .045       0   372.2      .1       0
Bank Sta=323.2,372.2
XS Rating Curve= 0 ,0
Exp/Cntr=0.3,0.1

Type RM Length L Ch R = 1 ,65946   ,420.4,429.4,438.2
XS GIS Cut Line= 2
     1867465.524      494421.778     1867646.568       494859.89
#Sta/Elev= 30
       0  786.97     9.7   784.6    19.4  781.94      29  780.03    38.7  776.96
    48.4  772.03    96.7  744.62   106.4  739.49   116.1  735.99   125.8  734.86
   241.9  731.12   251.5  730.31   270.9  726.52   280.6  724.84   290.2  724.11
   299.9     724   319.3  724.04   328.9  724.54   338.6  726.83   348.3  731.93
     358  738.01   367.6  744.65   377.3   751.8   406.3  774.15     416  781.09
   425.7  787.36   435.4  793.13     445  798.26   454.7   802.6     474   809.7
#Mann= 3 , 0 , 0
       0      .1       0   280.6    .045       0   328.9      .1       0
Bank Sta=280.6,328.9
XS Rating Curve= 0 ,0
Exp/Cntr=0.3,0.1

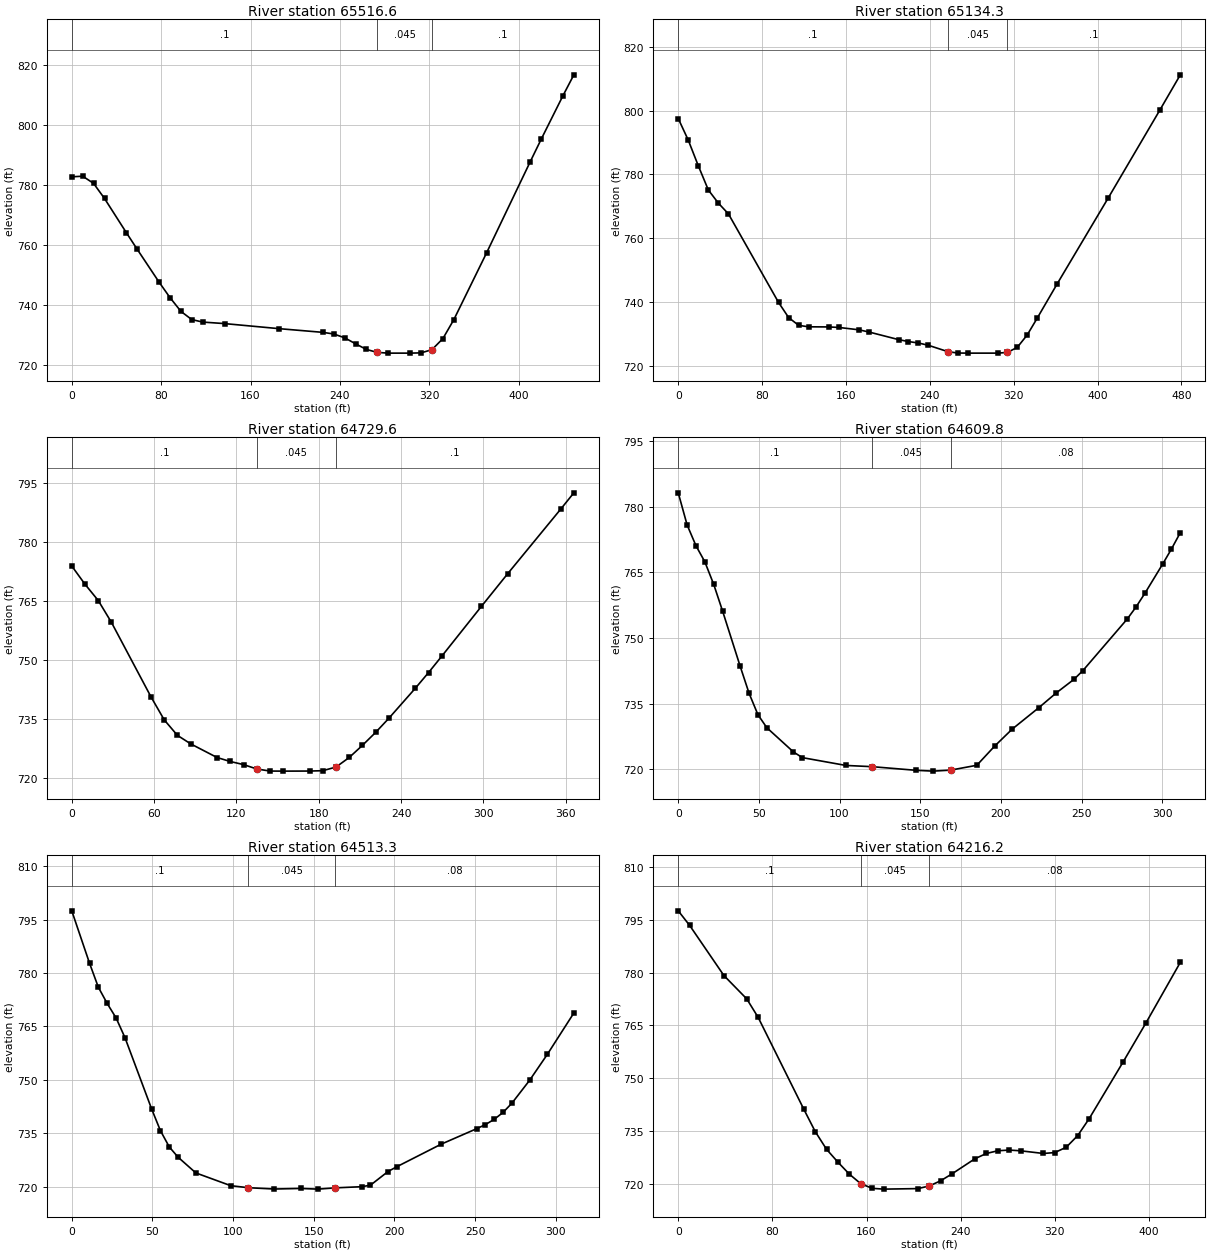
Type RM Length L Ch R = 1 ,65516.6 ,376.8,382.3,387.7
XS GIS Cut Line= 2
     1867170.729      494505.155     1867168.646       494954.46
#Sta/Elev= 30
       0  782.72     9.8  782.92    19.5  780.53    29.3  775.49    48.8  764.11
    58.6  758.52    78.1   747.6    87.9  742.42    97.7  737.82   107.4  735.09
   117.2  734.26   136.8  733.75   185.6  732.06   224.7  730.83   234.4  730.29
   244.2  729.02     254     727   263.7  725.12   273.5  724.14   283.3   723.9
   302.8   723.9   312.6  723.99   322.3  725.05   332.1  728.74   341.9  735.07
   371.2  757.34   410.2   787.7     420   795.2   439.5  809.74   449.3  816.74
#Mann= 3 , 0 , 0
       0      .1       0   273.5    .045       0   322.3      .1       0
Bank Sta=273.5,322.3
XS Rating Curve= 0 ,0
Exp/Cntr=0.3,0.1

Type RM Length L Ch R = 1 ,65134.3 ,408.2,404.8,401.3
XS GIS Cut Line= 4
     1866835.729      494479.877     1866816.285       494660.71
     1866772.325      494834.619     1866760.729      494951.682
#Sta/Elev= 30
       0  797.52     9.6  790.71    19.1  782.72    28.7   775.1    38.3  770.96
    47.9  767.58    95.7   739.8   105.3  735.06   114.9  732.61   124.4  732.16
   143.6  732.12   153.2  731.96   172.3  731.22   181.9  730.53   210.2  728.14
   219.6  727.53   229.1  727.08   238.5  726.37   257.4  724.34   266.8  723.93
   276.3   723.9   304.6   723.9     314  724.11   323.5  725.75   332.9  729.62
   342.4  734.87   361.2   745.5   410.3  772.68   459.3  800.12   478.9  811.23
#Mann= 3 , 0 , 0
       0      .1       0   257.4    .045       0     314      .1       0
Bank Sta=257.4,314
XS Rating Curve= 0 ,0
Exp/Cntr=0.3,0.1

Type RM Length L Ch R = 1 ,64729.6 ,67.2,119.8,172.3
XS GIS Cut Line= 2
     1866416.832       494491.63     1866381.415      494855.797
#Sta/Elev= 28
       0  773.86     9.6  769.24    19.3  765.08    28.9  759.53    57.8  740.53
    67.4  734.71      77  730.78    86.7  728.61   105.9  725.14   115.5  724.13
   125.2  723.34   134.8  722.23   144.4   721.7   154.1  721.68   173.3   721.7
   182.9  721.79   192.6  722.72   202.2  725.15   211.8  728.23   221.5  731.55
   231.1  735.13   250.3  742.73     260  746.75   269.6   750.9   298.5  763.58
   317.7  771.91   356.3  788.32   365.9  792.48
#Mann= 3 , 0 , 0
       0      .1       0   134.8    .045       0   192.6      .1       0
Bank Sta=134.8,192.6
XS Rating Curve= 0 ,0
Exp/Cntr=0.3,0.1

Type RM Length L Ch R = 1 ,64609.8 ,90.7,96.5,106.9
XS GIS Cut Line= 4
     1866396.446      494477.799     1866361.168      494607.174
     1866178.251      494653.008      1866115.89      494863.911
#Sta/Elev= 30
       0  783.22   5.506  775.87  11.013   771.1  16.462  767.46  21.968   762.3
  27.474  756.19   38.43   743.5  43.936  737.33  49.442  732.43  54.949  729.47
   71.41  723.94  76.917  722.64 103.932  720.85 120.164  720.57 147.237  719.74
  158.02  719.55 168.861  719.78 185.093  720.89 196.048  725.24 207.004  729.16
 223.465  734.05 234.421  737.47 245.376  740.57 250.882  742.57 278.299  754.34
 283.806  757.12 289.312  760.26 300.267  766.91 305.716  770.36 311.223  774.11
#Mann= 3 , 0 , 0
       0      .1       0 120.164    .045       0 168.861     .08       0
Bank Sta=120.164,168.861
XS Rating Curve= 0 ,0
Skew Angle= 55
Exp/Cntr=0.3,0.1

Type RM Length L Ch R = 1 ,64513.3 ,357.4,297.1,232.3
XS GIS Cut Line= 4
     1866328.529      494456.966     1866293.251      494586.341
     1866110.334      494632.174     1866047.973      494843.077
#Sta/Elev= 30
       0  797.48  11.013  782.76  16.462  776.02  21.968  771.44  27.474  767.38
  32.981  761.84  49.442  741.88  54.949  735.71  60.455  731.13  65.904  728.25
  76.917  723.83   98.54  720.25 109.381  719.68 125.613  719.31 141.788  719.47
 152.629  719.28 163.469  719.64 179.644  719.96 185.093  720.37 196.048  724.23
 201.555  725.59 228.972  731.91 250.882  736.24 256.389  737.41 261.838  738.88
 267.344  740.84  272.85  743.44 283.806  749.86 294.761  757.13 311.223  768.77
#Mann= 3 , 0 , 0
       0      .1       0 109.381    .045       0 163.469     .08       0
Bank Sta=109.381,163.469
XS Rating Curve= 0 ,0
Skew Angle= 55
Exp/Cntr=0.3,0.1

Type RM Length L Ch R = 1 ,64216.2 ,454.6,455.1,455.6
XS GIS Cut Line= 2
     1865894.389      494418.994     1865889.811       494845.61
#Sta/Elev= 30
       0  797.55     9.7   793.4    38.8  779.15    58.2  772.51    67.9  767.25
   106.7  741.12   116.4  734.77     126  729.73   135.8  726.03   145.4  722.66
   155.1  719.94   164.8  718.63   174.5   718.4   203.6  718.55   213.3   719.3
     223  720.78   232.7  722.76   252.1  727.04   261.8  728.54   271.5  729.31
   281.2  729.51   290.9   729.3   310.3  728.54     320   728.8   329.7  730.32
   339.4  733.62   349.1  738.41   378.2  754.68   397.6  765.78   426.6  782.89
#Mann= 3 , 0 , 0
       0      .1       0   155.1    .045       0   213.3     .08       0
Bank Sta=155.1,213.3
XS Rating Curve= 0 ,0
Exp/Cntr=0.3,0.1

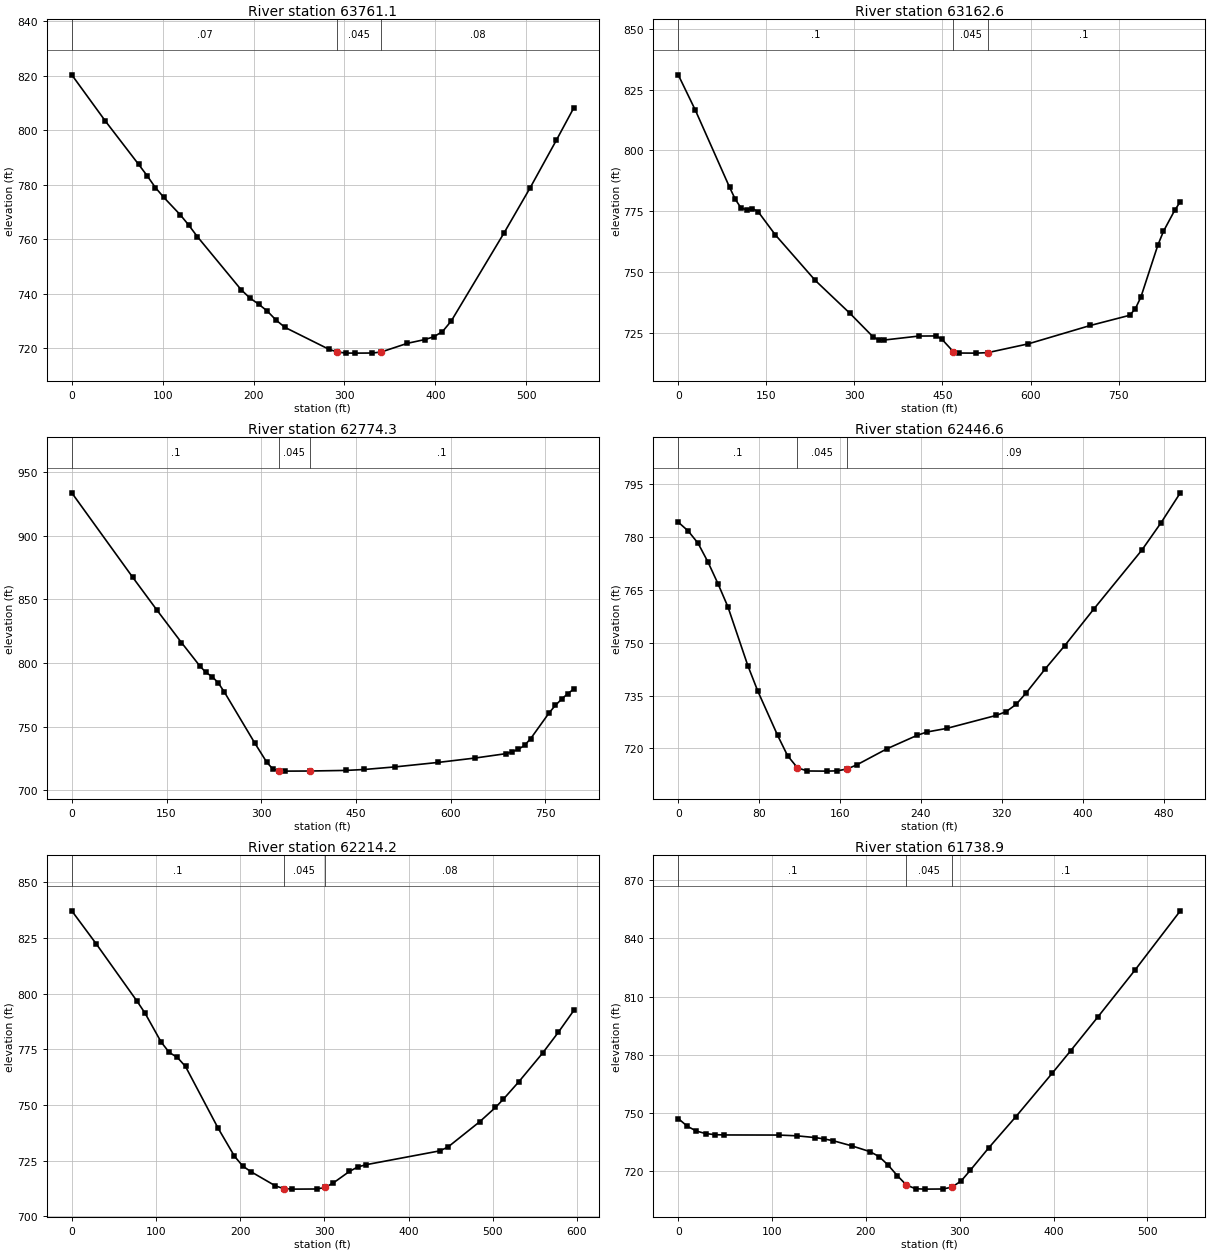
Type RM Length L Ch R = 1 ,63761.1 ,607.5,598.5,589.4
XS GIS Cut Line= 3
     1865511.159      494308.317      1865442.93      494428.343
     1865429.909      494842.406
#Sta/Elev= 30
       0  820.29    36.8   803.4    73.6  787.41    82.8  783.33      92  778.93
   101.2  775.35   119.6  768.85   128.9  765.06   138.1  760.96   186.2  741.51
   195.9  738.42   205.5   736.2   215.1  733.62   224.8  730.31   234.4  727.68
   282.6  719.67   292.2   718.6   301.8  718.24   311.5  718.21   330.8  718.25
   340.4  718.62   369.3  721.82   388.6   723.2   398.2  724.21   407.8  726.11
   417.4  729.97   475.3  762.17   504.2  778.83   533.1  796.33   552.3  808.21
#Mann= 3 , 0 , 0
       0     .07       0   292.2    .045       0   340.4     .08       0
Bank Sta=292.2,340.4
XS Rating Curve= 0 ,0
Exp/Cntr=0.3,0.1

Type RM Length L Ch R = 1 ,63162.6 ,423.5,388.3,353
XS GIS Cut Line= 4
     1864708.624      494160.791     1864758.618      494388.698
     1864890.339      494726.717     1865074.957       494908.21
#Sta/Elev= 30
       0  831.15    29.2  816.56    87.5  784.79    97.2  779.86   106.9  776.33
   116.7   775.5   126.4  776.05   136.1  774.76   165.3  765.25   233.3  746.47
   292.2  732.95   331.4  723.31   341.2  721.98     351  721.92   409.8  723.55
   439.2   723.6     449  722.24   468.6  717.08   478.4  716.56   507.9  716.52
   527.5  716.74   596.1  720.34   701.6   727.9   768.7   732.1   778.3  734.76
   787.9  739.63   816.6  760.89   826.2  766.65   845.4  775.32     855  778.89
#Mann= 3 , 0 , 0
       0      .1       0   468.6    .045       0   527.5      .1       0
Bank Sta=468.6,527.5
XS Rating Curve= 0 ,0
Exp/Cntr=0.3,0.1

Type RM Length L Ch R = 1 ,62774.3 ,327.1,327.7,328.3
XS GIS Cut Line= 3
     1864314.064      495014.177     1864748.092      494852.284
     1865072.744      494919.993
#Sta/Elev= 30
       0  933.55    96.5  867.21   135.1  841.27   173.7  815.95   202.7  797.61
   212.3  792.53     222  789.27   231.6  784.53   241.3  777.34   289.5  737.23
   308.8  721.92   318.5  716.55   328.1  715.11   337.8     715   376.4  715.09
   434.3  715.56   463.2  716.29     512  718.33   580.3  721.85   638.8   725.3
   687.6  728.73   697.3  730.14   707.1  732.19   716.8   735.2   726.6  740.57
   755.9  760.85   765.6   766.6   775.4   771.5   785.1  775.76   794.9  779.49
#Mann= 3 , 0 , 0
       0      .1       0   328.1    .045       0   376.4      .1       0
Bank Sta=328.1,376.4
XS Rating Curve= 0 ,0
Exp/Cntr=0.3,0.1

Type RM Length L Ch R = 1 ,62446.6 ,231.8,232.5,233
XS GIS Cut Line= 3
     1864653.835      495232.053     1864979.356      495120.942
     1865130.397      495100.108
#Sta/Elev= 30
       0  784.14     9.8  781.65    19.6  778.16    29.5  772.78    39.3  766.69
    49.1  760.15    68.8  743.48    78.6  736.29    98.3  723.68   108.1  717.95
   117.9   714.5   127.8  713.61   147.4  713.57   157.2  713.65   167.1  714.19
   176.9   715.4   206.4  719.91   235.9  723.68   245.7  724.65   265.3  725.67
   314.5  729.37   324.3  730.44   334.1   732.5     344  735.74     363   742.6
   382.1  749.13   410.7  759.45   458.3  776.19   477.4  783.99   496.4  792.45
#Mann= 3 , 0 , 0
       0      .1       0   117.9    .045       0   167.1     .09       0
Bank Sta=117.9,167.1
XS Rating Curve= 0 ,0
Exp/Cntr=0.3,0.1

Type RM Length L Ch R = 1 ,62214.2 ,457.9,475.3,492.7
XS GIS Cut Line= 4
     1864591.335        495407.4     1864762.431       495437.67
     1865032.548      495353.485     1865171.196      495336.219
#Sta/Elev= 30
       0  837.11      29  822.31    77.2  796.73    86.9  791.26   106.2  778.19
   115.8  773.56   125.5  771.28   135.1  767.25   173.8  739.57   193.3  726.96
     203  722.59   212.8  720.03     242  713.64   251.8  712.42   261.6   712.2
   290.8  712.26   300.6  712.94   310.3  714.88   329.8  720.14   339.6  722.13
   349.4  723.15   437.2  729.38   446.9   731.1   484.6  742.46   503.3  748.86
   512.6  752.53   531.2  760.46   559.2  773.22   577.8  782.51   596.4  792.42
#Mann= 3 , 0 , 0
       0      .1       0   251.8    .045       0   300.6     .08       0
Bank Sta=251.8,300.6
XS Rating Curve= 0 ,0
Exp/Cntr=0.3,0.1

Type RM Length L Ch R = 1 ,61738.9 ,306.5,311.7,316.9
XS GIS Cut Line= 2
     1864612.191      495749.568     1865089.971       495990.32
#Sta/Elev= 30
       0  747.19     9.7  743.19    19.4  740.71    29.2  739.45    38.9  738.88
    48.6  738.72     107  738.67   126.5  738.27   145.9  737.37   155.6  736.66
   165.4  735.71   184.8  733.12   204.3  730.13     214  727.58   223.7  723.18
   233.5  717.72   243.2  712.89   252.9     711   262.6   710.8   282.1  710.87
   291.8  711.84   301.6  715.08   311.3  720.57   330.7  731.99   359.9  748.22
   398.8  770.71   418.3  782.21   447.5  799.76   486.4  823.51     535  854.24
#Mann= 3 , 0 , 0
       0      .1       0   243.2    .045       0   291.8      .1       0
Bank Sta=243.2,291.8
XS Rating Curve= 0 ,0
Exp/Cntr=0.3,0.1

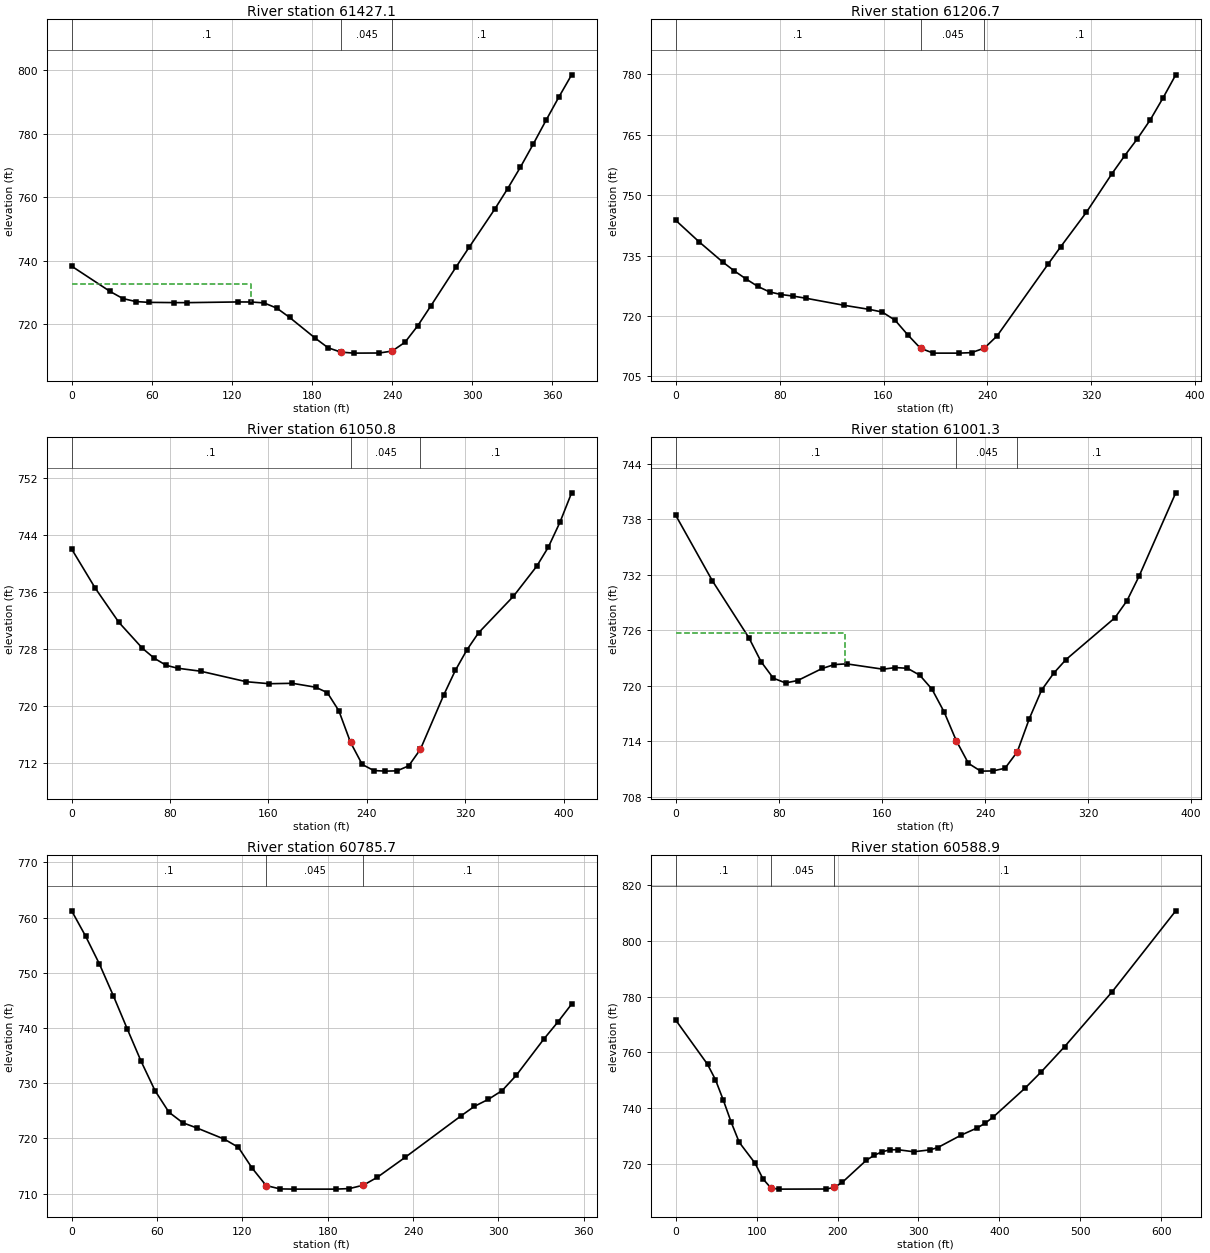
Type RM Length L Ch R = 1 ,61427.1 ,214.6,220.5,226.4
XS GIS Cut Line= 2
     1864513.455      495988.678       1864800.4      496229.094
#Sta/Elev= 30
       0  738.22    28.8  730.24    38.4     728      48  727.07    57.6  726.81
    76.8  726.73    86.4  726.72   124.8  726.94   134.4  726.92     144  726.64
   153.6     725   163.2  722.06   182.4  715.52     192  712.49   201.6  711.12
   211.2   710.8   230.4  710.84     240  711.45   249.6  714.22   259.2  719.44
   268.8  725.58     288  738.05   297.6  744.15   316.8  756.18   326.4   762.6
     336   769.4   345.6  776.67   355.2  784.19   364.8  791.51   374.4  798.56
#Mann= 3 , 0 , 0
       0      .1       0   201.6    .045       0     240      .1       0
#XS Ineff= 2 , 0
          134.07   732.6
Permanent Ineff=
       F       F
Bank Sta=201.6,240
XS Rating Curve= 0 ,0
Exp/Cntr=0.3,0.1

Type RM Length L Ch R = 1 ,61206.7 ,142.7,155.9,169.1
XS GIS Cut Line= 3
     1864399.819      496092.165     1864443.605      496171.096
     1864613.169      496412.271
#Sta/Elev= 30
       0  743.74      18  738.41    36.1  733.42    45.1   731.2    54.2  729.19
    63.2  727.35    72.2  725.99    81.2  725.34    90.3  724.96   100.1  724.43
   129.6  722.67   149.2  721.65     159     721   168.9  718.97   178.7  715.33
   188.5     712   198.4   710.8     218   710.8   227.8  710.92   237.7  712.05
   247.5  715.08   286.8  732.91   296.6  737.25   316.3  745.77   335.9  755.31
   345.8  759.81   355.6  764.03   365.4  768.66   375.2  774.08   385.1  779.87
#Mann= 3 , 0 , 0
       0      .1       0   188.5    .045       0   237.7      .1       0
Bank Sta=188.5,237.7
XS Rating Curve= 0 ,0
Exp/Cntr=0.3,0.1

Type RM Length L Ch R = 1 ,61050.8 ,49.6,49.5,49.5
XS GIS Cut Line= 4
     1864390.946      496101.855      1864414.59      496174.888
     1864374.333      496269.391      1864382.25      496496.335
#Sta/Elev= 30
       0     742    19.2   736.5    38.4   731.7    57.6  728.05    67.2  726.66
    76.8  725.67    86.1  725.26   104.8  724.84   142.1  723.36   160.8  723.08
   179.5  723.14   198.4  722.59   207.9  721.83   217.3  719.28   226.8  714.84
   236.3  711.74   245.7  710.88   255.2   710.8   264.6  710.84   274.1  711.54
   283.6  713.86   302.5  721.46     312  724.94   321.4  727.82   330.9  730.23
   359.3  735.37   378.2  739.58   387.6  742.25   397.1  745.76   406.6   749.9
#Mann= 3 , 0 , 0
       0      .1       0   226.8    .045       0   283.6      .1       0
Bank Sta=226.8,283.6
XS Rating Curve= 0 ,0
Exp/Cntr=0.3,0.1

Type RM Length L Ch R = 1 ,61001.3 ,222.3,215.6,208.6
XS GIS Cut Line= 3
     1864369.541      496119.262     1864326.833      496274.391
      1864334.75      496501.335
#Sta/Elev= 30
       0   738.4    28.4  731.34    56.8  725.18    66.2  722.61    75.7  720.83
    85.2  720.32    94.6  720.58   113.6  721.88     123   722.3   132.5  722.38
   160.9   721.8   170.4  721.98   179.8   721.9   189.3  721.16   198.8  719.65
   208.2   717.2   217.7  714.08   227.1  711.64   236.6   710.8   246.1  710.82
   255.5  711.11     265  712.88   274.4  716.48   283.9  719.55   293.4  721.39
   302.8  722.84   340.7  727.34   350.1  729.18   359.6  731.86     388  740.84
#Mann= 3 , 0 , 0
       0      .1       0   217.7    .045       0     265      .1       0
#XS Ineff= 2 , 0
           131.5  725.76
Permanent Ineff=
       F       F
Bank Sta=217.7,265
XS Rating Curve= 0 ,0
Exp/Cntr=0.3,0.1

Type RM Length L Ch R = 1 ,60785.7 ,195,196.8,198.6
XS GIS Cut Line= 2
      1864066.46      496257.025     1864181.961      496589.045
#Sta/Elev= 29
       0  761.24     9.8  756.65    19.5  751.61    29.3  745.85    39.1  739.83
    48.8  733.98    58.6  728.65    68.4  724.74    78.1  722.83    87.9   721.9
   107.4  719.85   117.2  718.38   126.9   714.6   136.7  711.45   146.5  710.84
   156.2   710.8   185.5   710.8   195.3   710.9   205.1  711.52   214.8  712.93
   234.4  716.55   273.4  724.01   283.2  725.81     293  727.08   302.7  728.67
   312.5   731.4     332  738.01   341.8  741.08   351.5  744.33
#Mann= 3 , 0 , 0
       0      .1       0   136.7    .045       0   205.1      .1       0
Bank Sta=136.7,205.1
XS Rating Curve= 0 ,0
Exp/Cntr=0.3,0.1

Type RM Length L Ch R = 1 ,60588.9 ,272.4,273.7,274.8
XS GIS Cut Line= 3
      1863894.13      496321.355     1863965.965      496596.332
     1864156.243      496870.637
#Sta/Elev= 30
       0  771.49    39.2  755.65      49  750.13    58.8  742.72    68.6  734.74
    78.4  727.62      98   720.1   107.8  714.46   117.6  711.21   127.4   710.8
   186.2  710.84     196  711.46   205.8  713.23   235.2  721.09     245  722.92
   254.8  724.19   264.6  724.92   274.4  724.97     294  724.23   313.7  724.89
   323.5  725.68   352.9  730.23   372.6  732.79   382.4  734.49   392.2  736.65
   431.5  747.02   451.1  752.73   480.6  761.99   539.5  781.74     618  810.78
#Mann= 3 , 0 , 0
       0      .1       0   117.6    .045       0     196      .1       0
Bank Sta=117.6,196
XS Rating Curve= 0 ,0
Exp/Cntr=0.3,0.1