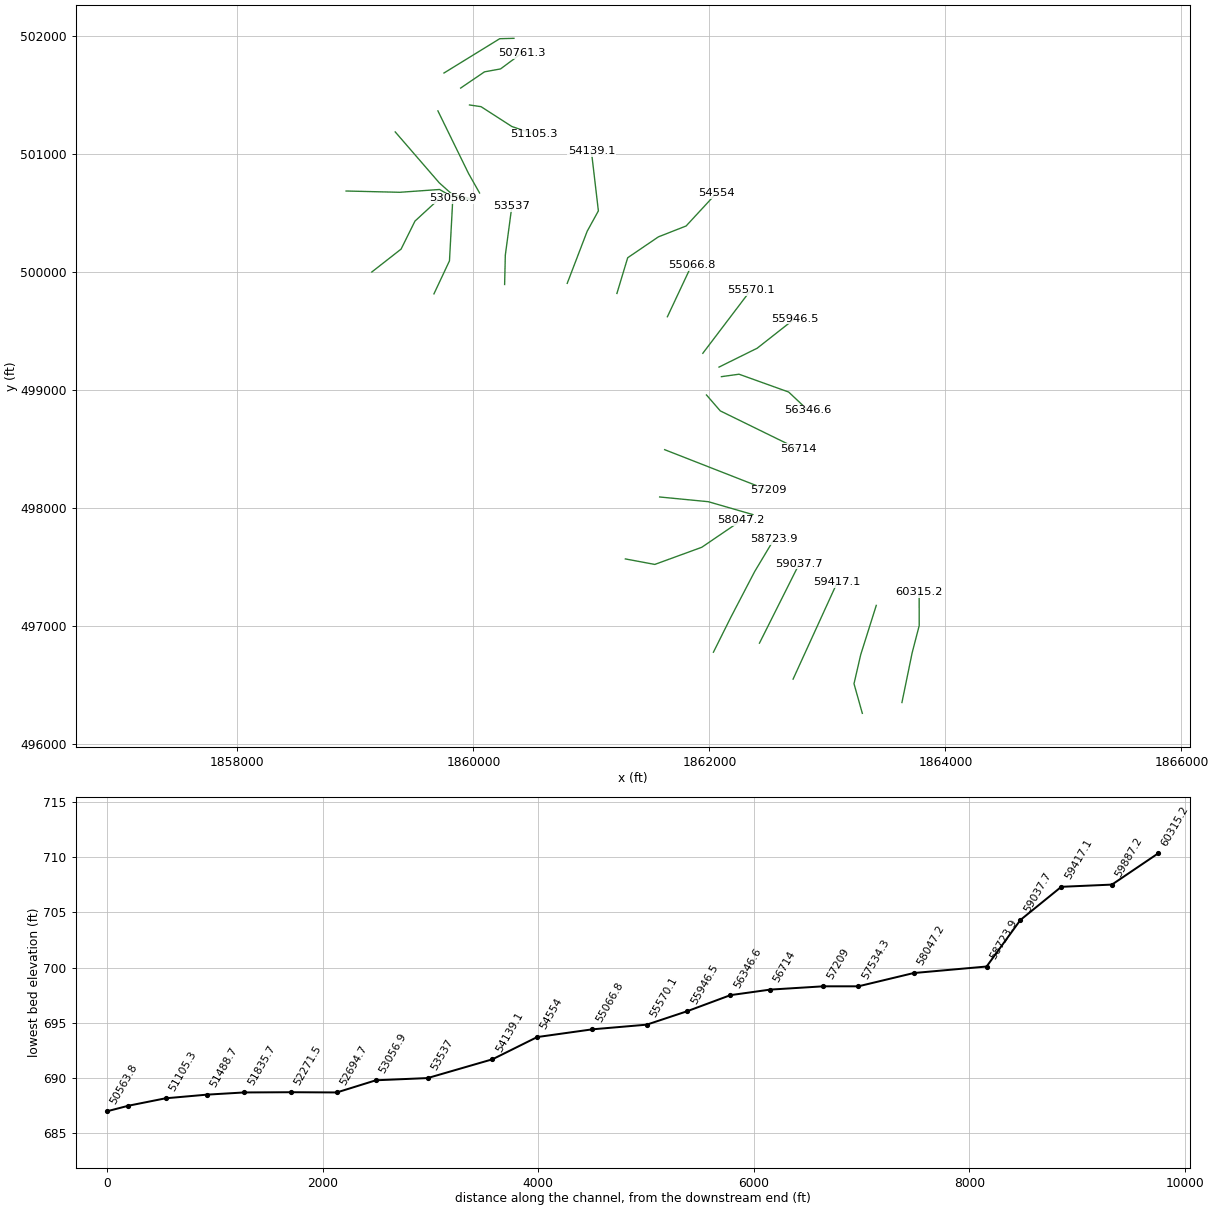
HEC-RAS study BLUECR.prj: BLUECR

--- BLUECR.g01 (geometry) --- (continued)

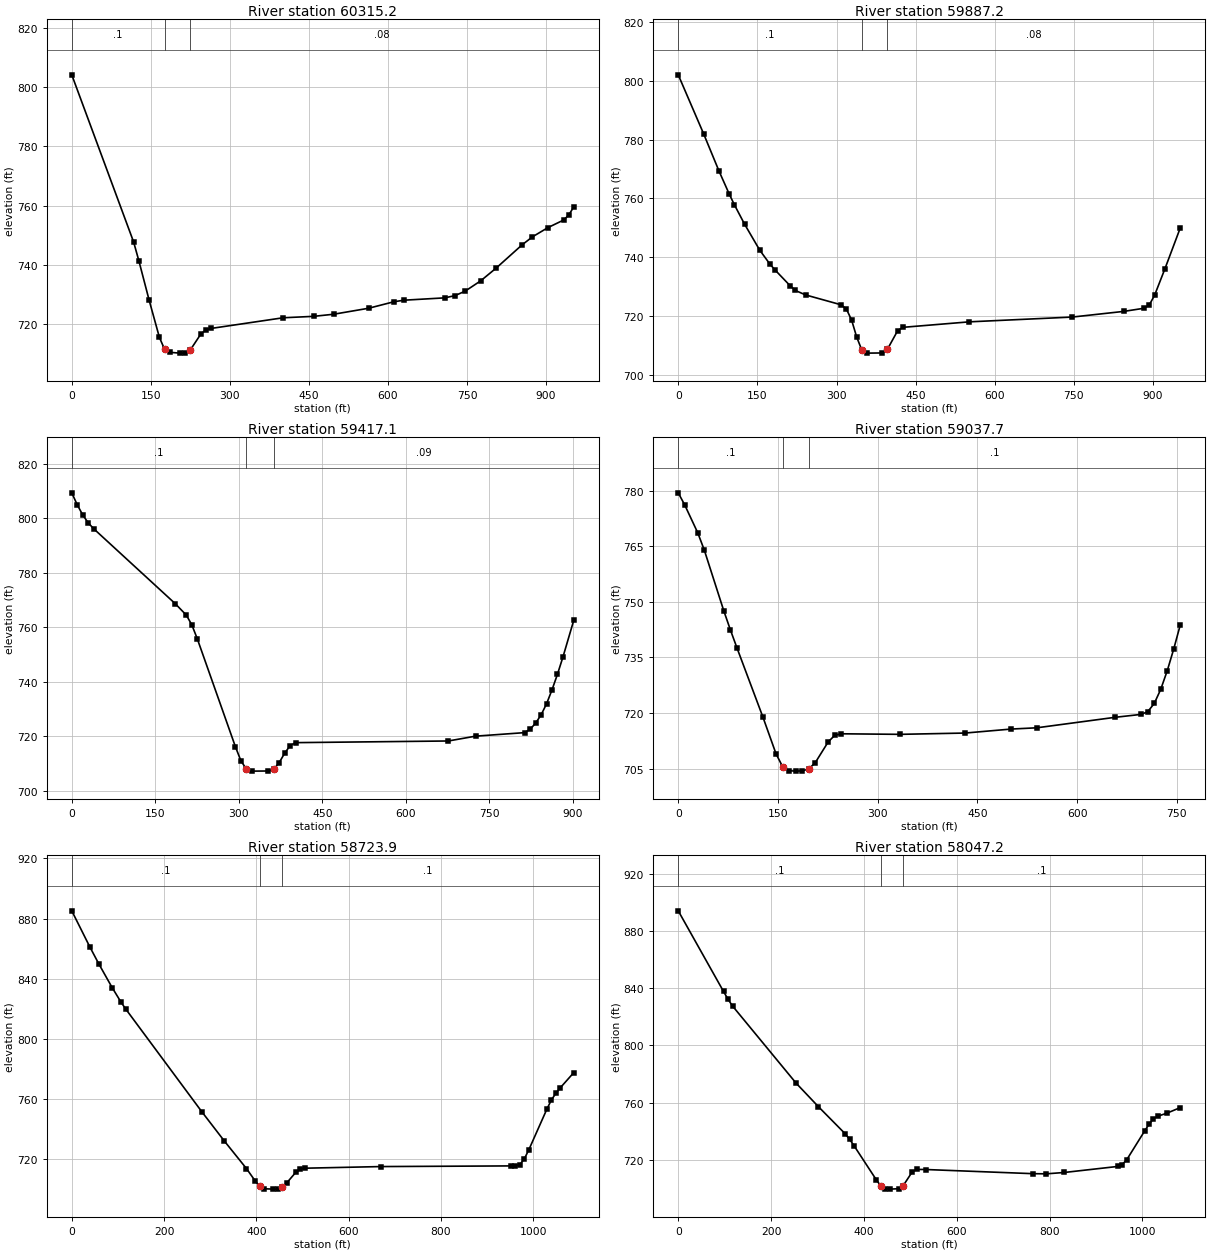
Type RM Length L Ch R = 1 ,60315.2 ,428.4,428,427.4
XS GIS Cut Line= 4
     1863631.488      496351.092     1863718.154      496772.759
     1863777.876      497002.759      1863777.46      497287.342
#Sta/Elev= 30
       0  804.14   117.4  747.77   127.2  741.52   146.8  728.17   166.3  715.62
   176.1  711.61   185.9  710.59   205.5  710.32   215.2  710.33     225   711.4
   244.6  716.68   254.4  718.18   264.2  718.64   401.1  722.24     459  722.72
     497  723.43   563.6  725.46   611.1  727.63   630.1  728.16   707.4  728.95
     727  729.69   746.6  731.23     776   734.7   805.5  739.02   854.6  746.84
   874.2  749.53   903.6  752.64   933.1  755.17   942.9  756.82   952.7  759.68
#Mann= 3 , 0 , 0
       0      .1       0   176.1    .045       0     225     .08       0
Bank Sta=176.1,225
XS Rating Curve= 0 ,0
Exp/Cntr=0.3,0.1

Type RM Length L Ch R = 1 ,59887.2 ,474.6,470.1,465.4
XS GIS Cut Line= 4
     1863295.803      496259.478     1863225.317      496510.519
      1863282.03      496756.144     1863413.975      497174.546
#Sta/Elev= 30
       0  801.95    48.3  781.86    77.3  769.28    96.6  761.51   106.2  757.92
   125.6  751.31   154.5  742.44   173.8   737.7   183.5  735.72   212.5  730.29
   222.1  728.76   241.4  727.25   309.2  723.88   318.9  722.39   328.6  718.72
   338.3  712.91     348  708.52   357.7   707.5   386.8  707.56   396.5  708.82
   415.9  715.12   425.6  716.25   551.8  718.12   746.8  719.74   844.3  721.66
   883.3  722.74   893.1  723.96   902.8  727.12   922.3  736.06   951.6  750.03
#Mann= 3 , 0 , 0
       0      .1       0     348    .045       0   396.5     .08       0
Bank Sta=348,396.5
XS Rating Curve= 0 ,0
Exp/Cntr=0.3,0.1

Type RM Length L Ch R = 1 ,59417.1 ,380.2,379.4,378.6
XS GIS Cut Line= 2
     1862709.021      496549.524     1863083.637       497369.76
#Sta/Elev= 30
       0   809.3     9.8  804.92    19.6  801.24    29.4  798.33    39.2  796.17
   186.2   768.6   205.8  764.46   215.6  760.91   225.4  755.82     294  716.18
   303.8  711.07   313.6  708.06   323.4   707.3   352.8  707.35   362.6  707.91
   372.5  710.42   382.3  713.85   392.1  716.62   401.9  717.74   676.3  718.35
   725.3  720.12   813.5  721.41   823.3  722.66   833.1   724.9   842.9  727.92
   852.7  731.98   862.5   737.1   872.3  742.82   882.1   749.1   901.7  762.69
#Mann= 3 , 0 , 0
       0      .1       0   313.6    .045       0   362.6     .09       0
Bank Sta=313.6,362.6
XS Rating Curve= 0 ,0
Exp/Cntr=0.3,0.1

Type RM Length L Ch R = 1 ,59037.7 ,314.1,313.8,313.4
XS GIS Cut Line= 2
     1862423.994      496854.379     1862762.536      497529.379
#Sta/Elev= 30
       0  779.43     9.8  776.14    29.4  768.62    39.2  763.97    68.6  747.53
    78.5   742.4    88.3  737.58   127.5  718.82   147.1  708.96   156.9  705.53
   166.7  704.41   176.5   704.3   186.3  704.36   196.1  704.87     206  706.56
   225.6  712.21   235.4  713.96   245.2  714.38   333.4  714.23   431.5  714.58
   500.2  715.65   539.4     716   657.1  718.83   696.3  719.62   706.1  720.35
   715.9  722.56   725.7   726.4   735.5  731.43   745.3  737.34   755.1  743.81
#Mann= 3 , 0 , 0
       0      .1       0   156.9    .045       0   196.1      .1       0
Bank Sta=156.9,196.1
XS Rating Curve= 0 ,0
Exp/Cntr=0.3,0.1

Type RM Length L Ch R = 1 ,58723.9 ,693.3,676.7,659.9
XS GIS Cut Line= 4
     1862033.809       496777.74     1862181.179      497073.182
     1862382.749      497460.064     1862548.132      497736.073
#Sta/Elev= 30
       0  885.15    38.8  861.37    58.3  850.04    87.4  834.16   106.8  824.39
   116.5  820.04   281.6  751.66   330.2  732.27   378.6  713.78     398  705.34
   407.7  701.87   417.4  700.33   436.8  700.09   446.5  700.23   456.2  701.26
   465.9  704.22   485.3  711.18     495  713.36   504.6     714   669.5  715.09
   951.7  715.53   961.4  715.58   971.2  716.39   980.9  720.23   990.7  726.31
  1029.7  753.25  1039.4   759.3  1049.2  763.82  1058.9  767.51  1088.2  777.62
#Mann= 3 , 0 , 0
       0      .1       0   407.7    .045       0   456.2      .1       0
Bank Sta=407.7,456.2
XS Rating Curve= 0 ,0
Exp/Cntr=0.3,0.1

Type RM Length L Ch R = 1 ,58047.2 ,523,512.9,502.7
XS GIS Cut Line= 4
     1861287.644      497568.218     1861536.891      497521.633
     1861934.808      497666.772     1862269.224      497894.104
#Sta/Elev= 30
       0  894.08    97.5  837.74   107.3  832.22     117  827.51   253.6  773.71
   301.7  757.23   359.4  738.27   369.1  734.38   378.7  729.84   426.8  705.95
   436.5  701.64   446.1  699.71   455.7   699.5     475  699.79   484.6  701.94
   503.8  711.44   513.5  713.27   532.7  713.22   763.8  710.31   792.7  710.19
   831.2  711.13   946.7  715.36   956.3  716.71     966     720  1004.5  740.07
  1014.1  744.84  1023.7  748.74  1033.4  750.53  1052.6   752.6  1081.5  756.51
#Mann= 3 , 0 , 0
       0      .1       0   436.5    .045       0   484.6      .1       0
Bank Sta=436.5,484.6
XS Rating Curve= 0 ,0
Exp/Cntr=0.3,0.1

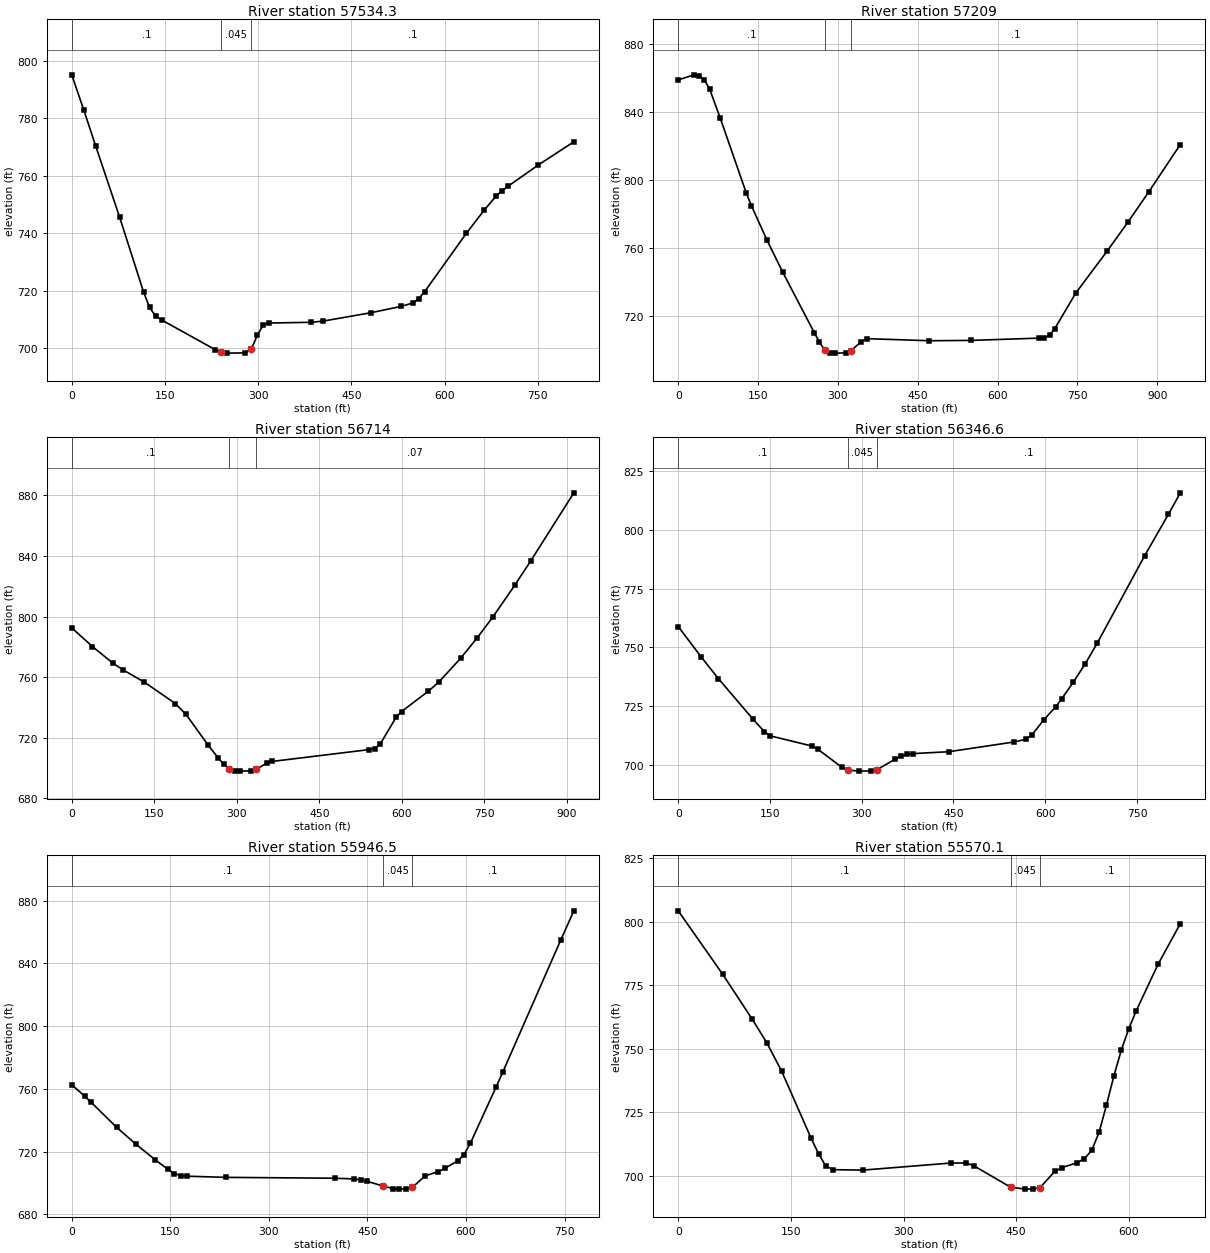
Type RM Length L Ch R = 1 ,57534.3 ,331.5,325.3,319.1
XS GIS Cut Line= 3
      1861578.02      498093.236     1861990.346      498053.305
     1862368.819       497943.93
#Sta/Elev= 30
       0  795.17    19.3  782.96    38.5  770.41    77.1  745.58   115.6  719.56
   125.2  714.21   134.9   711.2   144.5  709.86   231.2  699.47   240.8  698.52
   250.5   698.3   279.4  698.38     289  699.74   298.6  704.45   308.3  708.15
   317.9  708.78   385.4  709.03   404.6  709.45   481.5  712.36   529.6  714.54
   548.8  715.74   558.4  717.26     568  719.69   635.3  740.04   664.1  748.13
   683.3  753.01   692.9  754.87   702.5  756.41   750.6  763.74   808.2  771.86
#Mann= 3 , 0 , 0
       0      .1       0   240.8    .045       0     289      .1       0
Bank Sta=240.8,289
XS Rating Curve= 0 ,0
Exp/Cntr=0.3,0.1

Type RM Length L Ch R = 1 ,57209   ,496.7,495,493
XS GIS Cut Line= 2
     1861620.526      498494.191     1862498.998      498150.441
#Sta/Elev= 30
       0  858.87    29.5  861.88    39.3  861.37    49.1  858.97      59  853.49
    78.6  836.74   127.7  792.53   137.6  784.86     167  764.56   196.5  745.78
   255.5  710.39   265.3  704.82   275.1  700.14     285  698.39   294.8   698.3
   314.4  698.43   324.3  699.57   343.9  705.12   353.8  706.82   471.7  705.58
   550.3  705.78     678  707.12   687.8  707.38   697.7  708.76   707.5  712.74
   746.8  733.56   805.8  758.27   845.1  775.38   884.4  793.24   943.3  820.92
#Mann= 3 , 0 , 0
       0      .1       0   275.1    .045       0   324.3      .1       0
Bank Sta=275.1,324.3
XS Rating Curve= 0 ,0
Exp/Cntr=0.3,0.1

Type RM Length L Ch R = 1 ,56714   ,364.7,367.4,370.2
XS GIS Cut Line= 3
     1861974.955      498957.703     1862091.955       498822.91
     1862751.087      498500.019
#Sta/Elev= 30
       0  792.47    37.6  780.22    75.2  769.09    93.9  764.66   131.5  756.81
   188.3  742.59   207.8  735.38     247  715.54   266.6  706.52   276.4   702.4
   286.1  699.44   295.9   698.2   305.7     698   325.3  698.19   335.1  699.08
   354.6  703.39   364.4   704.4   540.6  712.21   550.4  712.93   560.2  715.65
   589.5  733.52   599.3   737.3   648.2  750.77   667.8  757.04     707  772.59
   736.3   785.7   765.7  799.91   804.8   820.5   834.2  836.75   912.5  881.64
#Mann= 3 , 0 , 0
       0      .1       0   286.1    .045       0   335.1     .07       0
Bank Sta=286.1,335.1
XS Rating Curve= 0 ,0
Exp/Cntr=0.3,0.1

Type RM Length L Ch R = 1 ,56346.6 ,377.2,400.1,422.6
XS GIS Cut Line= 4
     1862101.691      499112.981      1862250.65      499133.814
     1862671.483      498982.773     1862833.983      498829.648
#Sta/Elev= 30
       0  758.87    37.6  745.93    65.8   736.7   122.2  719.56     141  714.21
   150.4  712.48   218.4  708.15   228.2   706.8     267  699.21   276.8  697.95
   296.2   697.5   315.6  697.63   325.4  698.19   354.5  702.55   364.2  703.77
     374  704.56   383.7  704.94     442  705.73   548.9  709.86   568.4  711.01
   578.1  712.82   597.5  719.24   616.9  724.74   626.6  728.09   646.1  735.31
   665.5  743.12   684.9  751.76   762.6  788.95   801.4   806.5   820.8   815.6
#Mann= 3 , 0 , 0
       0      .1       0   276.8    .045       0   325.4      .1       0
Bank Sta=276.8,325.4
XS Rating Curve= 0 ,0
Exp/Cntr=0.3,0.1

Type RM Length L Ch R = 1 ,55946.5 ,370.5,376.4,382.1
XS GIS Cut Line= 3
     1862081.379      499194.115     1862405.019      499354.272
     1862721.871      499603.244
#Sta/Elev= 30
       0  762.63    19.5   755.4    29.3  751.51    68.3  735.46    97.6  724.72
   126.9   714.8   146.4  708.66   156.2     706   165.9  704.65   175.7   704.3
   234.2  703.56   400.4     703   429.9  702.54   439.7  701.99   449.6  701.02
   474.1 697.965   488.9  696.41   498.7  696.05   508.5  696.08   518.4  697.22
     538  704.54   557.7  707.21   567.5  709.24   587.2  714.02     597  718.14
   606.8  725.49   646.1  761.52     656  770.75   744.4  855.19   764.1  873.59
#Mann= 3 , 0 , 0
       0      .1       0   474.1    .045       0   518.4      .1       0
Bank Sta=474.1,518.4
XS Rating Curve= 0 ,0
Exp/Cntr=0.3,0.1

Type RM Length L Ch R = 1 ,55570.1 ,498.6,503.3,508
XS GIS Cut Line= 2
     1861943.956      499311.093     1862348.123      499843.732
#Sta/Elev= 30
       0  804.29      59  779.42    98.3  761.78     118  752.36   137.7  741.23
     177   714.8   186.8  708.78   196.6  703.87   206.5  702.48   245.8  702.31
   363.8  705.11   383.5  705.12   393.3  704.06   442.5  695.62   462.1  694.83
     472  694.87   481.8  695.43   501.5  701.81   511.3  703.33     531  705.18
   540.8   706.8   550.6  710.04   560.5  717.26   570.3  727.91   580.1  739.32
     590  749.52   599.8  757.79   609.6   764.8   639.1  783.35   668.6  799.25
#Mann= 3 , 0 , 0
       0      .1       0   442.5    .045       0   481.8      .1       0
Bank Sta=442.5,481.8
XS Rating Curve= 0 ,0
Exp/Cntr=0.3,0.1

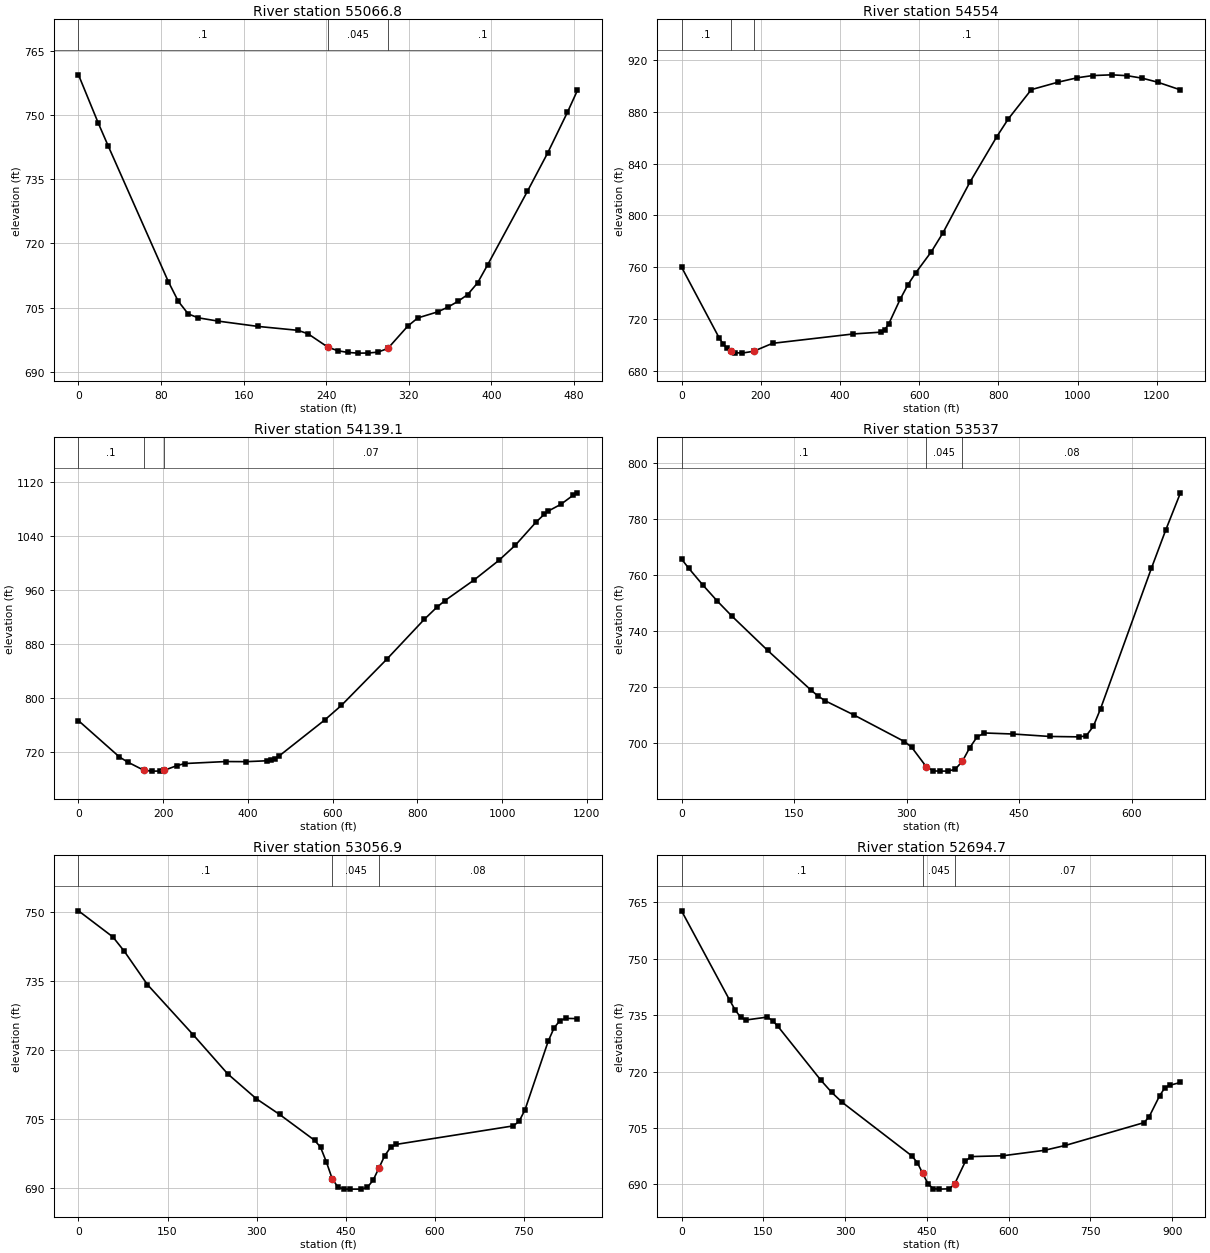
Type RM Length L Ch R = 1 ,55066.8 ,509.3,512.8,516
XS GIS Cut Line= 2
     1861643.748      499620.832     1861849.303      500058.332
#Sta/Elev= 30
       0  759.36    19.3  748.02      29  742.64      87  711.12    96.7   706.5
   106.3  703.56     116  702.65   135.4  701.88     174  700.64   212.7  699.73
   222.4  698.92   241.7  695.79   251.4  694.96     261  694.57   270.7  694.41
   280.4  694.43     290  694.64   299.7   695.5     319  700.71   328.7  702.62
     348  704.04   357.7  705.12   367.4  706.46     377  708.06   386.7  710.82
   396.4  715.02     435  732.21   454.4  741.05   473.7  750.62   483.4  755.73
#Mann= 3 , 0 , 0
       0      .1       0   241.7    .045       0   299.7      .1       0
Bank Sta=241.7,299.7
XS Rating Curve= 0 ,0
Exp/Cntr=0.3,0.1

Type RM Length L Ch R = 1 ,54554   ,416.5,414.9,413.3
XS GIS Cut Line= 5
     1861215.921      499818.339     1861307.214      500120.883
     1861567.502      500297.849     1861802.335      500390.037
      1862057.89      500666.426
#Sta/Elev= 30
       0  760.18    95.8  705.04   105.3  700.74   114.9  697.43   124.5  695.34
   134.1  694.11   152.3  693.71     182  695.14   229.8  701.28     434  708.53
   502.9  709.89   512.7  711.71   522.6  715.96   552.1   735.4   571.8  746.66
   591.4  755.78   630.8  772.08   659.9  786.55   727.8  825.62   795.7  860.76
   824.8  874.52     883  897.16   950.6  902.93   998.9  906.31  1037.5  908.01
  1085.7  908.59  1124.4  907.94    1163     906  1201.6  902.94  1259.5  896.96
#Mann= 3 , 0 , 0
       0      .1       0   124.5    .045       0     182      .1       0
Bank Sta=124.5,182
XS Rating Curve= 0 ,0
Exp/Cntr=0.3,0.1

Type RM Length L Ch R = 1 ,54139.1 ,596.7,602.1,607.2
XS GIS Cut Line= 4
     1860794.772      499904.003     1860964.043      500345.843
     1861058.817      500518.101     1860999.633      501022.927
#Sta/Elev= 30
       0  766.46    96.6  712.72   115.9   705.2   154.5  692.93   173.8   691.7
   193.1  691.79   202.8  692.98   231.8  699.74   251.1  702.95   347.6  705.89
   395.9  705.71   444.2  707.02   453.8  707.75   463.5  709.89   473.2  713.91
   581.3  767.44   620.6  788.98   728.4  857.84   816.4  916.54   845.7  934.26
   865.3  944.37   933.7  974.73   992.3  1003.8  1031.4 1026.38  1080.3 1060.58
  1099.8 1072.25  1109.6 1077.13    1139 1087.01  1168.3  1100.6    1178 1103.98
#Mann= 3 , 0 , 0
       0      .1       0   154.5    .045       0   202.8     .07       0
Bank Sta=154.5,202.8
XS Rating Curve= 0 ,0
Exp/Cntr=0.3,0.1

Type RM Length L Ch R = 1 ,53537   ,478.2,480.1,481.8
XS GIS Cut Line= 3
     1860264.189       499894.09      1860270.11      500142.671
       1860325.3      500555.576
#Sta/Elev= 30
       0  765.81     9.6  762.52    28.7  756.44    47.8  750.76    66.9  745.48
   114.8  733.16   172.1  719.08   181.7  716.92   191.3  715.17   229.5  710.12
   297.1  700.58   306.8  698.55   326.2  691.61   335.8  690.07   344.9     690
   355.2  690.02   364.9  690.66   374.6   693.6   384.3  698.39     394   702.2
   403.7  703.64   442.4  703.26   490.8  702.39   529.6  702.25   539.3  702.58
     549  705.98   558.7  712.33   626.5  762.55   645.8  776.36   665.2  789.48
#Mann= 3 , 0 , 0
       0      .1       0   326.2    .045       0   374.6     .08       0
Bank Sta=326.2,374.6
XS Rating Curve= 0 ,0
Exp/Cntr=0.3,0.1

Type RM Length L Ch R = 1 ,53056.9 ,371.2,362.2,352.9
XS GIS Cut Line= 3
     1859665.363      499814.906     1859796.794      500094.881
       1859825.2      500625.351
#Sta/Elev= 30
       0  750.15      58  744.48    77.3  741.36     116  734.17   193.3  723.26
   251.3   714.8   299.6   709.4   338.8  705.99   397.8  700.38   407.7   698.9
   417.5  695.72   427.3  692.08   437.2   690.2     447  689.82   456.8   689.8
   476.5   689.8   486.4  690.16   496.2   691.7     506  694.35   515.9  697.06
   525.7  698.85   535.6  699.51   732.3  703.51   742.1  704.48     752  706.95
   791.3  721.89   801.2  724.78     811  726.35   820.8  726.82   840.5  726.78
#Mann= 3 , 0 , 0
       0      .1       0   427.3    .045       0     506     .08       0
Bank Sta=427.3,506
XS Rating Curve= 0 ,0
Exp/Cntr=0.3,0.1

Type RM Length L Ch R = 1 ,52694.7 ,448.6,423.2,397.4
XS GIS Cut Line= 4
     1859138.807       500000.35     1859386.724        500194.1
     1859504.432        500431.6     1859751.307      500658.684
#Sta/Elev= 30
       0  762.78    88.5  738.94    98.3  736.43   108.2  734.47     118  733.72
   157.3  734.49   167.2  733.54     177  731.99   255.6  717.69   275.3  714.48
     295  711.77   422.6  697.53   432.4  695.77   442.3  692.94   452.1   690.1
   461.9  688.82   471.7   688.7   491.4  688.78   501.2  690.14   520.8  696.11
   530.6  697.36   589.3  697.58     666  699.04   704.3  700.34   848.1  706.39
   857.6  707.92   876.8   713.5   886.4  715.66     896  716.36   915.2   717.1
#Mann= 3 , 0 , 0
       0      .1       0   442.3    .045       0   501.2     .07       0
Bank Sta=442.3,501.2
XS Rating Curve= 0 ,0
Exp/Cntr=0.3,0.1

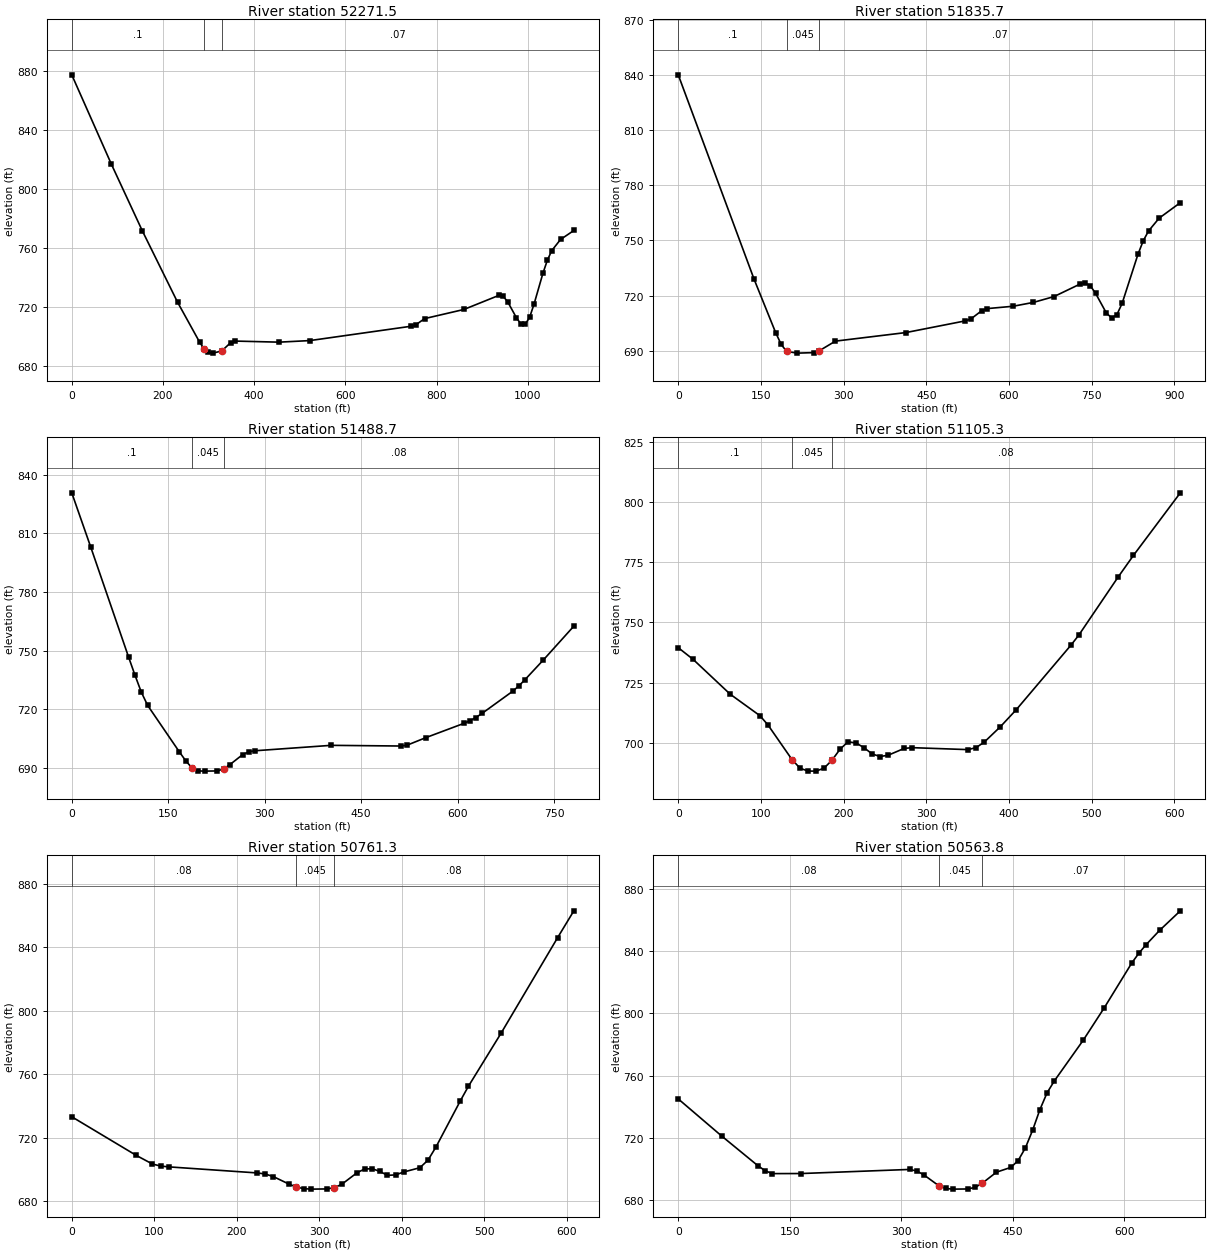
Type RM Length L Ch R = 1 ,52271.5 ,454.6,435.8,416.9
XS GIS Cut Line= 5
     1858920.495      500686.463     1859374.884      500675.574
     1859712.717      500699.379     1859811.773      500642.697
     1860001.731      500604.921
#Sta/Elev= 30
       0  877.47      87  816.76   154.7  771.68   232.1  723.19   280.4  696.14
   290.1  691.62   299.8  689.18   309.5  688.72   328.8  690.18   348.1  695.71
   357.8   696.9   454.5  696.16   522.2  697.23   744.8  706.98   754.5  707.93
   773.8  712.14   859.8  718.32   936.4  727.86     946  727.24   955.7  723.67
   975.1   712.7   984.8  708.53   994.5  708.29  1004.2  713.16  1013.8  722.05
  1033.2  742.89  1042.9  751.71  1052.6  758.28  1071.9  765.82    1101  771.89
#Mann= 3 , 0 , 0
       0      .1       0   290.1    .045       0   328.8     .07       0
Bank Sta=290.1,328.8
XS Rating Curve= 0 ,0
Exp/Cntr=0.3,0.1

Type RM Length L Ch R = 1 ,51835.7 ,352.8,347,341.2
XS GIS Cut Line= 4
     1859337.148      501187.213     1859710.064      500755.963
     1859820.727      500656.902     1860007.981      500614.296
#Sta/Elev= 30
       0  840.08   137.6  728.89   176.9  699.71   186.8   693.4   196.6  689.62
   216.2   688.7   245.7  688.97   255.6  689.94   285.1  695.23   412.8  699.88
     521  706.26   530.8  707.28   550.5  711.79   560.3  712.92   607.3  714.19
   644.4   716.3   681.5  719.45   728.2  726.17   737.8  726.81   747.5  725.37
   757.1  721.17   776.3  710.65   785.9  707.86   795.5  709.53   805.1  715.72
   833.9  742.45   843.5  749.84   853.1  755.15   872.3  762.12   910.7  770.54
#Mann= 3 , 0 , 0
       0      .1       0   196.6    .045       0   255.6     .07       0
Bank Sta=196.6,255.6
XS Rating Curve= 0 ,0
Exp/Cntr=0.3,0.1

Type RM Length L Ch R = 1 ,51488.7 ,371,383.4,395.6
XS GIS Cut Line= 3
     1859698.759      501365.518     1859958.134       500835.31
     1860051.884      500669.685
#Sta/Elev= 30
       0  830.73    29.5     803    88.5  746.64    98.4  737.41   108.2   728.8
     118  722.07   167.2  698.37   177.1  693.83   186.9  690.14   196.8   688.6
   206.6   688.5   226.3   688.6   236.1  689.64   245.9  691.84   265.6  696.92
   275.4   698.4   285.3  698.92   403.3  701.68   511.6  701.33   521.4  701.77
   550.9  705.67   609.3  712.86   618.8  714.21   628.3   715.9   637.8  717.98
   685.4  729.29   694.9     732   704.4  735.16     733  745.24   780.6   762.6
#Mann= 3 , 0 , 0
       0      .1       0   186.9    .045       0   236.1     .08       0
Bank Sta=186.9,236.1
XS Rating Curve= 0 ,0
Exp/Cntr=0.3,0.1

Type RM Length L Ch R = 1 ,51105.3 ,327,344,361
XS GIS Cut Line= 4
     1859966.625      501415.675     1860064.388      501401.275
     1860325.132      501233.384     1860512.632      501168.279
#Sta/Elev= 30
       0  739.51      18  734.64    62.9  720.15    98.8  711.23   108.5   707.4
   137.6  692.99   147.3   689.4     157  688.19   166.7  688.17   176.4  689.41
     186  692.71   195.7  697.26   205.4  700.38   215.1  699.88   224.8  697.91
   234.5  695.32   244.2  694.25   253.9  694.77   273.3  697.61     283  697.93
   350.8  697.11   360.5  697.99   370.2  700.23   389.6  706.59   408.9   713.7
   475.1  740.55   484.6  744.73   531.8   768.7   550.7  777.88   607.4   803.9
#Mann= 3 , 0 , 0
       0      .1       0   137.6    .045       0     186     .08       0
Bank Sta=137.6,186
XS Rating Curve= 0 ,0
Exp/Cntr=0.3,0.1

Type RM Length L Ch R = 1 ,50761.3 ,189,197.5,205.8
XS GIS Cut Line= 4
     1859891.451      501558.904     1860093.534      501696.404
     1860229.646      501721.231     1860411.243      501855.779
#Sta/Elev= 30
       0  733.09    78.2  708.75    97.8  703.32   107.6  702.05   117.3  701.53
   224.9   697.7   234.6  697.03   244.4   695.4   262.9  690.79   272.1  688.86
   281.3  687.79   290.5   687.5     309  687.62   318.2  688.38   327.4  690.55
   345.9  697.82   355.1  700.19   364.3  700.35   373.6  698.65   382.8  696.18
   392.6  696.46   402.4  698.27   422.1  700.99   431.9  705.72   441.7  714.12
   471.2  743.16     481  752.34   520.4   785.6   589.1  845.91   608.8  862.83
#Mann= 3 , 0 , 0
       0     .08       0   272.1    .045       0   318.2     .08       0
Bank Sta=272.1,318.2
XS Rating Curve= 0 ,0
Exp/Cntr=0.3,0.1

Type RM Length L Ch R = 1 ,50563.8 ,33.8,33.8,33.8
XS GIS Cut Line= 3
     1859750.271      501686.571     1860222.701      501977.307
     1860343.534      501980.432
#Sta/Elev= 30
       0  745.04    58.4  721.18     107  702.14   116.8  698.87   126.5  696.98
   165.4  697.03   311.4  699.67   321.2  698.65   330.9  696.03   350.4  689.26
   360.1  687.41   369.8     687   389.3   687.1     399  688.05   408.7  690.65
   428.2   697.9   447.7  701.01   457.4  705.41   467.1   713.5   476.9  724.95
   486.6  738.08   496.3  748.94   506.1  756.62     545  782.82   573.3  803.68
   610.5  832.63   619.8  838.73   629.1  844.02   647.7  853.44   675.6  866.03
#Mann= 3 , 0 , 0
       0     .08       0   350.4    .045       0   408.7     .07       0
Bank Sta=350.4,408.7
XS Rating Curve= 0 ,0
Exp/Cntr=0.3,0.1