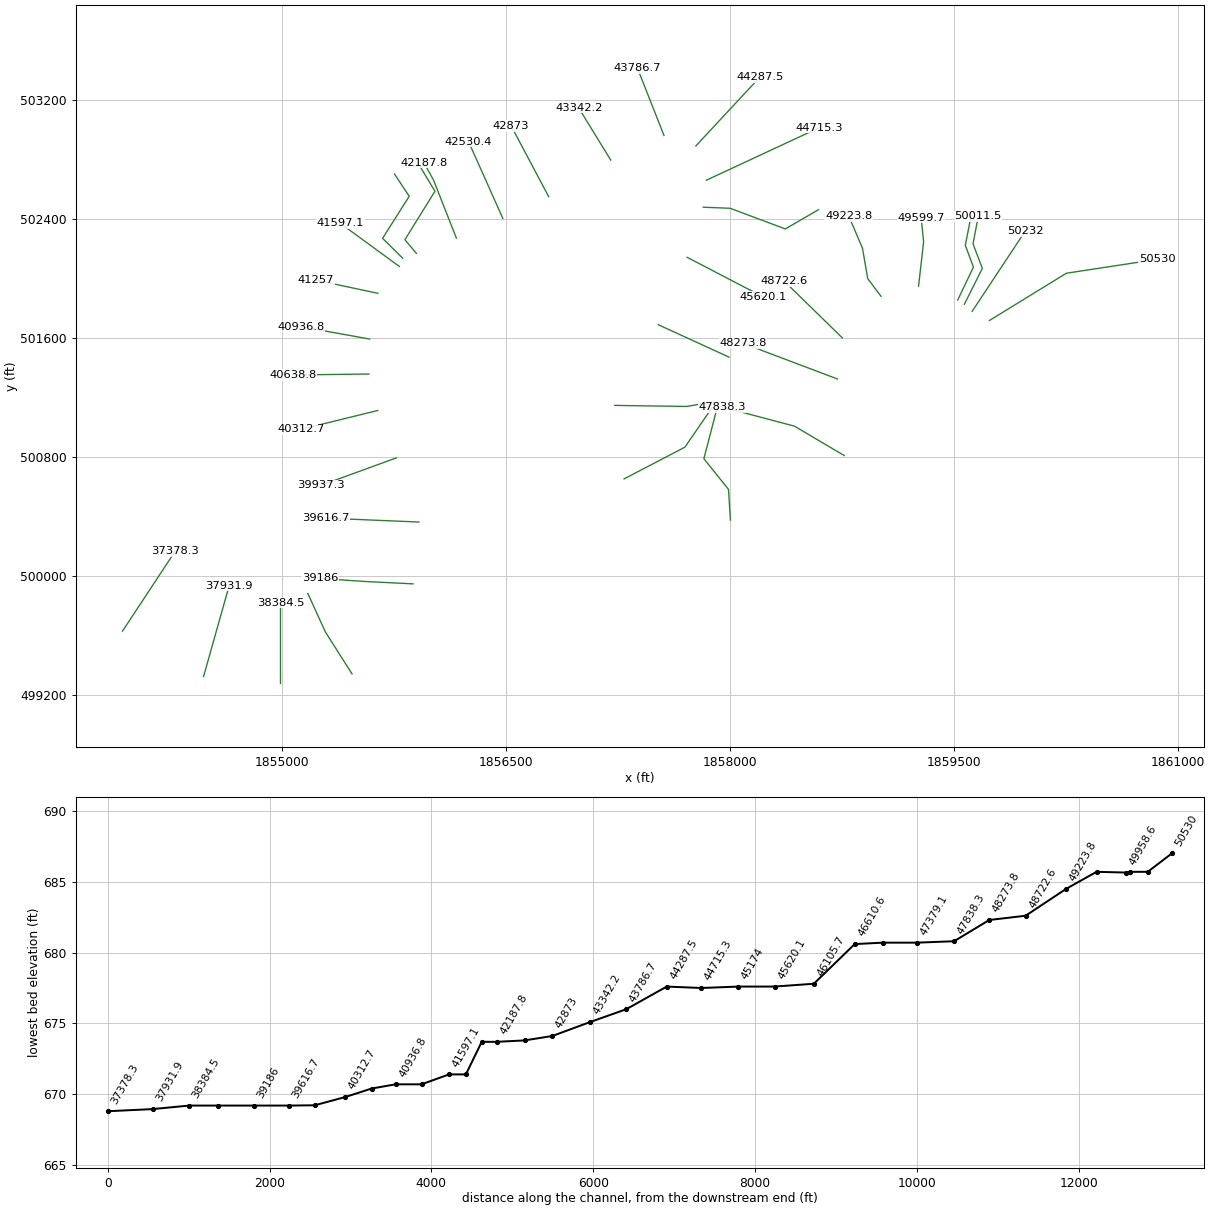
HEC-RAS study BLUECR.prj: BLUECR

--- BLUECR.g01 (geometry) --- (continued)

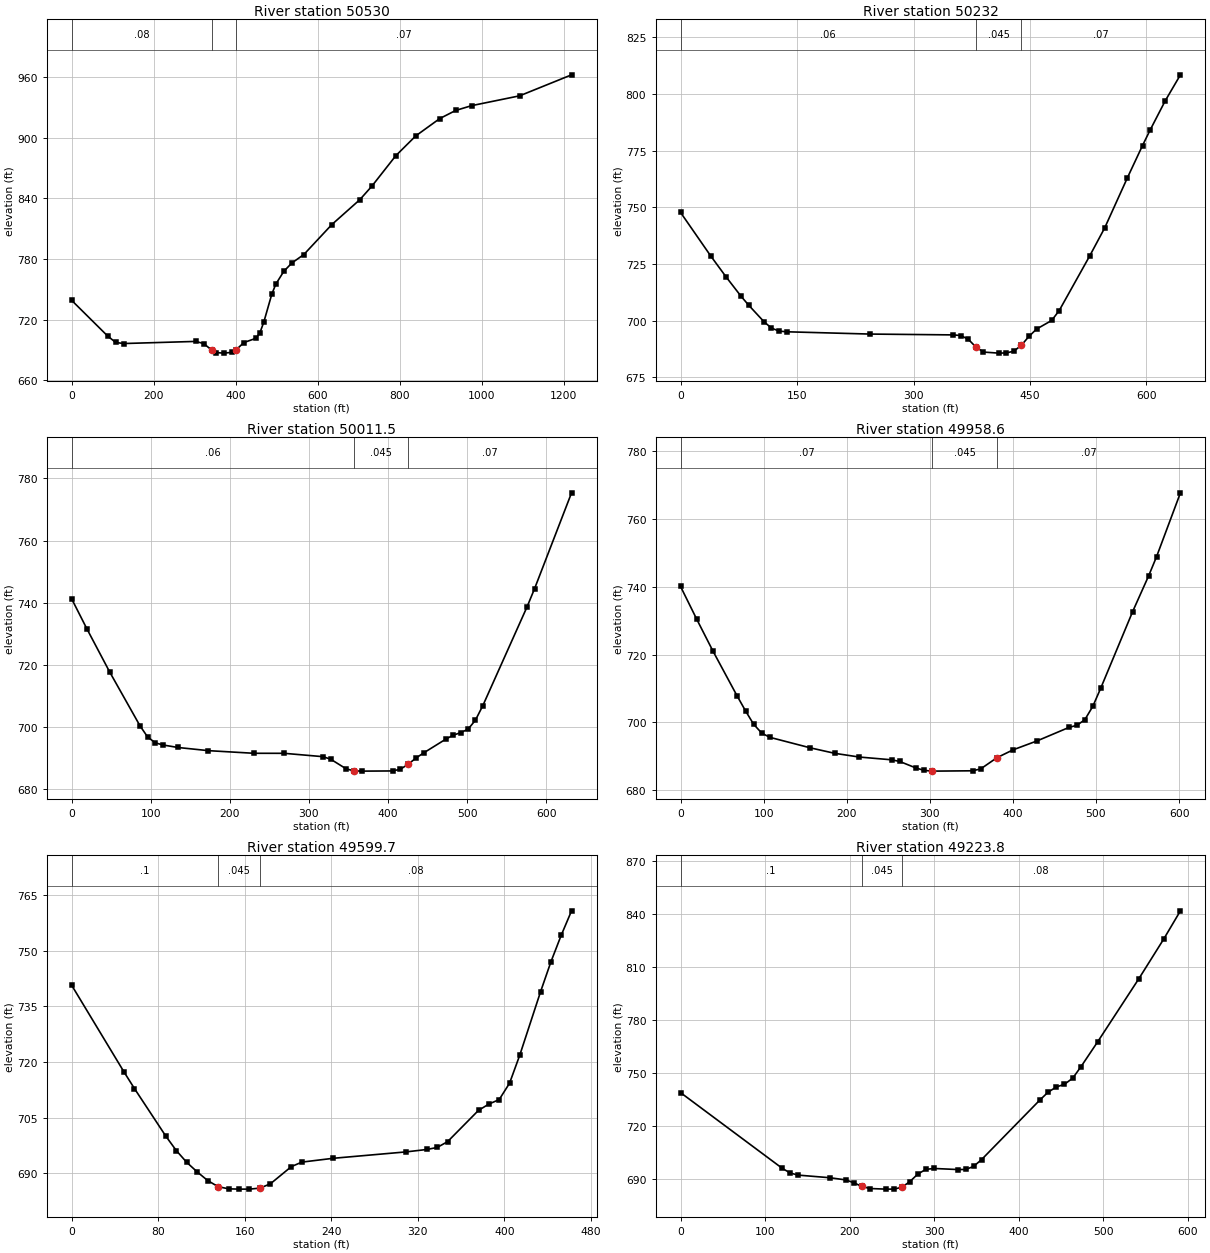
Type RM Length L Ch R = 1 ,50530   ,288.2,298,307.9
XS GIS Cut Line= 3
     1859736.937      501717.682     1860252.215      502035.293
     1860858.986      502128.175
#Sta/Elev= 30
       0  739.16    87.9  703.87   107.4  697.55   126.9  696.48   302.6  698.58
   322.2  696.43   341.7  689.91   351.5  687.58     371     687   390.5  687.75
   400.3  689.96   419.8  697.42   449.1  701.63   458.9  706.89   468.6  717.74
   488.2  745.46   497.9  755.22   517.4  767.86     537   776.1   566.2  784.46
   634.5  814.09   702.7  838.67     732  851.99   790.4  882.12   839.1  901.72
   897.6  918.85   936.6  926.91   975.6  931.66  1092.5  941.36  1219.1  962.11
#Mann= 3 , 0 , 0
       0     .08       0   341.7    .045       0   400.3     .07       0
Bank Sta=341.7,400.3
XS Rating Curve= 0 ,0
Exp/Cntr=0.3,0.1

Type RM Length L Ch R = 1 ,50232   ,198.9,220.5,241.6
XS GIS Cut Line= 2
     1859621.312      501779.043     1859975.479      502316.543
#Sta/Elev= 30
       0  747.78      39  728.51    58.5   719.4      78  710.76    87.8  706.83
   107.3  699.62     117  696.76   126.8  695.43   136.5  695.12   243.8  694.11
   351.1  693.74   360.9  693.46   370.6  691.79   380.4  688.37   390.1  686.17
   409.6   685.7   419.4  685.78   429.1  686.54   438.9  689.17   448.6  693.05
   458.4   696.3   477.9  700.11   487.6  704.47   526.7  728.46   546.2  740.95
   575.4  763.04   594.9  777.29   604.7  784.12   624.2  797.05   643.7  808.47
#Mann= 3 , 0 , 0
       0     .06       0   380.4    .045       0   438.9     .07       0
Bank Sta=380.4,438.9
XS Rating Curve= 0 ,0
Exp/Cntr=0.3,0.1

Type RM Length L Ch R = 1 ,50011.5 ,53,52.9,52.8
XS GIS Cut Line= 4
     1859569.673      501827.064     1859689.673       502067.62
     1859627.436      502232.626     1859662.048      502416.453
#Sta/Elev= 30
       0  741.22    19.2  731.58      48  717.69    86.4  700.31      96  696.73
   105.6  694.84   115.2  694.14   134.4  693.32   172.8   692.3   230.4  691.45
   268.8  691.44   317.8  690.36   327.6  689.54   347.2  686.43     357  685.78
   366.8   685.7     406  685.76   415.8  686.32   425.6  687.92   435.4  689.91
   445.2  691.58   473.2  696.01   482.6  697.29   491.9  698.09   501.3  699.21
   510.6  702.11     520  706.81   576.1  738.74   585.5  744.55   632.2  775.38
#Mann= 3 , 0 , 0
       0     .06       0     357    .045       0   425.6     .07       0
Bank Sta=357,425.6
XS Rating Curve= 0 ,0
Exp/Cntr=0.3,0.1

Type RM Length L Ch R = 1 ,49958.6 ,369.3,358.9,347.2
XS GIS Cut Line= 4
     1859525.229      501855.953     1859630.229      502076.509
     1859575.769      502222.626     1859614.271      502420.342
#Sta/Elev= 30
       0  740.13    19.5  730.46    39.1  721.03    68.4   707.7    78.2  703.44
    87.9   699.5    97.7  696.87   107.5  695.62   156.3  692.51   185.6   690.9
     215  689.81     254  688.99   263.8   688.5   283.3  686.58     293  685.88
   302.8  685.65   351.5  685.75   361.2   686.3   380.7   689.6   400.2  691.93
     429  694.56   467.4  698.54     477  699.17   486.5   700.8   496.1  704.73
   505.7  710.12   544.1  732.71   563.3  743.23   572.9  748.92   601.6  767.75
#Mann= 3 , 0 , 0
       0     .07       0   302.8    .045       0   380.7     .07       0
Bank Sta=302.8,380.7
XS Rating Curve= 0 ,0
Exp/Cntr=0.3,0.1

Type RM Length L Ch R = 1 ,49599.7 ,369.5,375.9,382.2
XS GIS Cut Line= 3
     1859262.874        501948.3     1859296.728      502246.043
     1859280.235      502407.501
#Sta/Elev= 30
       0  740.65    48.3  717.32      58  712.82      87  699.99    96.7   696.1
   106.3  692.93     116  690.35   125.7  688.02   135.3  686.37     145  685.78
   154.7   685.7   164.3   685.7     174  685.97   183.7  687.14     203  691.76
   212.7  692.98   241.7  694.01   309.2  695.74   328.3  696.39   337.8  696.93
   347.4  698.49     376  706.93   385.6  708.63   395.1  709.83   404.7  714.25
   414.2  721.86   433.3  738.86   442.9  746.94   452.4   754.1     462  760.71
#Mann= 3 , 0 , 0
       0      .1       0   135.3    .045       0     174     .08       0
Bank Sta=135.3,174
XS Rating Curve= 0 ,0
Exp/Cntr=0.3,0.1

Type RM Length L Ch R = 1 ,49223.8 ,487.1,501.3,515.3
XS GIS Cut Line= 4
     1859011.496      501880.476     1858922.732      501999.121
     1858887.578      502203.894     1858795.298      502420.092
#Sta/Elev= 30
       0  739.13   120.4  696.23   129.6  693.65   138.9  692.44   176.5  690.95
   195.4  689.72   204.8  688.12   214.3  686.05   223.7  684.85   242.6   684.5
   252.1   684.5   261.5  685.51     271   688.7   280.4  692.96   289.8  695.64
   299.3   696.2   327.6  695.59   337.1  695.61   346.5  697.36   355.9  701.22
   424.5  734.77   434.3  739.27   444.1  742.28   453.9  743.83   463.7  747.32
   473.5  753.84   493.1  767.84     542   803.7   571.4  826.15     591  842.01
#Mann= 3 , 0 , 0
       0      .1       0   214.3    .045       0   261.5     .08       0
Bank Sta=214.3,261.5
XS Rating Curve= 0 ,0
Exp/Cntr=0.3,0.1

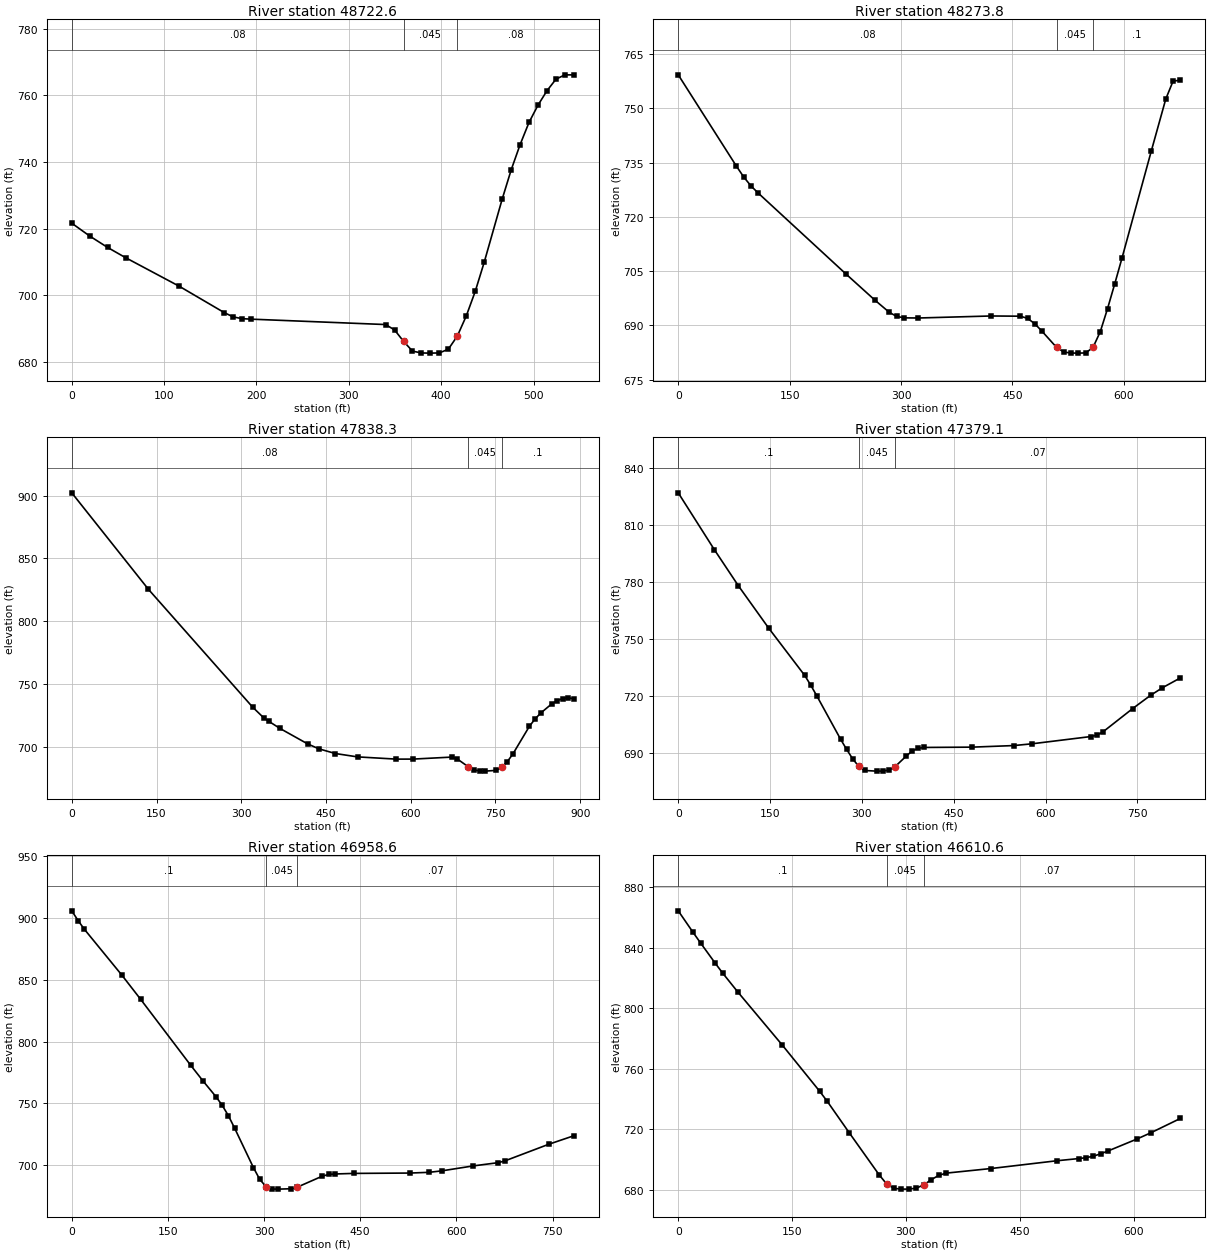
Type RM Length L Ch R = 1 ,48722.6 ,439.4,448.8,458.1
XS GIS Cut Line= 2
     1858752.998      501600.788     1858364.804      501981.344
#Sta/Elev= 30
       0  721.61    19.4  717.76    38.8  714.33    58.2  711.27   116.5  702.66
     165  694.78   174.7  693.48   184.4  692.95   194.2   692.8   339.8  691.18
   349.5  689.56   359.2  686.15   368.9   683.2   378.6  682.65   388.3   682.6
     398  682.66   407.7  683.78   417.4   687.7   427.1  693.74   436.8  701.11
   446.5  709.84     466  728.83   475.7  737.58   485.4   745.2   495.1   751.9
   504.8  757.06   514.5  761.38   524.2  764.84   533.9  766.16   543.6  766.13
#Mann= 3 , 0 , 0
       0     .08       0   359.2    .045       0   417.4     .08       0
Bank Sta=359.2,417.4
XS Rating Curve= 0 ,0
Exp/Cntr=0.3,0.1

Type RM Length L Ch R = 1 ,48273.8 ,433.1,435.5,437.8
XS GIS Cut Line= 2
     1858720.431        501324.9      1858088.14      501564.483
#Sta/Elev= 30
       0  759.31    78.4  734.02    88.2  731.04      98  728.56   107.8  726.57
   225.4  704.29   264.6  697.01   284.2   693.6     294  692.48   303.8  692.06
   323.4  692.02   421.4  692.58   460.6  692.52   470.4  691.93   480.2  690.43
     490  688.34   509.6  683.87   519.4  682.59   529.2  682.32     539   682.3
   548.8  682.36   558.6  683.87   568.4  688.23   578.2  694.62     588  701.55
   597.8  708.71     637  738.14   656.6   752.6   666.4  757.55   676.2  757.85
#Mann= 3 , 0 , 0
       0     .08       0   509.6    .045       0   558.6      .1       0
Bank Sta=509.6,558.6
XS Rating Curve= 0 ,0
Exp/Cntr=0.3,0.1

Type RM Length L Ch R = 1 ,47838.3 ,473.6,459.2,444.8
XS GIS Cut Line= 3
     1858765.467      500810.536     1858431.714      501008.296
     1857947.687      501136.769
#Sta/Elev= 30
       0  902.22   135.8  825.39     320  731.78   339.4  723.36   349.2   720.3
   368.6  714.75   417.4  702.49     437   698.6   466.5  694.81   505.8  692.13
   574.5  690.35     604  690.37   672.7  691.97   682.5  690.43   702.2  684.14
     712  681.75   721.8  680.92   731.6   680.8   751.3   681.4   761.1  683.83
   770.9  688.34   780.7  694.37   810.2  716.58     820  722.27   829.8   726.9
   849.4  734.24   859.3  736.89   869.1  738.58   878.9  739.12   888.7  738.35
#Mann= 3 , 0 , 0
       0     .08       0   702.2    .045       0   761.1      .1       0
Bank Sta=702.2,761.1
XS Rating Curve= 0 ,0
Exp/Cntr=0.3,0.1

Type RM Length L Ch R = 1 ,47379.1 ,460.5,420.5,380.6
XS GIS Cut Line= 4
       1858003.9      500377.025     1857990.865      500583.262
     1857826.169      500789.479     1857913.923      501127.797
#Sta/Elev= 30
       0  827.11      59   797.2    98.4  778.13   147.6  755.99   206.6  731.04
   216.4  725.94   226.2  720.38   265.3  697.42   275.1  692.11   284.8  687.22
   294.6  683.29   304.4  681.04   323.9   680.7   333.7  680.72   343.5  681.21
   353.3  682.79   372.8  688.73   382.6  691.42   392.4  692.75   402.1  693.16
   480.3  693.32   548.2  694.15   577.4  695.06   674.4  698.91   684.2  699.68
   693.9  701.39   742.4  713.64   771.5  720.57     791  724.59   820.1  729.72
#Mann= 3 , 0 , 0
       0      .1       0   294.6    .045       0   353.3     .07       0
Bank Sta=294.6,353.3
XS Rating Curve= 0 ,0
Exp/Cntr=0.3,0.1

Type RM Length L Ch R = 1 ,46958.6 ,358.9,348,336.6
XS GIS Cut Line= 3
     1857292.354       500653.97     1857699.234        500866.9
     1857882.305      501134.147
#Sta/Elev= 30
       0  905.93     9.8  898.08    19.5   891.1    78.2  853.85   107.5  834.27
   185.6  780.88   205.2  767.94   224.7  755.66   234.5  748.67   244.3  740.15
     254   730.1   283.4  698.08   293.1  688.72   302.9  682.75   312.7  680.79
   322.4   680.7     342  681.01   351.8   682.3   390.8   691.2   400.6  692.54
   410.4  692.95   439.7  693.42   527.9  693.71   557.4   694.3     577  695.47
   626.1  699.48   665.4  702.13   675.2  703.47   743.9  716.98   783.2   723.9
#Mann= 3 , 0 , 0
       0      .1       0   302.9    .045       0   351.8     .07       0
Bank Sta=302.9,351.8
XS Rating Curve= 0 ,0
Exp/Cntr=0.3,0.1

Type RM Length L Ch R = 1 ,46610.6 ,514.3,505,495.5
XS GIS Cut Line= 3
     1857229.797      501147.452     1857710.061      501140.468
     1857888.833      501170.672
#Sta/Elev= 30
       0  864.35    19.6  850.08    29.4  843.15      49  829.59    58.8  823.08
    78.4  810.83   137.2  775.66   186.2  745.32     196  738.82   225.4  717.77
   264.7  690.08   274.5  684.06   284.3  681.09   294.1   680.6   303.9  680.63
   313.7  681.22   323.5  683.41   333.3  686.79   343.1  689.64   352.9  691.16
   411.7  694.18   499.4  699.36     528  700.79   537.6  701.37   547.1  702.37
   556.6  703.91   566.2  705.76   604.4  713.67   623.4  717.95   661.6  727.25
#Mann= 3 , 0 , 0
       0      .1       0   274.5    .045       0   323.5     .07       0
Bank Sta=274.5,323.5
XS Rating Curve= 0 ,0
Exp/Cntr=0.3,0.1

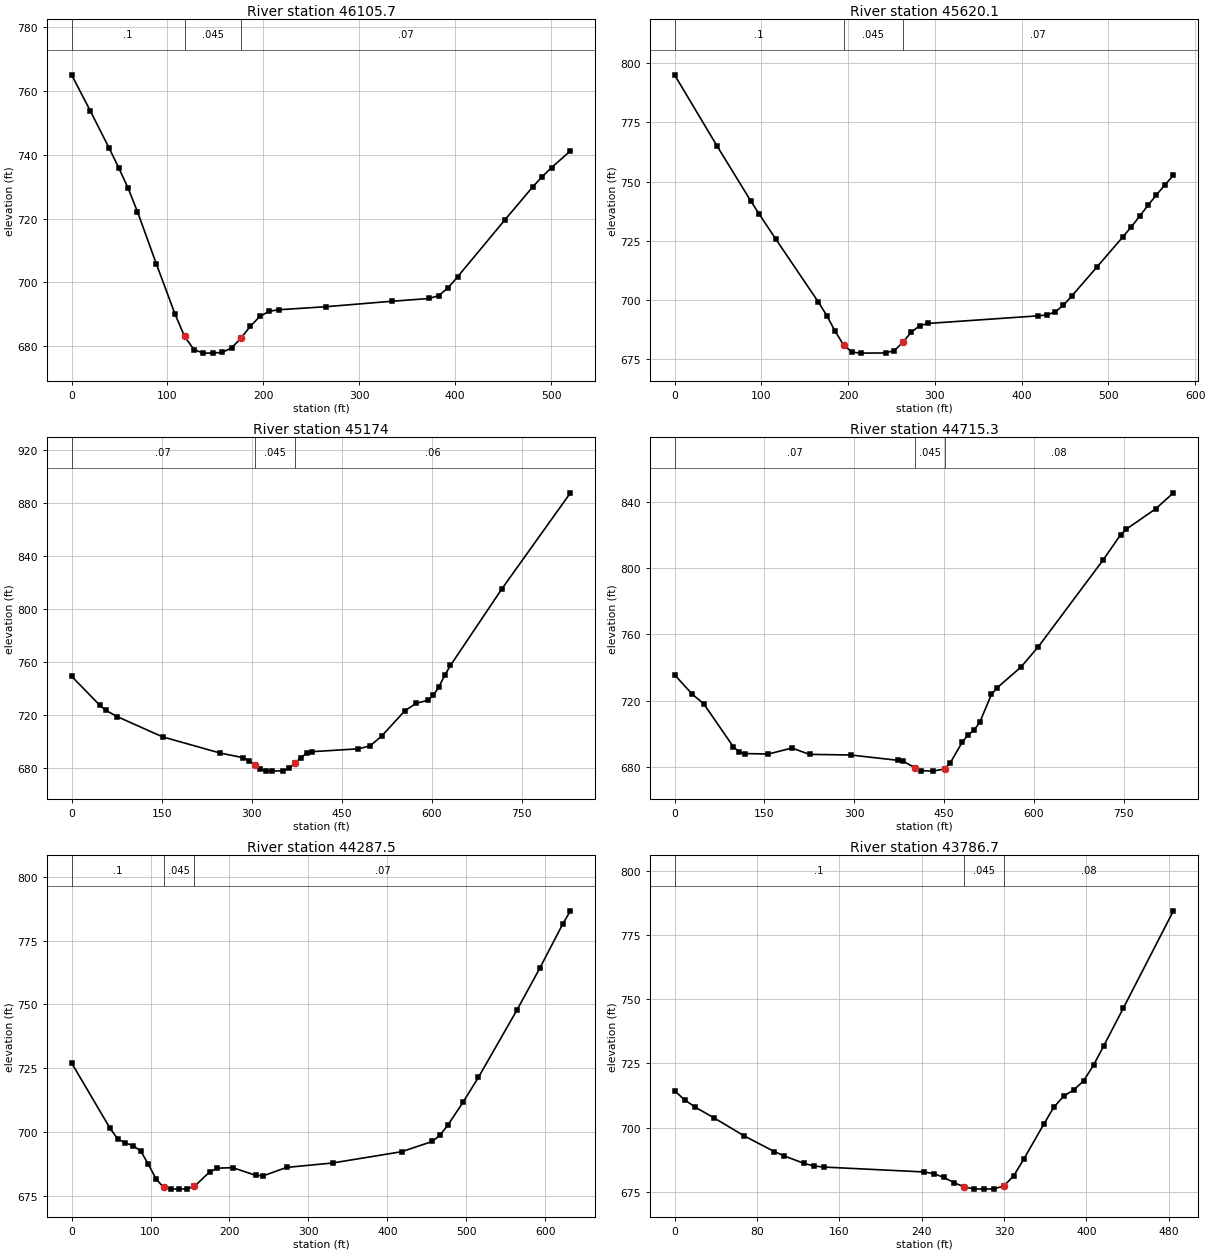
Type RM Length L Ch R = 1 ,46105.7 ,486.6,485.6,484.3
XS GIS Cut Line= 2
     1857521.783      501689.053     1857994.503      501471.738
#Sta/Elev= 30
       0  765.06    19.6  753.69    39.3  741.99    49.1  735.92    58.9  729.55
    68.7  722.14    88.4  705.75     108  689.93   117.8  683.04   127.6   678.9
   137.4   677.8   147.2  677.82   157.1  678.05   166.9  679.44   176.7  682.54
   186.5  686.23   196.3  689.31   206.2  690.93     216   691.4     265  692.35
   333.8  694.06     373  694.93   382.8  695.85   392.7  698.28   402.5   701.7
   451.6  719.48     481  729.94   490.8  733.14   500.6  735.99   520.3  741.22
#Mann= 3 , 0 , 0
       0      .1       0   117.8    .045       0   176.7     .07       0
Bank Sta=117.8,176.7
XS Rating Curve= 0 ,0
Exp/Cntr=0.3,0.1

Type RM Length L Ch R = 1 ,45620.1 ,443.4,446.1,448.9
XS GIS Cut Line= 2
     1857714.168      502142.288     1858223.698      501875.886
#Sta/Elev= 30
       0  795.05    48.7  765.19    87.7  741.91    97.4  736.38   116.9   725.6
   165.7  699.22   175.4  693.47   185.2  686.79   194.9  680.95   204.6  678.05
   214.4   677.6   243.6  677.68   253.4   678.7   263.1  682.13   272.9  686.49
   282.6  689.19   292.4  690.13     419  693.34   428.8  693.71   438.5  694.92
   448.3  697.84     458  701.77   487.3  714.13   516.5  726.54   526.2  730.78
     536  735.32   545.7  739.99   555.5  744.41   565.2   748.6     575  752.68
#Mann= 3 , 0 , 0
       0      .1       0   194.9    .045       0   263.1     .07       0
Bank Sta=194.9,263.1
XS Rating Curve= 0 ,0
Exp/Cntr=0.3,0.1

Type RM Length L Ch R = 1 ,45174   ,440.8,458.7,476.7
XS GIS Cut Line= 4
     1857822.154      502478.746     1858002.086      502471.584
     1858371.042      502332.844     1858593.334      502462.079
#Sta/Elev= 30
       0  749.09    47.4  727.08    56.9  723.47    75.8  718.75   151.6  703.44
   247.4  691.26   285.8  687.72   295.4   685.5   305.1  682.02   314.7  678.92
   324.3  677.65   333.9   677.6   353.1  677.93   362.7   679.8   372.4  683.52
     382  687.85   391.6  690.95   401.2  692.27   478.1  694.42   497.3   696.6
   516.6  703.95     555  722.92   574.2  728.76   593.3  730.91   602.8  734.69
   612.4  741.35   621.9  749.94   631.4  757.28   717.1  815.04   831.4  887.42
#Mann= 3 , 0 , 0
       0     .07       0   305.1    .045       0   372.4     .06       0
Bank Sta=305.1,372.4
XS Rating Curve= 0 ,0
Exp/Cntr=0.3,0.1

Type RM Length L Ch R = 1 ,44715.3 ,418.8,427.8,436.2
XS GIS Cut Line= 2
     1857842.863      502660.201     1858597.695      503012.793
#Sta/Elev= 30
       0  735.59    29.4  723.95      49  717.97      98  692.26   107.8  689.07
   117.6  688.08   156.8  687.83     196  691.42   225.4   687.6     294  687.23
   372.4  684.04   382.3  683.41   401.9  679.43   411.7  677.82   431.3   677.5
   450.9  678.81   460.7  682.63   480.3  694.89   490.1  699.28   499.9  702.04
   509.7  706.97   529.3  723.78   539.1  727.88   578.3  740.14   607.7  752.58
   715.5   804.7   744.9  819.98   754.7  823.43   803.7  835.68   833.1  845.28
#Mann= 3 , 0 , 0
       0     .07       0   401.9    .045       0   450.9     .08       0
Bank Sta=401.9,450.9
XS Rating Curve= 0 ,0
Exp/Cntr=0.3,0.1

Type RM Length L Ch R = 1 ,44287.5 ,475.3,500.9,526.1
XS GIS Cut Line= 2
     1857772.356      502890.355     1858202.044      503353.896
#Sta/Elev= 30
       0  727.03    48.6  701.49    58.3   697.3    68.1  695.64    77.8  694.67
    87.5  692.55    97.2  687.36     107  681.57   116.7  678.25   126.4  677.62
   136.1   677.6   145.9  677.71   155.6  678.69     175  684.37   184.8  685.81
   204.2  686.02   233.4  682.98   243.1  682.84   272.3   686.1   330.6  687.84
   418.1  692.26     457  696.28   466.8  698.73   476.5  702.58   495.9  711.62
   515.4  721.36     564  747.62   593.2  764.16   622.3  781.47   632.1  786.64
#Mann= 3 , 0 , 0
       0      .1       0   116.7    .045       0   155.6     .07       0
Bank Sta=116.7,155.6
XS Rating Curve= 0 ,0
Exp/Cntr=0.3,0.1

Type RM Length L Ch R = 1 ,43786.7 ,440.5,444.5,448.4
XS GIS Cut Line= 2
     1857558.988      502961.014     1857381.905      503412.056
#Sta/Elev= 30
       0  714.36     9.7  710.86    19.4  708.13    38.8  703.68    67.8  696.73
    96.9  690.65   106.6  688.94     126     686   135.7  685.02   145.4   684.6
   242.3   682.7     252  682.02   261.7  680.54   271.4  678.56     281  676.88
   290.7  676.11   300.4     676   310.1   676.1   319.8  677.21   329.5   681.2
   339.2  687.66   358.6  701.27   368.3  707.84     378  712.29   387.6  714.63
   397.3  718.19     407  724.36   416.7  731.69   436.1  746.71   484.6  784.53
#Mann= 3 , 0 , 0
       0      .1       0     281    .045       0   319.8     .08       0
Bank Sta=281,319.8
XS Rating Curve= 0 ,0
Exp/Cntr=0.3,0.1

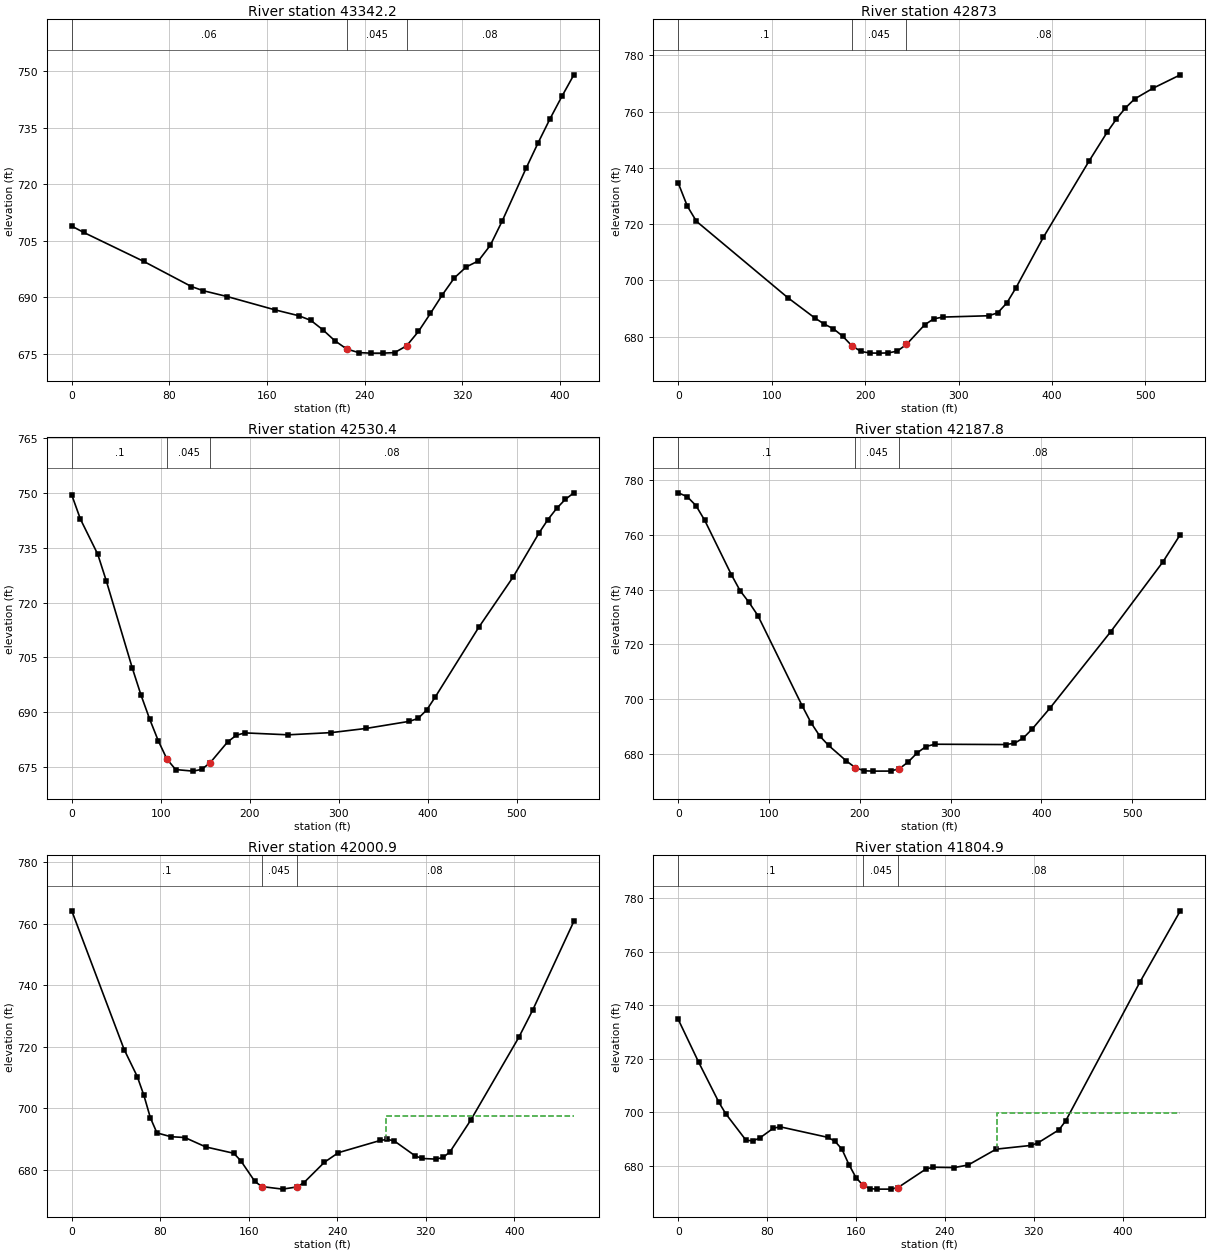
Type RM Length L Ch R = 1 ,43342.2 ,470.6,469.2,467.8
XS GIS Cut Line= 2
     1857202.738      502795.389     1856988.155      503146.431
#Sta/Elev= 30
       0  708.84     9.8  707.17    58.8   699.5      98   692.8   107.8  691.68
   127.4  690.13   166.5   686.6   186.1  685.03   195.9   683.8   205.7  681.31
   215.5  678.41   225.3  676.19   235.1  675.24   244.9   675.1   254.7   675.1
   264.5  675.23   274.3  677.02   284.1  680.87   293.9  685.66   303.7  690.62
   313.5   695.1   323.3  698.02   333.1  699.59   342.9  703.73   352.7  710.21
   372.2  724.18     382   730.9   391.8  737.32   401.6  743.32   411.4  749.05
#Mann= 3 , 0 , 0
       0     .06       0   225.3    .045       0   274.3     .08       0
Bank Sta=225.3,274.3
XS Rating Curve= 0 ,0
Exp/Cntr=0.3,0.1

Type RM Length L Ch R = 1 ,42873   ,344.2,342.6,341
XS GIS Cut Line= 2
     1856787.634      502549.556     1856536.592      503024.556
#Sta/Elev= 30
       0  734.58     9.8  726.32    19.5  720.98   117.2  693.84   146.5  686.53
   156.3  684.44   166.1  682.75   175.8   680.2   185.6   676.8   195.4  674.72
   205.1  674.15   214.9  674.11   224.7  674.18   234.4  674.83   244.2  677.18
   263.8  684.21   273.5  686.31   283.3  686.93   332.1   687.4   341.9  688.43
   351.7  691.98   361.4  697.33   390.7  715.28   439.6  742.38   459.1  752.71
   468.9  757.34   478.6  761.31   488.4  764.49     508  768.29   537.3  773.07
#Mann= 3 , 0 , 0
       0      .1       0   185.6    .045       0   244.2     .08       0
Bank Sta=185.6,244.2
XS Rating Curve= 0 ,0
Exp/Cntr=0.3,0.1

Type RM Length L Ch R = 1 ,42530.4 ,343.6,342.6,341.6
XS GIS Cut Line= 2
     1856480.364      502404.236     1856251.128       502919.59
#Sta/Elev= 30
       0  749.47     9.7  742.87    29.2  733.23    38.9  725.85    68.1  701.97
    77.8  694.63    87.5  688.06    97.2   682.1     107  677.06   116.7  674.23
   136.2   673.8   145.9  674.27   155.6  676.13     175  681.78   184.8  683.63
   194.5  684.28   243.1  683.75   291.7  684.36   330.6   685.5   379.3  687.45
     389  688.24   398.7  690.55   408.4  694.15   457.1  713.18     496  727.08
   525.1  739.15   534.9  742.75   544.6  745.78   554.3  748.25     564  750.07
#Mann= 3 , 0 , 0
       0      .1       0     107    .045       0   155.6     .08       0
Bank Sta=107,155.6
XS Rating Curve= 0 ,0
Exp/Cntr=0.3,0.1

Type RM Length L Ch R = 1 ,42187.8 ,216.6,186.9,156.3
XS GIS Cut Line= 3
     1856169.999      502271.036     1856016.848      502661.152
     1855952.083      502778.491
#Sta/Elev= 30
       0  775.41     9.8  774.02    19.5  770.76    29.2  765.34    58.5  745.52
    68.2  739.62      78  735.36    87.7  730.57   136.4  697.66   146.2  691.43
   155.9  686.53   165.7  683.07   185.2  677.43   194.9  675.01   204.7  673.82
   214.4   673.7   233.9  673.72   243.7   674.6   253.4  677.07   263.2  680.37
   272.9  682.69   282.6  683.53   360.6  683.41   370.4  683.88   380.1   685.8
   389.9  689.08   409.4  696.69   476.5  724.69     534   750.2   553.1  760.17
#Mann= 3 , 0 , 0
       0      .1       0   194.9    .045       0   243.7     .08       0
Bank Sta=194.9,243.7
XS Rating Curve= 0 ,0
Exp/Cntr=0.3,0.1

Type RM Length L Ch R = 1 ,42000.9 ,193.6,196,201
XS GIS Cut Line= 4
     1855902.277      502168.773     1855825.194      502260.439
     1856026.583      502586.134     1855921.722      502760.439
#Sta/Elev= 30
       0   764.2  47.373  719.08  59.201  710.32  65.114  704.29  71.092  696.86
  77.006  691.98  89.605  690.75 102.203  690.48 121.165  687.42 146.427  685.36
 152.726  682.96 165.325   676.3 171.624  674.54 190.587   673.7 203.185  674.39
 209.549   675.7 228.447  682.46 241.045  685.56  278.97  689.54 285.269  689.88
 291.568  689.36 310.531  684.49  316.83  683.66 329.364  683.46 335.599     684
 341.834  685.79 360.475  696.03 404.056  723.01 416.526  731.81 453.872  760.77
#Mann= 3 , 0 , 0
       0      .1       0 171.624    .045       0 203.185     .08       0
#XS Ineff= 2 , 0
                         283.958          697.46
Permanent Ineff=
       F       F
Bank Sta=171.624,203.185
XS Rating Curve= 0 ,0
Skew Angle= 50
Exp/Cntr=0.3,0.1

Type RM Length L Ch R = 1 ,41804.9 ,167.8,207.8,246.1
XS GIS Cut Line= 4
     1855810.611      502136.134     1855675.889      502269.884
     1855854.222      502552.106      1855755.75      502701.759
#Sta/Elev= 30
       0  734.69  18.319  718.76  36.639  703.72  42.681  699.55  61.001  689.61
  67.107   689.4  73.214  690.42  85.426  694.07  91.533  694.65 134.664   690.7
 140.963  689.26 147.263  686.32 153.562  680.58 159.926  675.71 166.225  672.82
 172.524  671.58 178.824   671.4 191.422   671.4 197.786     672 222.983  678.92
 229.347  679.56 248.245  679.43 260.908   680.4 286.105  686.31 317.666  687.71
 323.965  688.72  342.67  693.54 348.712  696.92 415.434  748.62 451.751  775.17
#Mann= 3 , 0 , 0
       0      .1       0 166.225    .045       0 197.786     .08       0
#XS Ineff= 2 , 0
                          286.78          699.61
Permanent Ineff=
       F       F
Bank Sta=166.225,197.786
XS Rating Curve= 0 ,0
Skew Angle= 50
Exp/Cntr=0.3,0.1

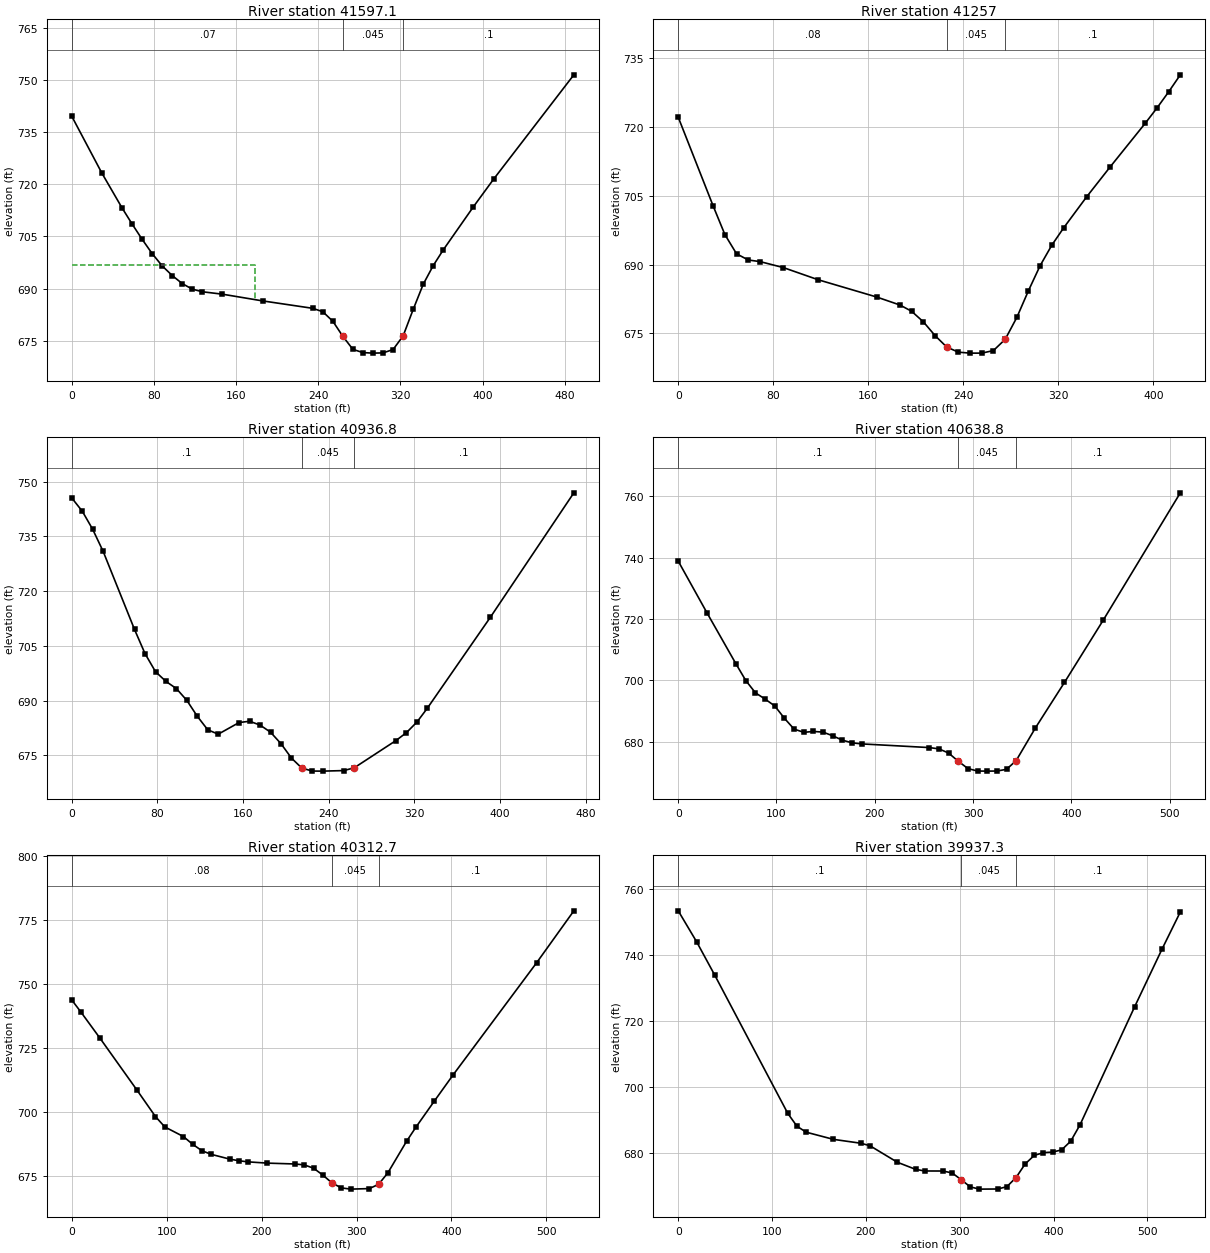
Type RM Length L Ch R = 1 ,41597.1 ,330.6,340,349.6
XS GIS Cut Line= 2
     1855788.129      502080.897     1855393.924        502369.9
#Sta/Elev= 30
       0  739.59    29.3  723.23    48.9  713.23    58.7  708.59    68.4  704.21
    78.2  700.08      88  696.52    97.8  693.74   107.5  691.43   117.3  689.82
   127.1  689.07   146.6  688.37   185.7  686.44   234.6   684.3   244.4  683.32
   254.2  680.56     264   676.2   273.7  672.48   283.5  671.55   293.3   671.4
     303  671.47   312.8  672.43   322.6  676.36   332.4  683.99   342.2  691.25
   351.9   696.6   361.7  701.14     391  713.53   410.6  721.45   488.8  751.52
#Mann= 3 , 0 , 0
       0     .07       0     264    .045       0   322.6      .1       0
#XS Ineff= 2 , 0
          178.57  696.74
Permanent Ineff=
       F       F
Bank Sta=264,322.6
XS Rating Curve= 0 ,0
Exp/Cntr=0.3,0.1

Type RM Length L Ch R = 1 ,41257   ,319.4,320.2,320.9
XS GIS Cut Line= 2
     1855644.294      501900.408     1855231.087      501988.764
#Sta/Elev= 30
       0  722.11    29.5   702.7    39.3  696.52    49.1  692.34      59  690.99
    68.8  690.65    88.4  689.35   117.9  686.68     167  682.93   186.7  681.18
   196.5  679.81   206.4   677.5   216.2  674.51     226  672.02   235.8  670.91
   245.7   670.7   255.5   670.7   265.3  671.26   275.2  673.71     285  678.48
   294.8  684.32   304.6  689.76   314.4  694.21   324.3  697.96   343.9  704.81
   363.6   711.3   393.1   720.8   402.9   724.1   412.7  727.61   422.6  731.35
#Mann= 3 , 0 , 0
       0     .08       0     226    .045       0   275.2      .1       0
Bank Sta=226,275.2
XS Rating Curve= 0 ,0
Exp/Cntr=0.3,0.1

Type RM Length L Ch R = 1 ,40936.8 ,293.2,298,301.9
XS GIS Cut Line= 2
     1855589.759       501593.14     1855128.325      501676.534
#Sta/Elev= 30
       0  745.49     9.8  741.87    19.5  736.93    29.3  730.87    58.6  709.49
    68.4  702.88    78.2  697.93    87.9  695.28    97.7   693.3   107.5  690.06
   117.2  685.73     127  682.01   136.8  680.82   156.3  684.01   166.1  684.35
   175.8  683.32   185.6  681.37   195.4  678.21   205.2  674.26   214.9  671.52
   224.7  670.72   234.4   670.7     254  670.85   263.8  671.61   302.8  679.08
   312.6  681.25   322.4  684.15   332.1  687.94   390.8  712.77   468.9   746.9
#Mann= 3 , 0 , 0
       0      .1       0   214.9    .045       0   263.8      .1       0
Bank Sta=214.9,263.8
XS Rating Curve= 0 ,0
Exp/Cntr=0.3,0.1

Type RM Length L Ch R = 1 ,40638.8 ,320.9,326.1,331.2
XS GIS Cut Line= 2
     1855584.826      501358.226     1855073.882      501351.867
#Sta/Elev= 30
       0  738.87    29.5  721.88      59  705.24    68.8  699.92    78.6  695.93
    88.4   693.9    98.3  691.63   108.1  687.62   117.9  684.11   127.8  683.05
   137.6  683.34   147.4  683.12   157.2  681.92     167   680.5   176.9  679.63
   186.7  679.28   255.5  678.08   265.3  677.66   275.1  676.31     285  673.63
   294.8  671.24   304.6  670.43   314.4   670.4   324.3  670.43   334.1  670.98
   343.9  673.82   363.6  684.53   393.1  699.33   432.4  719.55     511  761.15
#Mann= 3 , 0 , 0
       0      .1       0     285    .045       0   343.9      .1       0
Bank Sta=285,343.9
XS Rating Curve= 0 ,0
Exp/Cntr=0.3,0.1

Type RM Length L Ch R = 1 ,40312.7 ,373,375.5,377.9
XS GIS Cut Line= 2
     1855643.587       501113.17     1855129.929      500986.603
#Sta/Elev= 30
       0  743.74     9.8  738.94    29.4  728.97    68.6  708.56    88.2  698.16
      98  694.12   117.6  690.36   127.4  687.32   137.2   684.8     147  683.39
   166.5  681.53   176.3  680.88   186.1  680.45   205.7  679.97   235.1  679.63
   244.9  679.28   254.7     678   264.5   675.3   274.3  672.18   284.1  670.28
   293.9   669.8   313.5  670.01   323.3  671.68   333.1   676.2   352.7  688.47
   362.5  693.96   382.1  704.27   401.7  714.41   489.8   758.3     529  778.59
#Mann= 3 , 0 , 0
       0     .08       0   274.3    .045       0   323.3      .1       0
Bank Sta=274.3,323.3
XS Rating Curve= 0 ,0
Exp/Cntr=0.3,0.1

Type RM Length L Ch R = 1 ,39937.3 ,329.4,320.5,311.7
XS GIS Cut Line= 2
     1855767.719      500794.593     1855265.114      500610.999
#Sta/Elev= 30
       0  753.27    19.5  743.97    38.9  733.85   116.8  692.07   126.5  688.23
   136.2  686.43   165.4  684.25   194.6  683.08   204.3  682.33   233.5  677.34
     253  675.19   262.7   674.7   282.1  674.69   291.9  674.11   301.6  672.06
   311.3  669.89     321  669.22   340.5  669.26   350.2  669.95     360   672.7
   369.7  676.81   379.4   679.4   389.2  680.24   398.9   680.4   408.6  681.07
   418.3   683.7   428.1  688.58   486.4  724.28   515.6   741.7   535.1  752.92
#Mann= 3 , 0 , 0
       0      .1       0   301.6    .045       0     360      .1       0
Bank Sta=301.6,360
XS Rating Curve= 0 ,0
Exp/Cntr=0.3,0.1

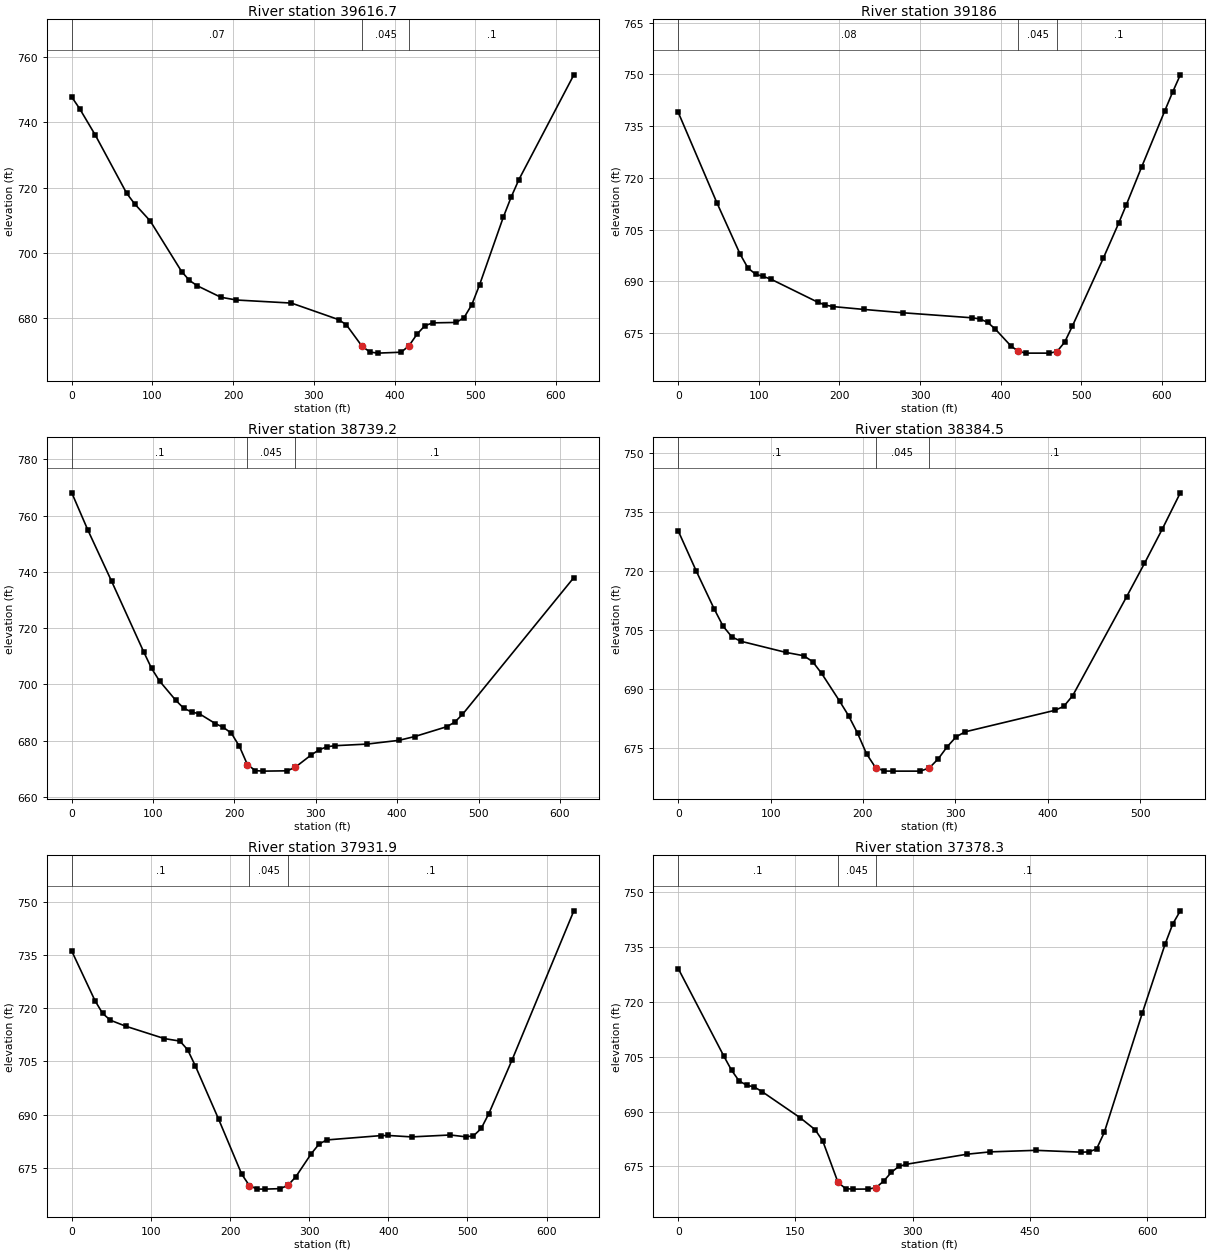
Type RM Length L Ch R = 1 ,39616.7 ,431,430.7,429.5
XS GIS Cut Line= 2
     1855919.455      500363.951     1855297.927      500389.993
#Sta/Elev= 30
       0  747.74     9.7   744.2    29.2  736.06      68  718.24    77.8  715.01
    97.2  709.74   136.1  694.23   145.8   691.5   155.5  689.86   184.7  686.34
   204.1  685.49   272.2  684.55   330.5  679.49   340.2   677.9   359.6  671.33
   369.4  669.54   379.1   669.2   408.2  669.48     418  671.51   427.7  674.99
   437.4  677.58   447.1  678.48   476.3  678.61     486  680.07   495.7  684.07
   505.4  690.23   534.6  710.83   544.3  716.98     554  722.42   622.1  754.56
#Mann= 3 , 0 , 0
       0     .07       0   359.6    .045       0     418      .1       0
Bank Sta=359.6,418
XS Rating Curve= 0 ,0
Exp/Cntr=0.3,0.1

Type RM Length L Ch R = 1 ,39186   ,468,446.7,425.5
XS GIS Cut Line= 3
     1855879.872      499948.608     1855544.396      499965.393
     1855258.295      499985.138
#Sta/Elev= 30
       0  739.02      48  712.77    76.8  697.88    86.4   693.9      96  692.08
   105.6  691.43   115.2  690.62   172.8     684   182.3  683.13   191.9   682.7
   230.3  681.87   278.3  680.91   364.6  679.44   374.1  679.12   383.7  678.13
   393.2  676.18   412.4  671.33   421.9  669.69   431.5   669.2   460.2   669.2
   469.7  669.63   479.3   672.4   488.8  677.02   527.1  696.68   546.2  706.85
   555.8  712.24   574.9  723.27   603.6  739.55   613.1  744.85   622.7   749.9
#Mann= 3 , 0 , 0
       0     .08       0   421.9    .045       0   469.7      .1       0
Bank Sta=421.9,469.7
XS Rating Curve= 0 ,0
Exp/Cntr=0.3,0.1

Type RM Length L Ch R = 1 ,38739.2 ,367.3,354.7,341.8
XS GIS Cut Line= 3
     1855471.439      499344.031     1855292.936      499625.887
     1855175.748      499884.133
#Sta/Elev= 30
       0   768.1    19.6  754.98    49.1  736.59    88.3  711.66    98.1  705.71
   107.9  701.22   127.6  694.45   137.4  691.61   147.2  690.22     157  689.56
   176.6  686.08   186.4  684.74   196.2  682.67   206.1     678   215.9  671.52
   225.7  669.38   235.5   669.2   264.9  669.31   274.8  670.59   294.4  674.97
   304.2  676.79     314  677.88   323.8  678.24     363  678.81   402.1  680.14
   421.6  681.49   460.8  684.97   470.5  686.54   480.3  689.36   617.2  737.98
#Mann= 3 , 0 , 0
       0      .1       0   215.9    .045       0   274.8      .1       0
Bank Sta=215.9,274.8
XS Rating Curve= 0 ,0
Exp/Cntr=0.3,0.1

Type RM Length L Ch R = 1 ,38384.5 ,458.8,452.6,446.5
XS GIS Cut Line= 2
     1854992.371      499279.749     1854992.371      499823.369
#Sta/Elev= 30
       0  730.22    19.4  720.08    38.8  710.46    48.5  706.04    58.2  703.26
      68  702.18   116.5  699.36   135.9  698.51   145.6  696.99   155.3     694
   174.7  686.99   184.4  683.28   194.2  678.81   203.9  673.59   213.6  670.11
   223.3  669.22     233   669.2   262.1   669.2   271.8     670   281.5  672.32
   291.2  675.39   300.9  677.92   310.6  679.18   407.7  684.64   417.4  685.64
   427.1  688.38   485.4  713.47   504.8  721.97   524.2  730.74   543.6  739.89
#Mann= 3 , 0 , 0
       0      .1       0   213.6    .045       0   271.8      .1       0
Bank Sta=213.6,271.8
XS Rating Curve= 0 ,0
Exp/Cntr=0.3,0.1

Type RM Length L Ch R = 1 ,37931.9 ,560.4,553.6,546.5
XS GIS Cut Line= 2
     1854478.048      499326.407     1854649.489      499937.302
#Sta/Elev= 30
       0  736.12    29.3  722.16      39  718.54    48.8  716.62    68.3  714.92
   117.1  711.43   136.7  710.73   146.4  708.29   156.2  703.71   185.5  688.73
   214.8  673.16   224.5  669.93   234.3  668.97     244  668.95   263.6  669.09
   273.3  670.04   283.1  672.43   302.6  678.93   312.4  681.64   322.1  682.83
   390.5  684.05   400.2  684.09   429.5  683.69   478.3  684.23   497.8  683.72
   507.6  683.97   517.4  686.06   527.1  690.28   556.4   705.4   634.5  747.49
#Mann= 3 , 0 , 0
       0      .1       0   224.5    .045       0   273.3      .1       0
Bank Sta=224.5,273.3
XS Rating Curve= 0 ,0
Exp/Cntr=0.3,0.1

Type RM Length L Ch R = 1 ,37378.3 ,534,513.4,492.7
XS GIS Cut Line= 2
     1853935.514      499631.312     1854288.161      500168.421
#Sta/Elev= 30
       0  729.07    58.4  705.13    68.2   701.3    77.9  698.36    87.6  697.21
    97.4   696.7   107.1  695.47   155.8  688.34   175.2  685.04     185  681.93
   204.4  670.67   214.2  668.93   223.9   668.8   243.4  668.82   253.1  669.22
   262.8  670.97   272.6  673.37   282.3  675.02   292.1   675.6   369.9  678.35
   399.2  678.98   457.6   679.4     516   678.9   525.7  678.97   535.4   679.8
   545.2   684.3   593.8  716.87   623.1  735.79   632.8  741.25   642.5  744.85
#Mann= 3 , 0 , 0
       0      .1       0   204.4    .045       0   253.1      .1       0
Bank Sta=204.4,253.1
XS Rating Curve= 0 ,0
Exp/Cntr=0.3,0.1