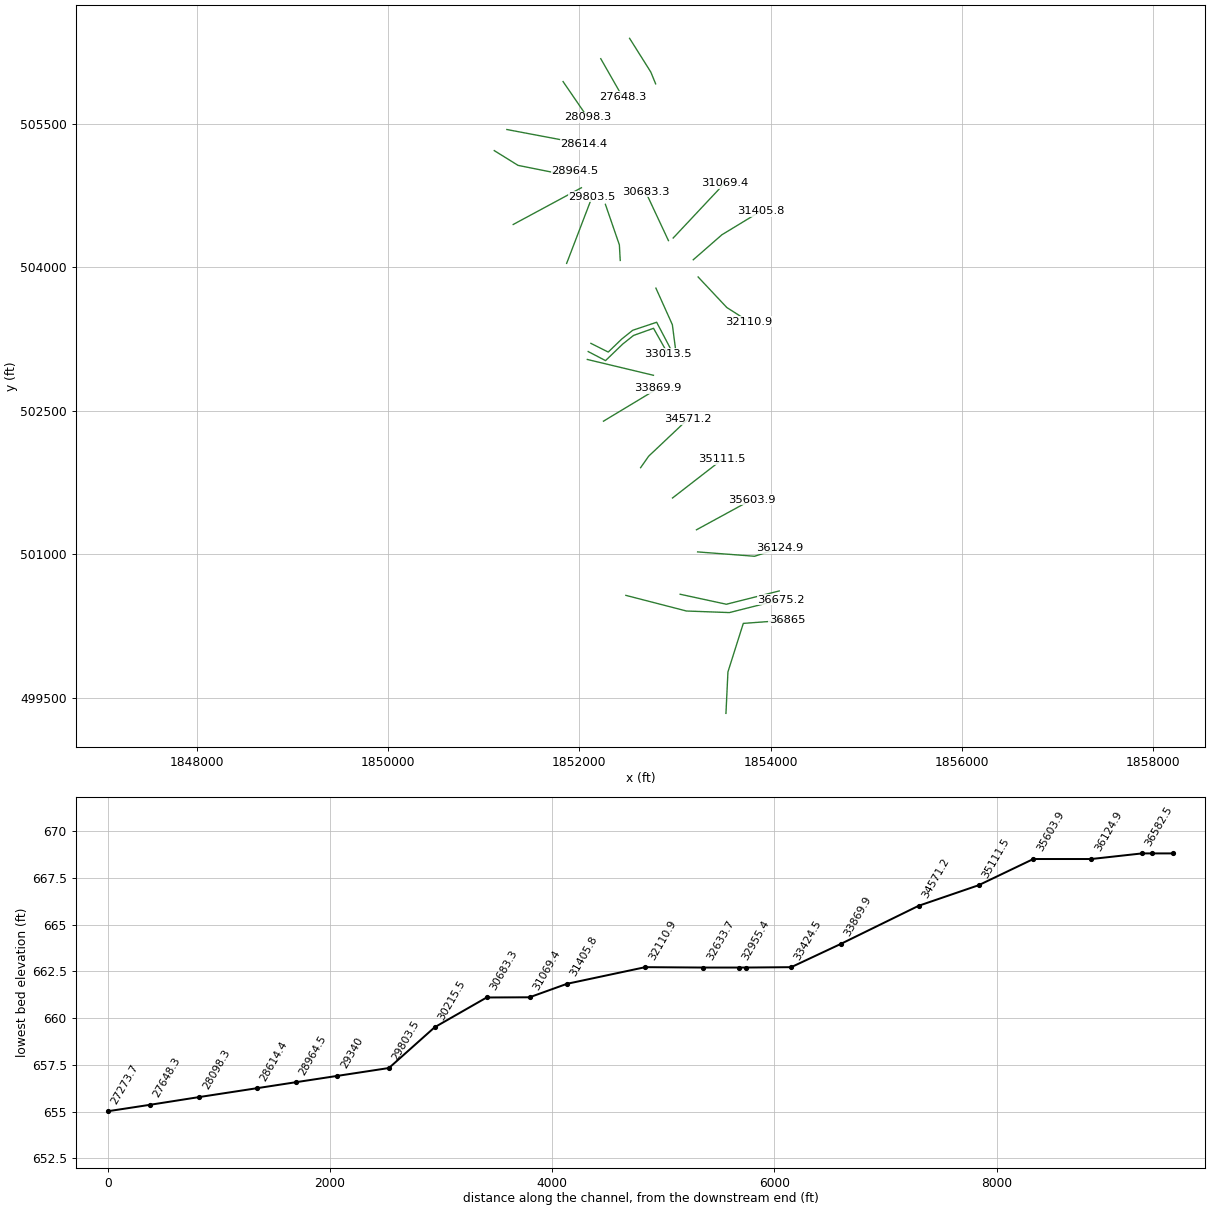
HEC-RAS study BLUECR.prj: BLUECR

--- BLUECR.g01 (geometry) --- (continued)

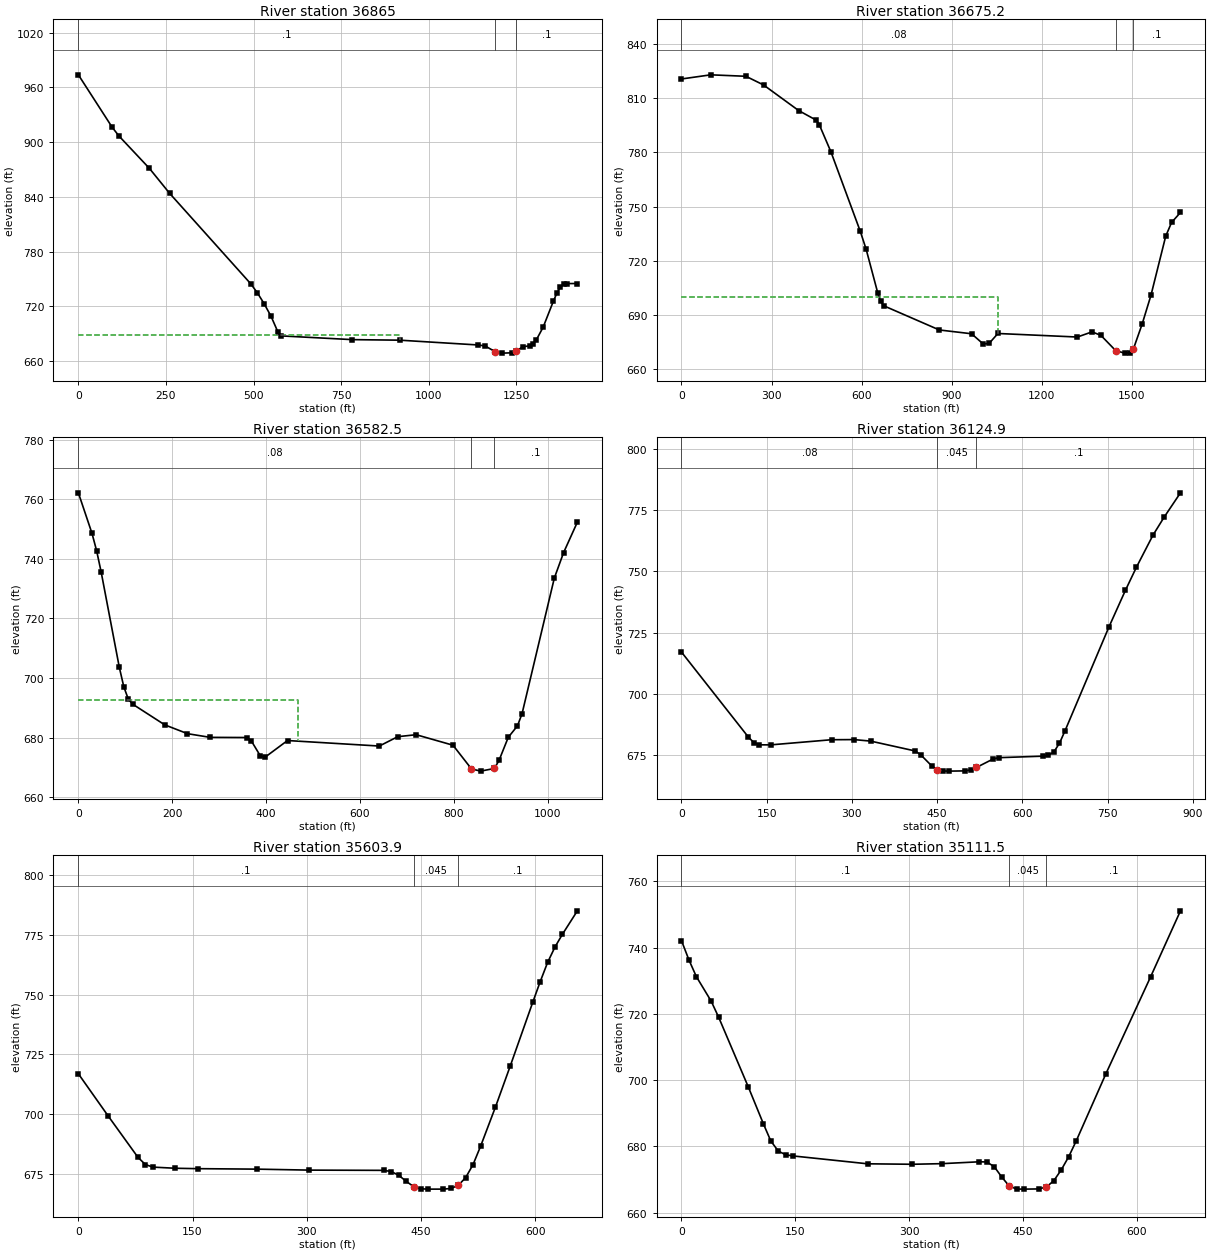
Type RM Length L Ch R = 1 ,36865   ,186,189.8,193.7
XS GIS Cut Line= 4
     1853532.531      499338.568     1853553.364      499771.902
     1853713.856      500278.881     1854171.321      500312.736
#Sta/Elev= 30
       0   973.8    96.4  916.37   115.7  906.83   202.5  871.38   260.3     844
   491.8  744.89   511.2  734.74   530.5  722.78   549.9  709.21   569.2  692.28
   578.9  687.69   781.9  683.59   917.3  682.99  1141.3  677.73  1160.8  676.68
  1190.1  670.31  1209.6   668.8  1238.9  669.15  1248.6  670.74  1268.2  675.65
  1287.7   676.9  1297.4  679.05  1307.2  683.35  1326.7  697.32    1356   725.9
  1365.8  734.56  1375.5     741  1385.3   744.2    1395  745.03  1424.3  745.08
#Mann= 3 , 0 , 0
       0      .1       0  1190.1    .045       0  1248.6      .1       0
#XS Ineff= 2 , 0
          917.83  688.95
Permanent Ineff=
       F       F
Bank Sta=1190.1,1248.6
XS Rating Curve= 0 ,0
Exp/Cntr=0.3,0.1

Type RM Length L Ch R = 1 ,36675.2 ,92.7,92.6,92.7
XS GIS Cut Line= 4
     1852486.698      500571.902     1853119.917      500408.373
     1853568.381      500391.959     1854110.633      500528.543
#Sta/Elev= 30
       0   820.7    97.6     823   214.7  822.19   273.3   817.4   390.4   803.2
     449  797.87   458.8  795.47   497.8  780.34   595.4  736.37     615  726.42
     654  702.02   663.8  697.44   673.5  695.05   858.9  681.63   966.2  679.53
  1005.2  673.86  1024.7  674.18    1054  679.68  1318.6  677.72  1367.6  680.59
  1397.1  678.62  1446.1  670.22  1475.6   668.8  1495.2  669.03    1505     671
  1534.4  684.92  1563.8  700.89  1612.9  733.62  1632.5  741.22    1662  746.73
#Mann= 3 , 0 , 0
       0     .08       0  1446.1    .045       0    1505      .1       0
#XS Ineff= 2 , 0
          1053.3  699.78
Permanent Ineff=
       F       F
Bank Sta=1446.1,1505
XS Rating Curve= 0 ,0
Exp/Cntr=0.3,0.1

Type RM Length L Ch R = 1 ,36582.5 ,464.7,457.7,450.1
XS GIS Cut Line= 3
     1853054.359      500583.448     1853537.214      500479.096
     1854089.175      500618.126
#Sta/Elev= 30
       0  762.12    29.1  748.49    38.8  742.76    48.4   735.7    87.2  703.64
    96.9  697.02   106.6  692.87   116.2   691.2     184  684.32   232.5  681.36
   280.9  680.12   358.4  680.07   368.1  679.04   387.4     674   397.1  673.39
   445.6  679.06   641.2  677.21   680.5  680.35   719.7  681.01   798.2  677.49
   837.5  669.55   857.1   668.8   886.6   669.7   896.4  672.45     916  680.15
   935.6  683.99   945.4  688.11  1014.1  733.54  1033.8  742.06  1063.2   752.3
#Mann= 3 , 0 , 0
       0     .08       0   837.5    .045       0   886.6      .1       0
#XS Ineff= 2 , 0
          468.13  692.65
Permanent Ineff=
       F       F
Bank Sta=837.5,886.6
XS Rating Curve= 0 ,0
Exp/Cntr=0.3,0.1

Type RM Length L Ch R = 1 ,36124.9 ,507.9,521,534
XS GIS Cut Line= 3
     1853236.469      501026.104     1853832.172      500980.531
     1854099.099      501067.336
#Sta/Elev= 30
       0   717.1   117.5  682.47   127.3  680.15   137.1  679.24   156.7  679.21
   264.4  681.32   303.6  681.37     333  680.75   411.4  676.72   421.2  675.13
   440.7  670.56   450.5  669.08   460.3  668.56   470.1   668.5   499.5   668.6
   509.3  669.07   519.1  670.01   548.5  673.46   558.3  673.99   636.2  674.61
   645.8  674.93   655.5  676.39   665.2  679.89   674.9  684.93   752.3  727.37
   781.3  742.32   800.7  751.76   829.7  764.79   849.1  772.06   878.1  782.08
#Mann= 3 , 0 , 0
       0     .08       0   450.5    .045       0   519.1      .1       0
Bank Sta=450.5,519.1
XS Rating Curve= 0 ,0
Exp/Cntr=0.3,0.1

Type RM Length L Ch R = 1 ,35603.9 ,488.8,492.4,496
XS GIS Cut Line= 2
     1853224.408       501257.09     1853799.929      501570.892
#Sta/Elev= 30
       0   716.8    39.1  699.15    78.3  681.81      88  678.81    97.8  677.72
   127.2  677.24   156.5  677.07   234.8  676.87   303.3  676.46   401.1  676.36
   410.9  675.88   420.7  674.33   430.5  671.81   440.3  669.57     450  668.63
   459.8   668.5   479.3   668.5   489.2  668.77     499  670.05   508.8  673.35
   518.5  678.81   528.3  686.41   547.9  702.88   567.5  720.22   596.8  746.67
   606.6  755.32   616.4  763.44   626.2  769.96   635.9  775.24   655.5  785.04
#Mann= 3 , 0 , 0
       0      .1       0   440.3    .045       0     499      .1       0
Bank Sta=440.3,499
XS Rating Curve= 0 ,0
Exp/Cntr=0.3,0.1

Type RM Length L Ch R = 1 ,35111.5 ,538,540.3,542.4
XS GIS Cut Line= 2
      1852974.23      501589.586     1853493.673      501992.516
#Sta/Elev= 30
       0  742.11     9.8  736.29    19.6  731.24    39.2   723.8    49.1  718.92
    88.3  697.81   107.9  686.83   117.7  681.63   127.6  678.57   137.4  677.46
   147.2  677.11   245.3  674.74   304.2   674.6   343.4  674.79   392.5  675.35
   402.3   675.3   412.1  673.86   421.9  670.77   431.7  668.05   441.5  667.12
   451.4   667.1     471  667.16   480.8  667.74   490.6  669.66   500.4  672.93
   510.2  676.89     520  681.62   559.3  701.98   618.2  731.23   657.4  751.08
#Mann= 3 , 0 , 0
       0      .1       0   431.7    .045       0   480.8      .1       0
Bank Sta=431.7,480.8
XS Rating Curve= 0 ,0
Exp/Cntr=0.3,0.1

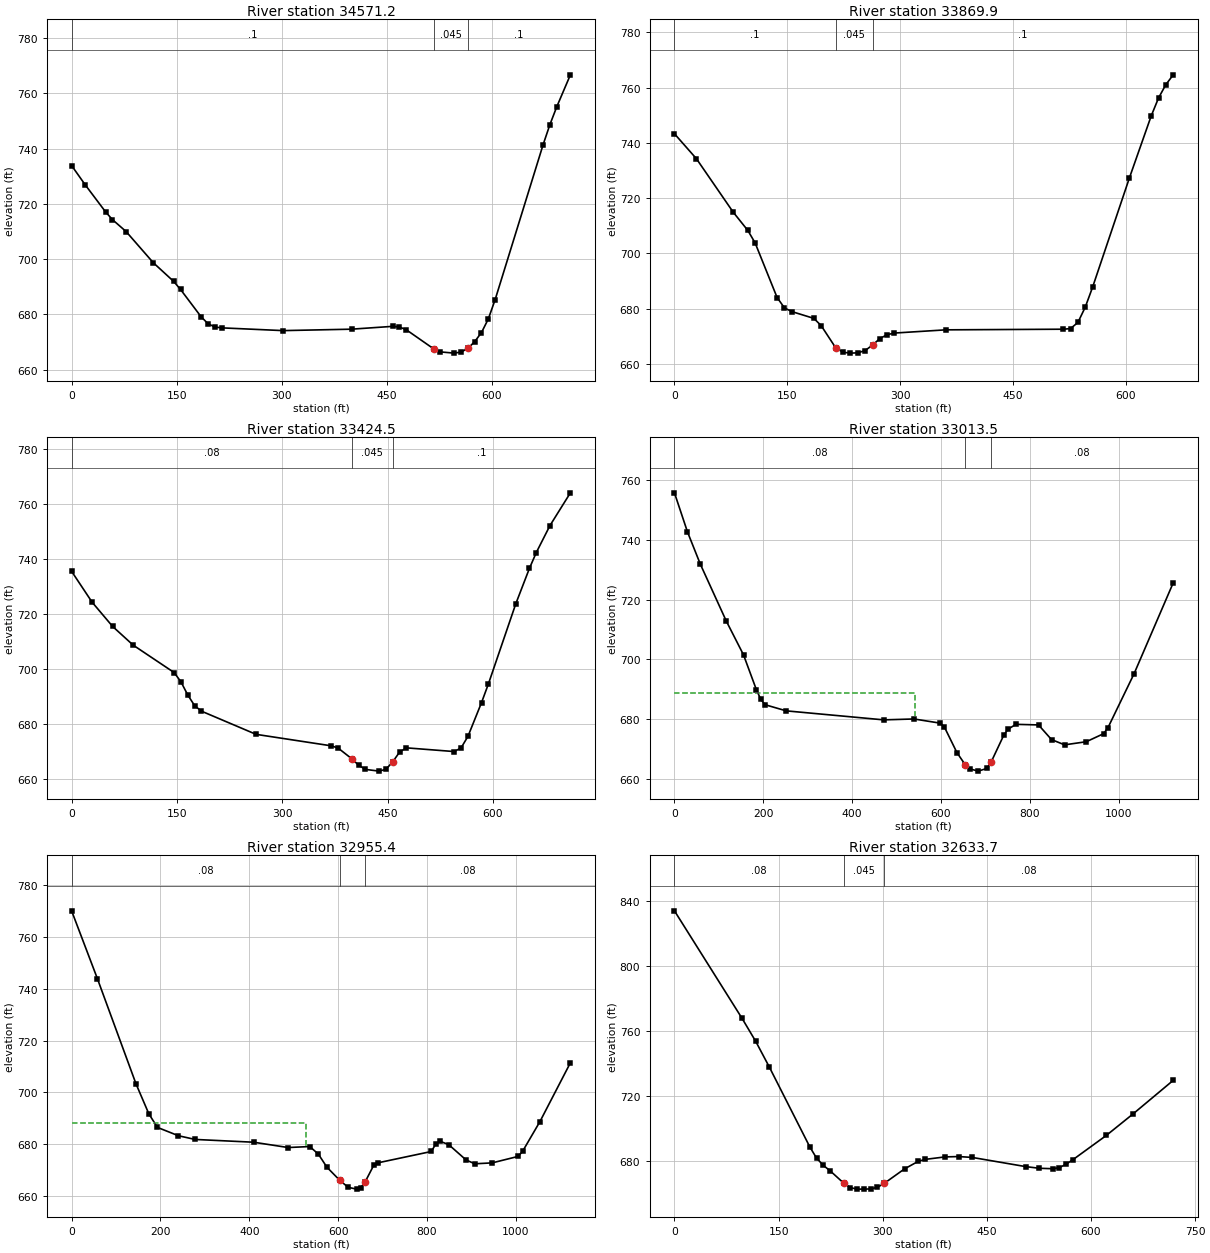
Type RM Length L Ch R = 1 ,34571.2 ,706.3,701.3,696.3
XS GIS Cut Line= 3
      1852640.97      501906.604     1852724.604      502026.129
      1853136.63      502415.285
#Sta/Elev= 30
       0   733.9    19.4  726.94    48.6  717.11    58.4  714.32    77.8  710.03
   116.7  698.73   145.9  691.94   155.6  689.06     185  679.17   194.7  676.69
   204.5  675.46   214.3  675.15   302.2  674.15   399.9  674.67   458.6  675.69
   468.3  675.46   478.1  674.47   517.2  667.56     527  666.44   546.5     666
   556.3  666.38   566.1  667.73   575.8  670.13   585.6  673.46   595.4  678.41
   605.1  685.37   673.5  741.36   683.3  748.71   693.1  755.16   712.6  766.75
#Mann= 3 , 0 , 0
       0      .1       0   517.2    .045       0   566.1      .1       0
Bank Sta=517.2,566.1
XS Rating Curve= 0 ,0
Exp/Cntr=0.3,0.1

Type RM Length L Ch R = 1 ,33869.9 ,462.8,445.4,427.8
XS GIS Cut Line= 2
     1852252.342      502392.281      1852820.05      502734.295
#Sta/Elev= 30
       0  743.29    29.2  734.26      78  714.96    97.5  708.33   107.2  703.81
   136.4  684.07   146.2  680.31     156  678.98   185.2  676.53   194.9  673.93
   214.4  665.83   224.2  664.27   233.9  663.96   243.7  664.07   253.4  664.89
   263.2  666.88   272.9  669.21   282.6  670.63   292.4  671.22   360.6  672.38
   516.6  672.61   526.3  672.83   536.1  675.05   545.8  680.53   555.6  687.77
   604.3  727.12   633.5  749.72   643.3  756.25     653  761.06   662.8   764.6
#Mann= 3 , 0 , 0
       0      .1       0   214.4    .045       0   263.2      .1       0
Bank Sta=214.4,263.2
XS Rating Curve= 0 ,0
Exp/Cntr=0.3,0.1

Type RM Length L Ch R = 1 ,33424.5 ,397.9,411,425.2
XS GIS Cut Line= 2
     1852084.066      503037.152     1852774.939      502871.987
#Sta/Elev= 30
       0  735.51    29.2  724.27    58.4  715.44    87.6  708.64     146  698.64
   155.7  695.26   165.4  690.47   175.2  686.57   184.9  684.57   262.7  676.12
   369.8  671.94   379.5  671.13     399  667.22   408.7   664.9   418.4  663.35
   437.9  662.72   447.6  663.38   457.3  666.11   467.1  669.67   476.8   671.2
   544.9  669.85   554.6  671.18   564.4  675.37   583.8  687.72   593.6  694.53
   632.5  723.66     652  736.62   661.7  742.34   681.2  752.19   710.3  764.12
#Mann= 3 , 0 , 0
       0     .08       0     399    .045       0   457.3      .1       0
Bank Sta=399,457.3
XS Rating Curve= 0 ,0
Exp/Cntr=0.3,0.1

Type RM Length L Ch R = 1 ,33013.5 ,57.6,58,59.8
XS GIS Cut Line= 6
      1852093.13      503119.735     1852274.084      503025.365
     1852452.577      503197.177     1852566.674      503288.288
     1852775.595      503362.955     1852924.554      503098.545
#Sta/Elev= 30
       0  755.65    29.2  742.65    58.3  731.81   116.6  712.86   155.5  701.54
   184.6  689.86   194.4  686.68   204.1  684.88   251.7  682.83   471.3  679.82
   539.4  680.12   597.8  678.74   607.4  677.57   636.1  668.89   655.3  664.72
   664.9  663.47     684   662.7   703.2  663.59   712.7   665.6   741.4  674.64
     751  676.69     769  678.33   819.8  678.13   849.1  673.24   878.5  671.48
   927.4  672.52   966.6  675.22   976.4  677.26  1035.1  695.26  1123.2   725.6
#Mann= 3 , 0 , 0
       0     .08       0   655.3    .045       0   712.7     .08       0
#XS Ineff= 2 , 0
          541.76  688.73
Permanent Ineff=
       F       F
Bank Sta=655.3,712.7
XS Rating Curve= 0 ,0
Exp/Cntr=0.3,0.1

Type RM Length L Ch R = 1 ,32955.4 ,356.2,321.7,284.9
XS GIS Cut Line= 6
     1852120.968       503205.68     1852302.275      503114.689
     1852444.244      503251.344     1852558.341      503342.455
     1852808.234      503426.149      1852953.72      503148.892
#Sta/Elev= 30
       0  770.01      58  743.88   144.9  703.32   173.9  691.72   193.2   686.5
   240.4  683.29   277.9  681.86   409.6  680.79   487.5  678.74   536.2  679.12
   555.5  676.19   574.6  671.18   603.4  666.14   622.5   663.4   641.7   662.7
   651.2  663.32   660.8  665.51     680  671.85   689.5  672.84   809.7  677.21
   819.5     680   829.2  681.16   848.8  679.87     888  673.95   907.5  672.47
   946.7  672.82  1005.4  675.33  1015.2  677.28  1054.3  688.76  1122.8  711.42
#Mann= 3 , 0 , 0
       0     .08       0   603.4    .045       0   660.8     .08       0
#XS Ineff= 2 , 0
          528.57  688.34
Permanent Ineff=
       F       F
Bank Sta=603.4,660.8
XS Rating Curve= 0 ,0
Exp/Cntr=0.3,0.1

Type RM Length L Ch R = 1 ,32633.7 ,515.3,522.9,530.4
XS GIS Cut Line= 3
     1852800.595       503782.92      1852972.47      503400.628
     1853011.012      503103.753
#Sta/Elev= 30
       0  833.84    97.5  767.63     117  753.62   136.5  737.92     195  688.65
   204.7  681.77   214.4  677.32   224.2  673.98   243.7  666.44   253.4  663.63
   263.2  662.71   272.9   662.7   282.7  662.83   292.4  663.83   302.2  666.25
   331.4  675.14   350.9  679.73   360.7  680.96   389.9  682.52   409.4  682.73
   428.8   682.2   506.1  676.54   525.4  675.53   544.7  675.25   554.4  675.89
     564  678.01   573.7  680.71     622  695.68   660.6  708.94   718.5   729.6
#Mann= 3 , 0 , 0
       0     .08       0   243.7    .045       0   302.2     .08       0
Bank Sta=243.7,302.2
XS Rating Curve= 0 ,0
Exp/Cntr=0.3,0.1

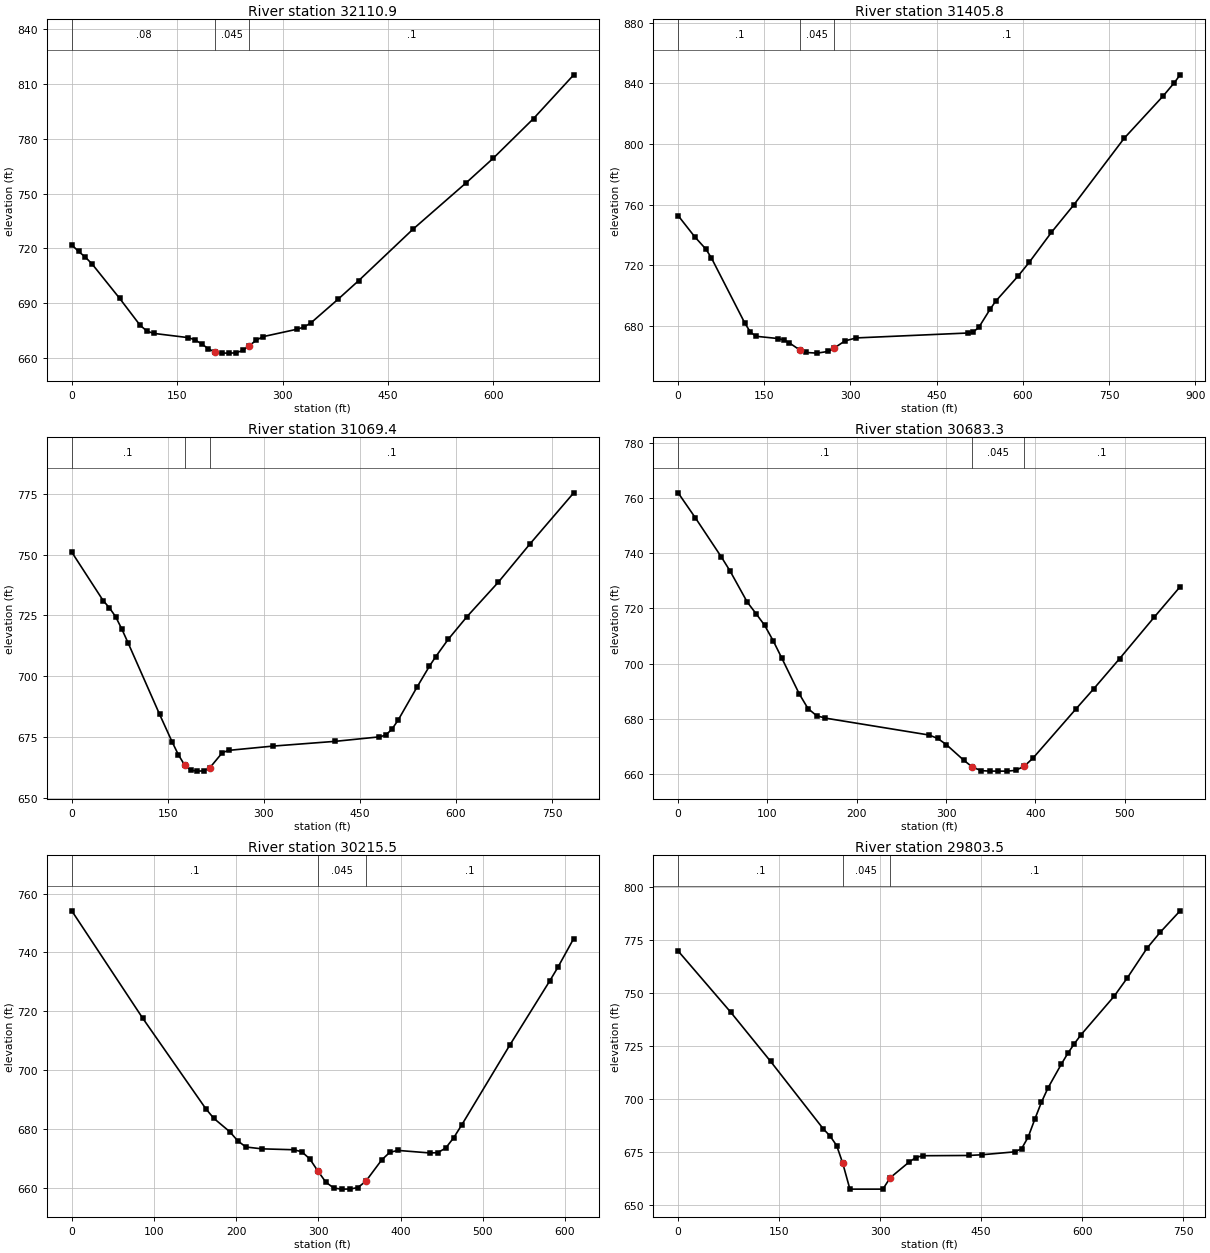
Type RM Length L Ch R = 1 ,32110.9 ,669.9,705,739.2
XS GIS Cut Line= 3
     1853241.772      503899.401     1853541.252      503580.391
     1853774.542      503431.736
#Sta/Elev= 30
       0  721.94     9.7  718.35    19.4  715.21    29.2  711.35    68.1  692.69
    97.2  677.98     107  674.75   116.7  673.51   165.3  671.22     175  670.06
   184.8  667.76   194.5  665.07   204.2  663.19   213.9  662.75   223.6  662.72
   233.4  662.86   243.1  664.16   252.8  666.84   262.5  669.81   272.3  671.75
   320.9  675.83   330.6  677.03   340.3  679.27   379.2  692.31   408.4  702.45
   485.2  730.42   561.6  756.06   599.7  769.36     657  791.05   714.2  814.98
#Mann= 3 , 0 , 0
       0     .08       0   204.2    .045       0   252.8      .1       0
Bank Sta=204.2,252.8
XS Rating Curve= 0 ,0
Exp/Cntr=0.3,0.1

Type RM Length L Ch R = 1 ,31405.8 ,334.4,336.5,339.2
XS GIS Cut Line= 3
     1853191.146      504079.364     1853490.131      504340.424
     1853897.772       504587.85
#Sta/Elev= 30
       0   752.7      29  738.67    48.4  730.53    58.1  724.62   116.2  681.59
   125.8  675.74   135.5  672.97   174.3  671.46   183.9  670.49   193.6   668.6
     213   663.6   222.7  662.26     242  661.83   261.4  662.97   271.1  665.04
   290.4  669.89   309.8  671.87     504  675.12   513.7  675.78   523.4  678.84
   542.9  690.73   552.6  696.04   591.6  712.66     611  721.75   649.9  741.67
   688.9  759.85   776.5  803.82   844.6  831.86     864  840.62   873.8  845.72
#Mann= 3 , 0 , 0
       0      .1       0     213    .045       0   271.1      .1       0
Bank Sta=213,271.1
XS Rating Curve= 0 ,0
Exp/Cntr=0.3,0.1

Type RM Length L Ch R = 1 ,31069.4 ,359.1,386.1,413.1
XS GIS Cut Line= 2
     1852981.106        504306.6     1853517.564      504878.214
#Sta/Elev= 30
       0     751      49  731.12    58.8  728.13    68.6  724.47    78.4  719.29
    88.2  713.61   137.2   684.4   156.8  673.07   166.6  667.78   176.4  663.54
   186.2  661.47     196  661.11   205.8   661.2   215.6  662.49   235.2   668.7
     245  669.63   313.6  671.37   411.6  673.34   480.2  675.17     490  675.85
   499.8  678.27   509.6  682.01     539  695.53   558.5  704.17   568.3  708.07
   587.9  715.22   617.3  724.56   666.3  738.72   715.3   754.3   783.9  775.35
#Mann= 3 , 0 , 0
       0      .1       0   176.4    .045       0   215.6      .1       0
Bank Sta=176.4,215.6
XS Rating Curve= 0 ,0
Exp/Cntr=0.3,0.1

Type RM Length L Ch R = 1 ,30683.3 ,470.2,467.8,465.4
XS GIS Cut Line= 2
     1852931.627      504279.256     1852693.345      504788.371
#Sta/Elev= 30
       0  761.82    19.4  752.73    48.5  738.56    58.2  733.51    77.5  722.22
    87.2  718.12    96.9  713.87   106.6  708.19   116.3  701.87   135.7  689.02
   145.4  683.76   155.1  681.15   164.8  680.29   281.1  674.16   290.8  672.91
   300.4  670.68   319.8  665.06   329.5  662.58   339.2  661.28   348.9  661.11
   358.6   661.1   368.3   661.1     378  661.37   387.7   662.9   397.4  665.81
   445.8  683.72   465.2  690.82   494.3  701.78     533  716.77   562.1  727.82
#Mann= 3 , 0 , 0
       0      .1       0   329.5    .045       0   387.7      .1       0
Bank Sta=329.5,387.7
XS Rating Curve= 0 ,0
Exp/Cntr=0.3,0.1

Type RM Length L Ch R = 1 ,30215.5 ,427.8,412,396.1
XS GIS Cut Line= 3
      1852427.72      504072.225     1852418.606      504234.985
     1852272.772      504658.162
#Sta/Elev= 30
       0  754.14    86.3  717.63     163  686.86   172.8  683.58   192.2  679.02
   201.9  675.94   211.7  673.84   231.1  673.21     270   672.9   279.8  672.22
   289.5  669.79   299.2  665.74     309   661.9   318.7  659.87   328.4  659.51
   338.2  659.54   347.9  660.02   357.6  662.16   377.1  669.47   386.8  672.01
   396.6  672.68   435.5  671.81   445.2  671.91   454.9  673.49   464.7  677.03
   474.4  681.36   532.8  708.47   581.4   730.3   591.2  734.89   610.6  744.73
#Mann= 3 , 0 , 0
       0      .1       0   299.2    .045       0   357.6      .1       0
Bank Sta=299.2,357.6
XS Rating Curve= 0 ,0
Exp/Cntr=0.3,0.1

Type RM Length L Ch R = 1 ,29803.5 ,479.5,463.5,447.5
XS GIS Cut Line= 2
     1851867.678      504041.336     1852134.145      504737.305
#Sta/Elev= 30
       0  769.84    78.4   740.8   137.3  717.68   215.7  685.72   225.5  682.45
   235.3  677.94   244.2  669.76     255  657.33     304  657.33   314.8  662.69
   343.2   670.2     353  672.26   362.8  673.11   431.4  673.23   451.1  673.57
   500.1  674.96   509.9  676.44   519.7  681.94   529.5  690.35   539.3  698.35
   549.1  705.14   568.7  716.27   578.5  721.48   588.3  726.08   598.2  730.29
   647.2  748.42   666.8  757.11   696.2   771.2   715.8  778.72   745.2  788.81
#Mann= 3 , 0 , 0
       0      .1       0   244.2    .045       0   314.8      .1       0
Bank Sta=244.2,314.8
XS Rating Curve= 0 ,0
Exp/Cntr=0.3,0.1

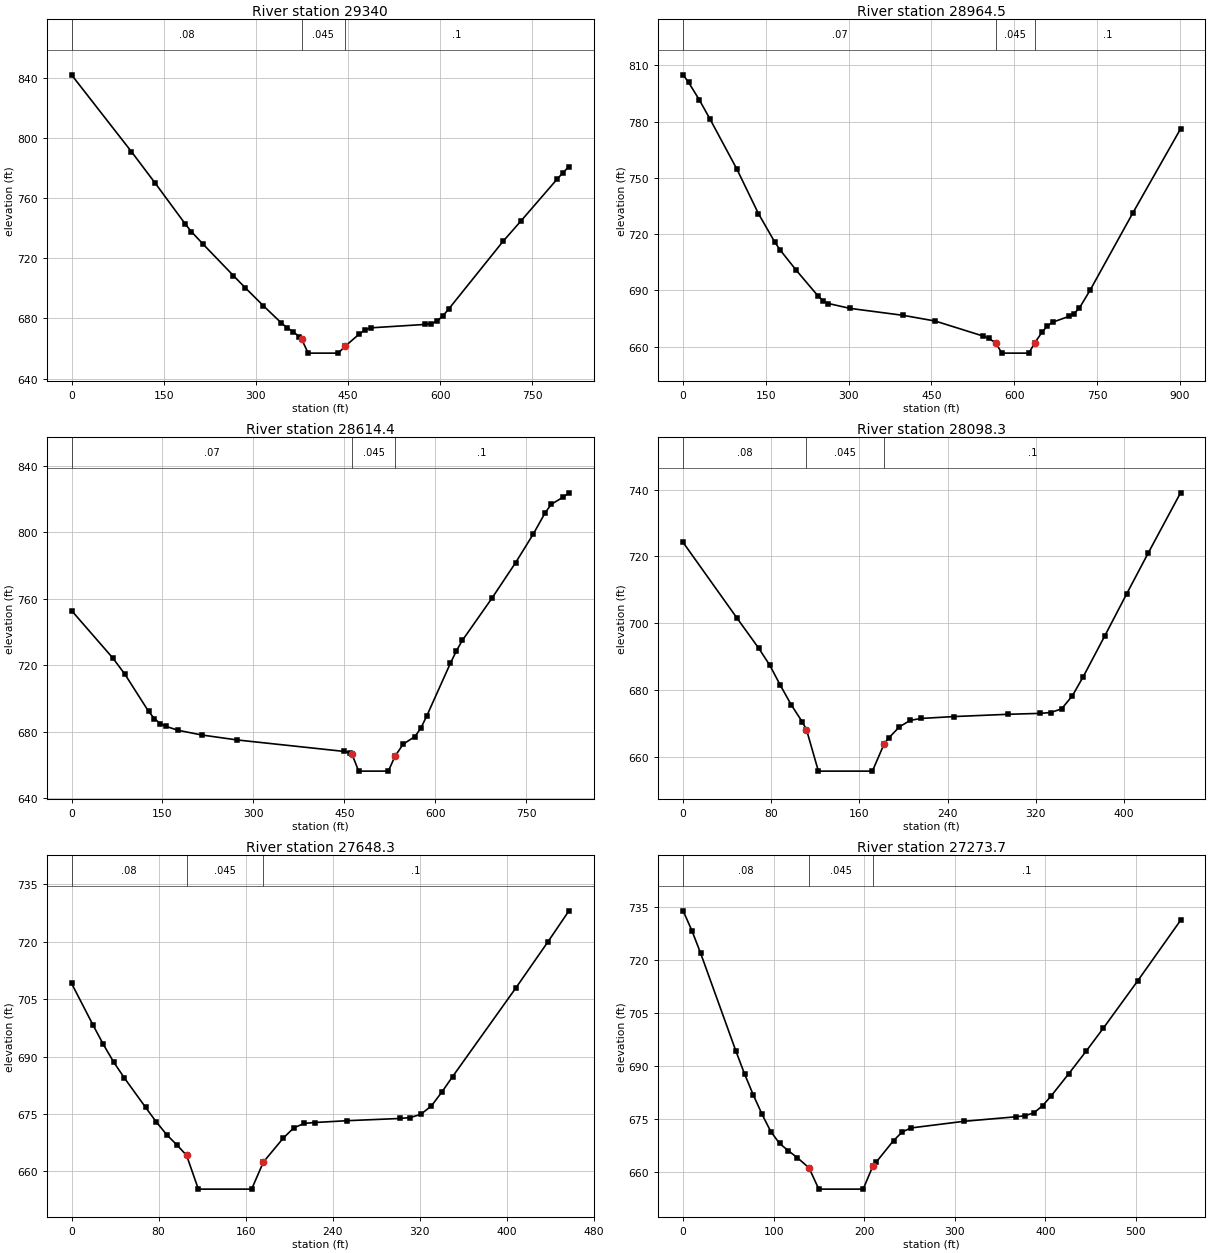
Type RM Length L Ch R = 1 ,29340   ,391.1,375.4,359.8
XS GIS Cut Line= 2
     1851309.259      504448.035     1852022.189      504832.106
#Sta/Elev= 30
       0  842.21    97.6  791.01   136.6  769.87   185.4  742.74   195.1  737.79
   214.6  729.28   263.4  708.56   282.9  700.38   312.2  688.49   341.5  677.02
   351.2  673.74     361   671.1   370.8  667.87  374.45   666.3  385.25  656.91
  434.25  656.91  445.05  661.36   468.3  669.58   478.1  672.46   487.8  673.76
   575.6  676.02   585.4  676.46   595.2  678.25   604.9  681.88   614.7  686.62
   702.5  731.34   731.8  744.97   790.3  772.65     800  777.01   809.8  781.12
#Mann= 3 , 0 , 0
       0     .08       0  374.45    .045       0  445.05      .1       0
Bank Sta=374.45,445.05
XS Rating Curve= 0 ,0
Exp/Cntr=0.3,0.1

Type RM Length L Ch R = 1 ,28964.5 ,349.8,350.1,350.3
XS GIS Cut Line= 4
     1851111.196      505219.985     1851359.807      505065.819
     1851795.918      504978.319     1851957.029      505008.874
#Sta/Elev= 30
       0  804.88     9.8  800.89    29.2  791.61    48.8  781.25    97.5  754.57
   136.5  730.89   165.8  715.88   175.5  711.63   204.8  700.79   243.8  687.25
   253.5  684.49   263.3  683.01   302.2  680.42   398.9   676.7   456.9  673.66
   543.9  665.64   553.6  664.46   566.7   661.9   577.5  656.57   626.5  656.57
   637.3  662.14   650.3  667.69     660  671.07   669.6  673.06   698.7  676.12
   708.3  677.61     718  680.59   737.3  690.05   814.5  731.08   901.3  776.08
#Mann= 3 , 0 , 0
       0     .07       0   566.7    .045       0   637.3      .1       0
Bank Sta=566.7,637.3
XS Rating Curve= 0 ,0
Exp/Cntr=0.3,0.1

Type RM Length L Ch R = 1 ,28614.4 ,533.7,516.1,498.3
XS GIS Cut Line= 2
     1851242.729      505440.402     1852048.979      505288.319
#Sta/Elev= 30
       0  752.96    68.4  724.24    87.9  714.67     127  692.28   136.7  687.82
   146.5  684.89   156.3  683.17   175.8  680.84   214.9  678.01   273.5  675.01
   449.3  668.13   459.1  667.29   462.8  666.29   473.6  656.25   522.6  656.25
   533.4   665.1     547  672.49   566.5  677.08   576.3  682.22     586  689.54
   625.1  721.35   634.9  728.71   644.6  734.97   693.5  760.42   732.6  781.86
   761.9   799.2   781.4  811.96   791.2  816.92   810.7  821.22   820.5  823.87
#Mann= 3 , 0 , 0
       0     .07       0   462.8    .045       0   533.4      .1       0
Bank Sta=462.8,533.4
XS Rating Curve= 0 ,0
Exp/Cntr=0.3,0.1

Type RM Length L Ch R = 1 ,28098.3 ,451.9,450,448.1
XS GIS Cut Line= 2
     1851830.299      505941.363     1852085.507      505568.967
#Sta/Elev= 26
       0   724.2    49.1  701.47    68.7  692.51    78.5  687.54    88.3  681.42
    98.1  675.62     108  670.57  111.95  668.18  122.75  655.78  171.75  655.78
  182.55  664.02   186.5  665.66   196.3  669.04   206.1  670.97   215.9  671.54
   245.4   672.1   294.4  672.78   323.9  673.06   333.7  673.32   343.5  674.42
   353.3  678.36   363.1  684.04   382.8  696.34   402.4  708.75     422     721
   451.4  739.05
#Mann= 3 , 0 , 0
       0     .08       0  111.95    .045       0  182.55      .1       0
Bank Sta=111.95,182.55
XS Rating Curve= 0 ,0
Exp/Cntr=0.3,0.1

Type RM Length L Ch R = 1 ,27648.3 ,373.7,374.6,375.6
XS GIS Cut Line= 2
     1852224.396      506180.513     1852450.958      505783.377
#Sta/Elev= 27
       0  709.14    19.5  698.38    29.2  693.19    38.9  688.49    48.6   684.4
    68.1  676.71    77.8  672.96    87.6  669.54    97.3  666.78  105.75  664.18
  116.55  655.36  165.55  655.36  176.35  662.44   194.6  668.69   204.3  671.38
     214  672.54   223.7  672.77   252.9  673.24   301.6  673.82   311.3  674.06
     321  674.91   330.8  677.11   340.5  680.78   350.2  684.75   408.6  708.02
   437.8  719.96   457.2  728.09
#Mann= 3 , 0 , 0
       0     .08       0  105.75    .045       0  176.35      .1       0
Bank Sta=105.75,176.35
XS Rating Curve= 0 ,0
Exp/Cntr=0.3,0.1

Type RM Length L Ch R = 1 ,27273.7 ,276.4,260.4,244.5
XS GIS Cut Line= 3
     1852525.637        506393.4     1852747.361      506040.877
     1852797.684      505917.775
#Sta/Elev= 30
       0   733.8     9.7  728.19    19.4  721.75    58.1  694.23    67.8  687.66
    77.5  681.68    87.2  676.19    96.8  671.32   106.5  667.96   116.2  665.89
   125.9  663.97  139.05  661.04  149.85  655.02  198.85  655.02  209.65   661.6
   213.1  662.62   232.4  668.76   242.1  671.23   251.8  672.34   309.9  674.21
     368  675.51   377.7   675.8   387.4  676.62   397.1  678.64   406.8   681.5
     426  687.71     445  694.03     464  700.54     502  713.95   549.4   731.1
#Mann= 3 , 0 , 0
       0     .08       0  139.05    .045       0  209.65      .1       0
Bank Sta=139.05,209.65
XS Rating Curve= 0 ,0
Exp/Cntr=0.3,0.1