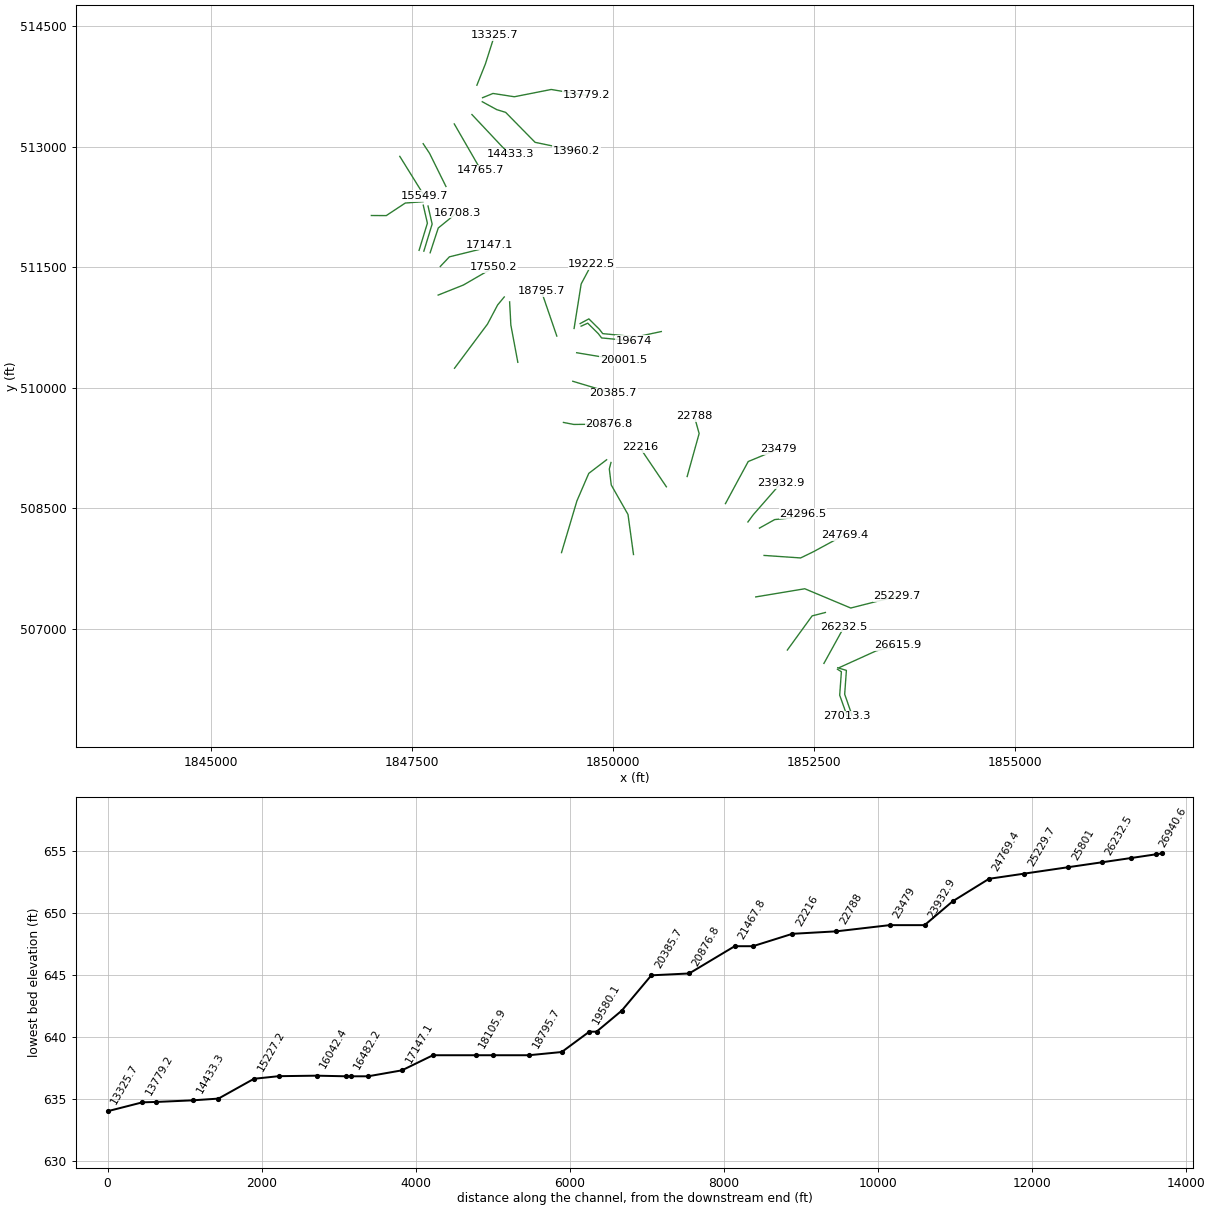
HEC-RAS study BLUECR.prj: BLUECR

--- BLUECR.g01 (geometry) --- (continued)

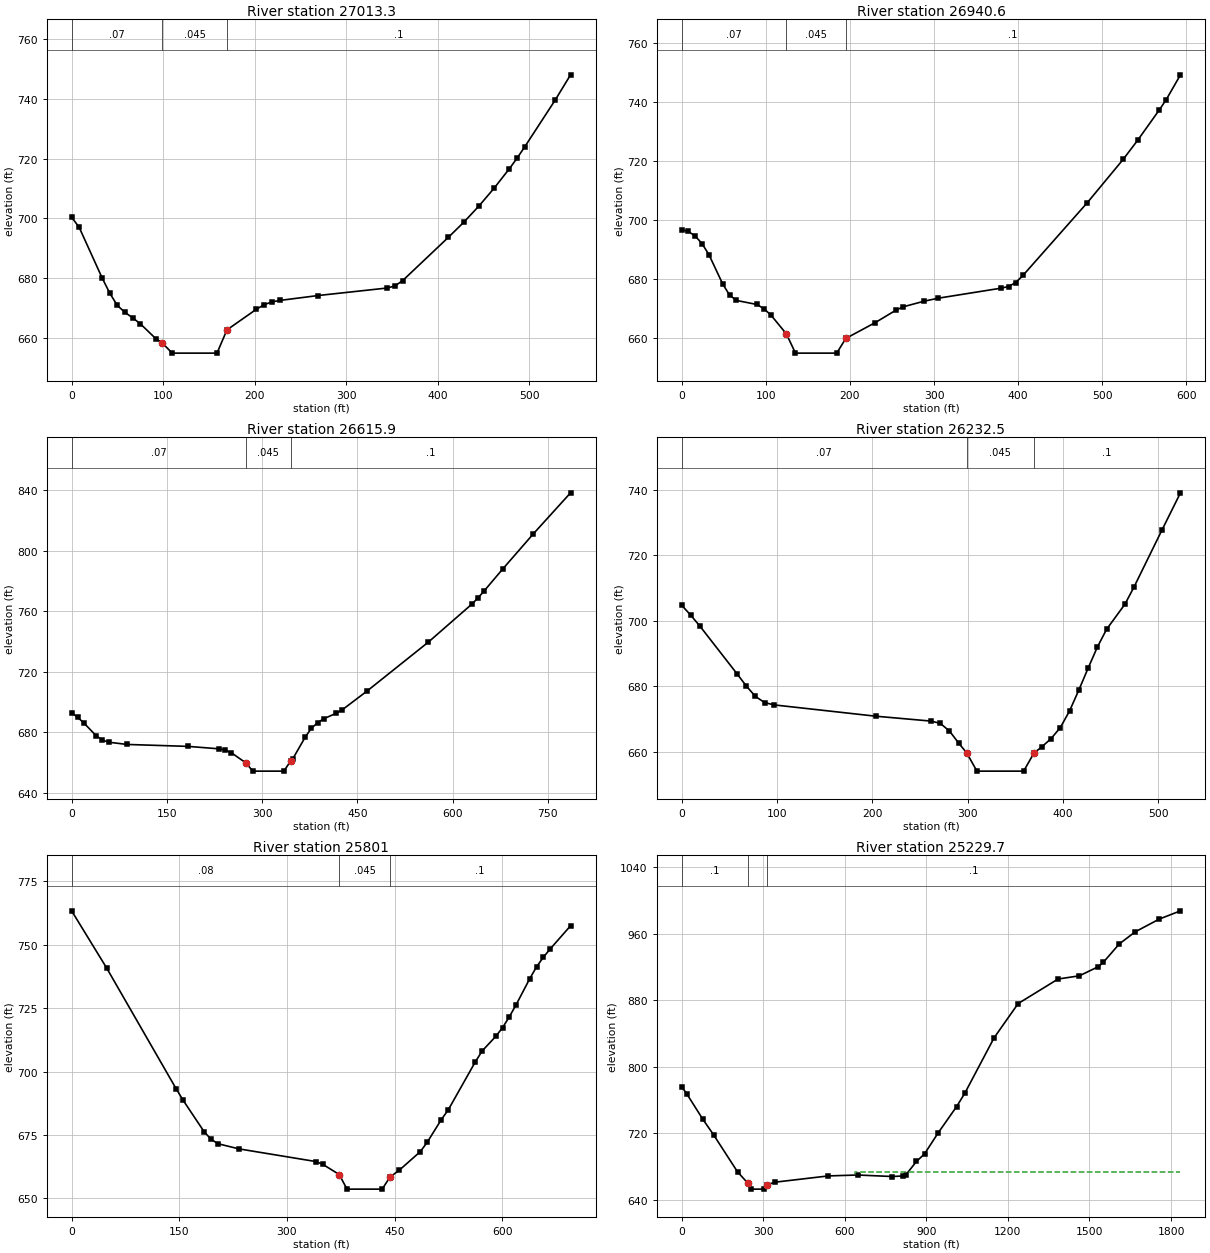
Type RM Length L Ch R = 1 ,27013.3 ,72.7,72.7,72.7
XS GIS Cut Line= 4
     1852793.122      506499.129     1852841.984      506468.505
     1852820.689      506176.631     1852914.823      505913.724
#Sta/Elev= 30
       0  700.37    8.31  696.93   33.26  680.06   41.66  674.91   49.97  670.77
   58.37  668.43   66.86   666.6   75.26  664.57   92.14   659.6   99.11  658.19
  109.91  654.79  158.91  654.79  169.71  662.57  202.04  669.53  210.44  671.03
  218.93  671.97  227.33  672.45  269.59  674.11  345.11  676.63  353.42  677.34
  361.74   679.1   411.8  693.64  428.51  698.66  445.14  704.12  461.85  710.15
  478.48  716.66  486.88  720.19  495.19  723.97  528.53  739.68  545.25   748.1
#Mann= 3 , 0 , 0
       0     .07       0   99.11    .045       0  169.71      .1       0
Bank Sta=99.11,169.71
XS Rating Curve= 0 ,0
Skew Angle= 30
Exp/Cntr=0.3,0.1

Type RM Length L Ch R = 1 ,26940.6 ,275.7,324.7,373.7
XS GIS Cut Line= 4
     1852796.247      506517.879     1852904.271      506485.029
     1852882.803      506189.239     1852973.157      505929.349
#Sta/Elev= 30
       0  696.58    8.14  695.99   16.28  694.44   24.42  691.86   32.56  688.14
   48.84  678.24   57.07  674.42   65.21   672.6   89.63  671.22   97.77  669.82
  106.09  667.69  124.61  661.24  135.41  654.72  184.41  654.72  195.21   659.7
  230.36   665.1  255.22  669.37  263.45  670.43   288.3  672.35  304.93  673.35
  380.18  676.78  388.67  677.32  397.16  678.68  405.65  681.06  482.29   705.8
  524.81  720.46  541.87  726.88  567.33  737.07  575.91   740.7  592.88  749.14
#Mann= 3 , 0 , 0
       0     .07       0  124.61    .045       0  195.21      .1       0
Bank Sta=124.61,195.21
XS Rating Curve= 0 ,0
Skew Angle= 30
Exp/Cntr=0.3,0.1

Type RM Length L Ch R = 1 ,26615.9 ,368.8,383.3,397.8
XS GIS Cut Line= 3
     1852814.144      506519.199       1853272.7      506727.159
     1853546.663       506795.36
#Sta/Elev= 30
       0  693.01     9.7  689.88    19.4  686.19    38.7  677.78    48.4  674.99
    58.1  673.55    87.2  672.05     184  670.75   232.4  669.14   242.1   668.3
   251.8   666.5  274.55  659.81  285.35  654.42  334.35  654.42  345.15  661.25
   348.6  662.75     368  676.96   377.6  682.71   387.3  686.37     397     689
   416.4  692.59     426  694.86   464.8  707.16   561.9  739.67   630.1  764.65
   639.8  768.73   649.5  773.36   678.7  787.82   727.4  811.28   785.8  838.27
#Mann= 3 , 0 , 0
       0     .07       0  274.55    .045       0  345.15      .1       0
Bank Sta=274.55,345.15
XS Rating Curve= 0 ,0
Exp/Cntr=0.3,0.1

Type RM Length L Ch R = 1 ,26232.5 ,434.9,431.6,428.8
XS GIS Cut Line= 2
     1852624.788       506572.27     1852877.609      507030.169
#Sta/Elev= 29
       0  704.78     9.7  701.68    19.4  698.31    58.1  683.83    67.8  680.11
    77.5  676.87    87.2     675    96.9   674.3   203.4  670.85   261.5  669.35
   271.2  668.67   280.9  666.33   290.6  662.61   298.9  659.68   309.7  654.07
   358.7  654.07   369.5   659.6   377.8   661.5   387.4  663.99   397.1  667.35
   406.8  672.44   416.5  678.81   426.2  685.46   435.9  691.92   445.6  697.36
   464.9  705.06   474.6  710.42   503.7   727.7   523.1  739.06
#Mann= 3 , 0 , 0
       0     .07       0   298.9    .045       0   369.5      .1       0
Bank Sta=298.9,369.5
XS Rating Curve= 0 ,0
Exp/Cntr=0.3,0.1

Type RM Length L Ch R = 1 ,25801   ,588.2,571.2,553.6
XS GIS Cut Line= 3
     1852169.833      506738.271     1852477.889       507163.03
     1852642.923      507205.285
#Sta/Elev= 30
       0  763.38    48.6  740.94   145.8  693.15   155.5  688.65   184.6  676.31
   194.3  673.32     204  671.57   233.2  669.54   340.1  664.56   349.8  663.47
  372.85  659.43  383.65  653.68  432.65  653.68  443.45   658.4   456.7   661.2
   485.8  668.46   495.6  672.24     515  681.07   524.7  684.93   562.6  703.94
     572  708.16     591  713.93   600.4  717.34   609.9  721.66   619.4  726.44
   638.3  736.67   647.7  741.29   657.2  745.09   666.7  748.35   695.1  757.49
#Mann= 3 , 0 , 0
       0     .08       0  372.85    .045       0  443.45      .1       0
Bank Sta=372.85,443.45
XS Rating Curve= 0 ,0
Exp/Cntr=0.3,0.1

Type RM Length L Ch R = 1 ,25229.7 ,465.6,460.3,455.1
XS GIS Cut Line= 4
     1851776.995      507398.977     1852386.717      507500.366
     1852958.245      507260.783     1853536.587      507407.831
#Sta/Elev= 30
       0  776.35    19.6  767.42    78.5  736.97   117.7  718.48     206  673.88
  244.35  660.14  255.15  653.16  304.15  653.16  314.95  658.51   343.4  661.48
   539.6  669.01   647.6  670.11   775.5  668.29   814.8  668.98   824.7  670.25
     864  686.41   893.5  695.46   942.7  720.22  1011.6  752.33  1041.1  767.97
  1149.3  834.84  1237.8  875.95  1384.6  905.41  1462.8  909.24  1531.3  920.03
  1550.8  925.37  1609.6  947.54  1668.2  962.05  1756.3   977.3  1834.6  987.27
#Mann= 3 , 0 , 0
       0      .1       0  244.35    .045       0  314.95      .1       0
#XS Ineff= 2 , 0
                          637.33          674.24
Permanent Ineff=
       F       F
Bank Sta=244.35,314.95
XS Rating Curve= 0 ,0
Exp/Cntr=0.3,0.1

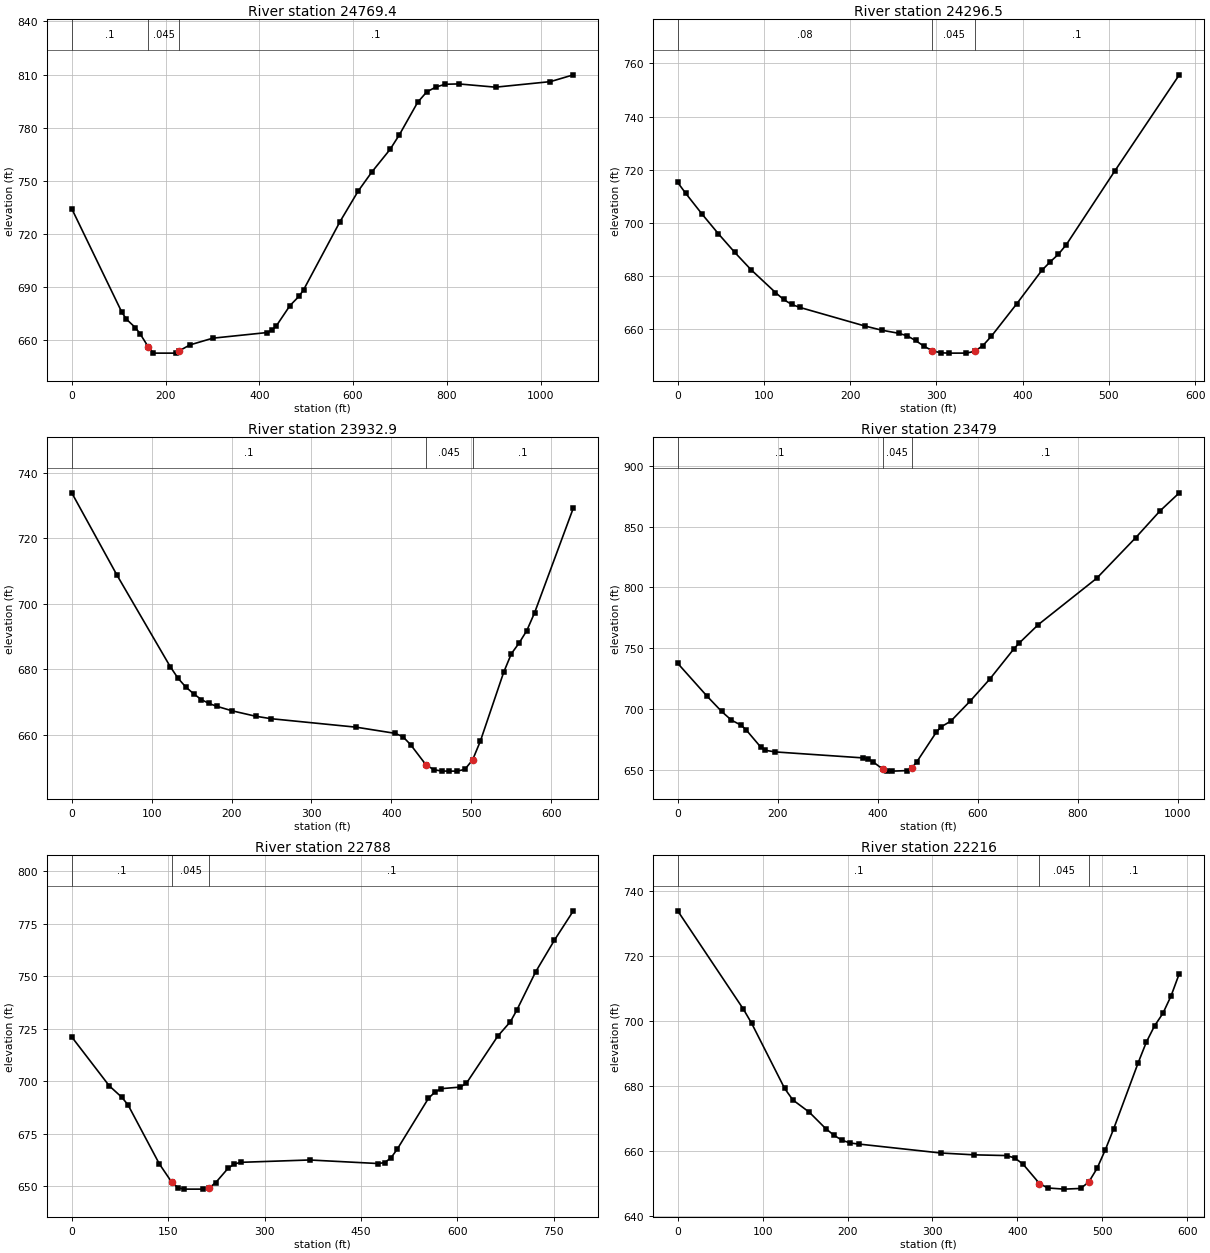
Type RM Length L Ch R = 1 ,24769.4 ,469.1,472.9,476.7
XS GIS Cut Line= 4
     1851880.525      507914.891     1852335.328      507883.699
     1852492.272      507960.088     1852879.002      508169.123
#Sta/Elev= 30
       0  734.27   106.7  675.91   116.4  671.95   135.8   667.1   145.5  663.78
  163.55  656.13  174.35  652.74  223.35  652.74  227.74  653.84   252.2  657.38
   300.7  661.17   417.1  664.37   426.8  665.57   436.5  668.16   465.6  679.61
     485  684.88   494.7  688.55   572.2  726.95     611  744.21   640.2  754.99
   679.3  767.82   698.8  775.94   737.9  794.32   757.4  800.23     777  802.93
   796.5   804.5   825.8  804.68     904  802.85  1021.2  805.99    1070  809.82
#Mann= 3 , 0 , 0
       0      .1       0  163.55    .045       0  227.74      .1       0
Bank Sta=163.55,227.74
XS Rating Curve= 0 ,0
Exp/Cntr=0.3,0.1

Type RM Length L Ch R = 1 ,24296.5 ,346.6,363.6,380.4
XS GIS Cut Line= 4
     1851822.886      508254.807     1852012.583      508360.722
      1852226.24      508382.362     1852365.941      508436.057
#Sta/Elev= 30
       0  715.18     9.4  711.05    28.3  703.25    47.2  695.86    66.1  688.88
      85  682.35   113.4  673.74   122.8  671.12   132.2  669.25   141.7  668.13
   217.3  661.11   236.8  659.55   256.3  658.39   266.1  657.44   275.8  655.68
   285.6  653.52   295.4  651.81   305.1  651.04   314.9  650.92   334.4  650.93
   344.2  651.55   353.9  653.75   363.7  657.26     393  669.42   422.2  682.06
     432   685.3   441.4  688.12   450.7  691.78   506.8  719.47   581.7  755.72
#Mann= 3 , 0 , 0
       0     .08       0   295.4    .045       0   344.2      .1       0
Bank Sta=295.4,344.2
XS Rating Curve= 0 ,0
Exp/Cntr=0.3,0.1

Type RM Length L Ch R = 1 ,23932.9 ,448.8,453.9,458.8
XS GIS Cut Line= 3
      1851679.44      508331.196     1851747.148      508422.342
      1852085.69      508809.495
#Sta/Elev= 30
       0  733.82    56.8  708.65   123.2  680.87     133  677.31   142.6  674.67
   152.4   672.6   162.1  670.82   171.8  669.62   181.5  668.76   200.9  667.37
     230  665.74   249.4  664.98   356.1  662.39   404.6  660.52   414.4  659.51
   424.1  657.07   443.5  650.87   453.2  649.44   462.9  649.03   472.6     649
   482.3     649     492  649.54   501.7  652.43   511.4  658.13   540.5  679.06
   550.2  684.78   559.9  688.04   569.6  691.86   579.3  697.28   627.8  729.21
#Mann= 3 , 0 , 0
       0      .1       0   443.5    .045       0   501.7      .1       0
Bank Sta=443.5,501.7
XS Rating Curve= 0 ,0
Exp/Cntr=0.3,0.1

Type RM Length L Ch R = 1 ,23479   ,685.9,691,695.9
XS GIS Cut Line= 3
     1851400.027        508559.3     1851683.013      509082.737
     1852060.425      509238.741
#Sta/Elev= 30
       0   737.6    58.5  710.71    87.8  698.08   107.3  690.96   126.8  686.74
   136.6  683.07   165.8   668.9   175.6   666.1   195.1  664.79   370.7  659.87
   380.4  658.98   390.2  656.78   409.7  650.83   419.4  649.32   429.2     649
   458.5  649.43   468.2  651.62     478  656.44     517   680.8   526.8  685.36
   546.3  690.08   585.3  706.68   624.2  724.61   672.8  749.65   682.6  754.04
   721.4  769.44   838.1  807.49   915.9  840.75   964.5  862.75  1003.4  877.74
#Mann= 3 , 0 , 0
       0      .1       0   409.7    .045       0   468.2      .1       0
Bank Sta=409.7,468.2
XS Rating Curve= 0 ,0
Exp/Cntr=0.3,0.1

Type RM Length L Ch R = 1 ,22788   ,552.3,572,591.6
XS GIS Cut Line= 3
     1850923.776      508896.168      1851072.77      509430.827
     1851012.054      509647.917
#Sta/Elev= 30
       0  721.03    58.4  697.71    77.9  692.28    87.6  688.62   136.3  660.51
   155.8   651.7   165.5  649.11   175.3   648.5   204.5   648.5   214.2  649.18
     224  651.62   243.4  658.49   253.2   660.5   262.9  661.27     370  662.39
   477.1  660.69   486.9  661.17   496.6  663.38   506.3  667.49     555  691.79
   564.8  694.68   574.6  696.37     604  697.12   613.8  698.86   662.8  721.41
   682.4  728.26   692.2  733.67   721.6  751.97     751  767.16   780.4  781.13
#Mann= 3 , 0 , 0
       0      .1       0   155.8    .045       0   214.2      .1       0
Bank Sta=155.8,214.2
XS Rating Curve= 0 ,0
Exp/Cntr=0.3,0.1

Type RM Length L Ch R = 1 ,22216   ,522.5,511.8,501
XS GIS Cut Line= 2
     1850665.175      508768.834     1850334.228        509258.2
#Sta/Elev= 30
       0  733.97    77.5  703.65    87.2  699.29   125.9  679.32   135.6  675.76
     155  671.98   174.3  666.94     184  664.89   193.7  663.32   203.4  662.49
   213.1  662.18   309.9  659.42   348.6  658.86   387.4  658.63   397.1  657.88
   406.8  655.97   426.1  650.02   435.8  648.66   455.2   648.3   474.6  648.51
   484.2   650.5   493.9  654.67   503.6  660.37   513.3  666.73   542.3  687.15
     552  693.57   561.7  698.58   571.4  702.37   581.1  707.78   590.8  714.66
#Mann= 3 , 0 , 0
       0      .1       0   426.1    .045       0   484.2      .1       0
Bank Sta=426.1,484.2
XS Rating Curve= 0 ,0
Exp/Cntr=0.3,0.1

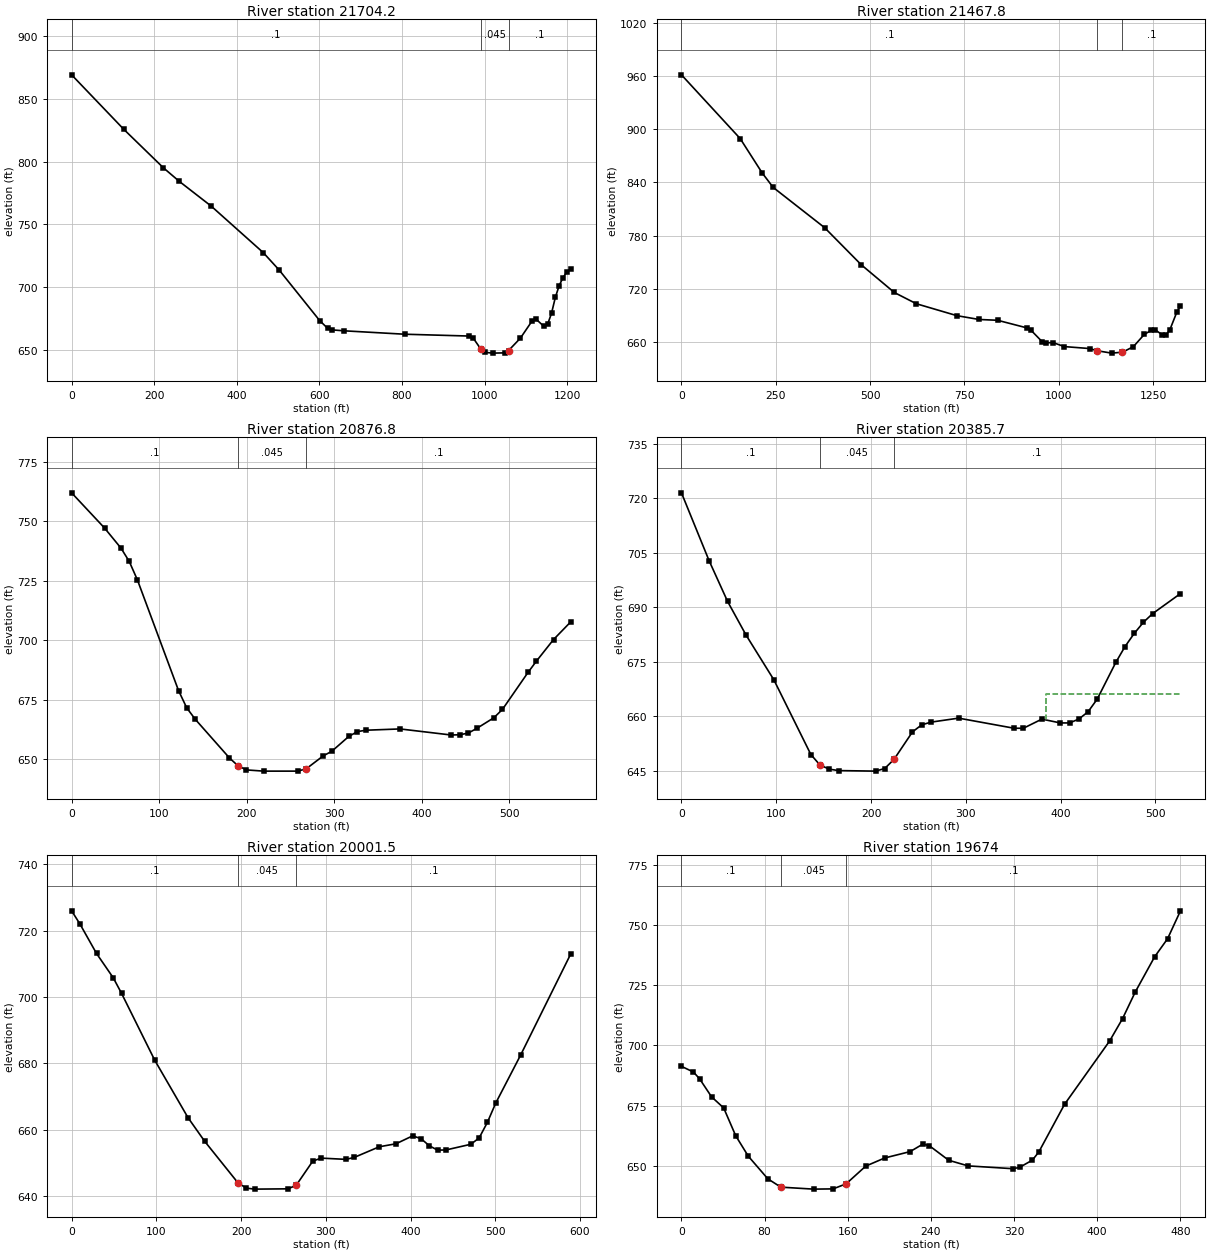
Type RM Length L Ch R = 1 ,21704.2 ,259.7,236.4,212.6
XS GIS Cut Line= 5
     1850256.349      507926.285      1850187.99      508424.331
     1849979.874      508790.651     1849955.568      508990.304
     1849976.401      509071.033
#Sta/Elev= 30
       0  869.07   125.7  825.86   222.4  794.94     261  784.11   338.4  764.35
     464  727.42   502.7   713.5   600.7  673.26   620.3  666.98   630.1  665.83
   659.5  665.09   806.4  662.37   962.3  660.91   971.9  659.61   991.1  650.49
  1000.6  647.94  1019.8   647.3  1048.5  647.51  1058.1  649.33  1086.8  659.21
  1115.6  673.15  1125.2  674.25  1143.7  668.64  1152.9  670.41  1162.2  679.02
  1171.5  691.74  1180.7  701.04    1190  707.48  1199.3  711.92  1208.5  714.52
#Mann= 3 , 0 , 0
       0      .1       0   991.1    .045       0  1058.1      .1       0
Bank Sta=991.1,1058.1
XS Rating Curve= 0 ,0
Exp/Cntr=0.3,0.1

Type RM Length L Ch R = 1 ,21467.8 ,605.3,591,576.4
XS GIS Cut Line= 4
     1849361.167      507950.156     1849552.776      508593.328
     1849700.282      508935.665     1849921.888      509104.453
#Sta/Elev= 30
       0  961.59   155.6  889.62     214  850.72   243.2  834.39   379.3  789.01
   476.6  747.03   564.1  715.77   622.5  703.06     730   689.6   788.8   685.3
   837.9  684.39   916.4   675.7   926.2  673.21   955.6  660.32   965.4  658.99
     985  659.17  1014.4   654.7  1082.3  652.45  1101.5     650  1139.9   647.3
  1168.7  648.34  1197.6  654.58  1226.4  668.37  1245.6  673.24  1255.2   673.7
  1274.4  667.89    1284  668.04  1293.6  672.94  1312.8  693.63  1322.4  700.71
#Mann= 3 , 0 , 0
       0      .1       0  1101.5    .045       0  1168.7      .1       0
Bank Sta=1101.5,1168.7
XS Rating Curve= 0 ,0
Exp/Cntr=0.3,0.1

Type RM Length L Ch R = 1 ,20876.8 ,497.9,491.2,484.4
XS GIS Cut Line= 3
     1849385.117      509568.885     1849514.241      509543.929
     1849952.609      509548.269
#Sta/Elev= 30
       0  761.91    37.6  747.14    56.4  738.69    65.8  733.12    75.2   725.3
   122.1  678.92   131.5  671.63   141.2  666.86   180.2  650.65     190  647.34
   199.7  645.61   219.2   645.1   258.2   645.1   267.9  646.06   287.4  651.52
   297.1  653.41   316.6  659.68   326.4  661.69   336.1  662.27   375.1  662.81
   433.5  660.26   443.3  660.36     453  661.07   462.7  663.03   482.2  667.49
     492  670.99   521.2  686.51   530.9   691.3   550.4  700.34   569.9   707.7
#Mann= 3 , 0 , 0
       0      .1       0     190    .045       0   267.9      .1       0
Bank Sta=190,267.9
XS Rating Curve= 0 ,0
Exp/Cntr=0.3,0.1

Type RM Length L Ch R = 1 ,20385.7 ,381.3,384.1,387
XS GIS Cut Line= 2
     1849501.448      510080.727     1850005.739      509929.828
#Sta/Elev= 30
       0  721.47    29.2  702.78    48.7  691.59    68.2  682.33    97.5  670.05
   136.5  649.52   146.2   646.6     156  645.49   165.7   645.1   204.7  644.95
   214.4  645.67   224.2  648.17   243.7  655.74   253.4  657.67   263.2  658.42
   292.4  659.52   350.9  656.74   360.7  656.74   380.2  659.25   399.7   658.2
   409.4   658.2   419.2  659.27   428.9  661.26   438.6  664.76   458.2  674.85
   467.9   679.2   477.6   682.8   487.4   685.9   497.1  688.27   526.4  693.77
#Mann= 3 , 0 , 0
       0      .1       0   146.2    .045       0   224.2      .1       0
#XS Ineff= 2 , 0
                          384.62          666.24
Permanent Ineff=
       F       F
Bank Sta=146.2,224.2
XS Rating Curve= 0 ,0
Exp/Cntr=0.3,0.1

Type RM Length L Ch R = 1 ,20001.5 ,359.4,327.5,299.4
XS GIS Cut Line= 2
     1849549.415      510435.788      1850130.38      510339.624
#Sta/Elev= 30
       0     726     9.8  722.04    29.4  713.14    49.1  705.82    58.9  701.14
    98.1  680.96   137.4  663.63     157  656.53   196.3     644   206.1  642.41
   215.9   642.1   255.2  642.19     265  643.24   284.6  650.54   294.4  651.45
   323.9  651.07   333.7  651.68   363.1  654.87   382.8  655.77   402.4  658.15
   412.2  657.35     422   655.2   431.8  653.86   441.6   653.9   471.1  655.62
   480.9  657.52   490.7  662.24   500.5  668.03     530  682.57   588.9  712.94
#Mann= 3 , 0 , 0
       0      .1       0   196.3    .045       0     265      .1       0
Bank Sta=196.3,265
XS Rating Curve= 0 ,0
Exp/Cntr=0.3,0.1

Type RM Length L Ch R = 1 ,19674   ,91.9,93.9,96.5
XS GIS Cut Line= 5
     1849604.927      510766.233     1849687.158      510803.331
     1849819.103      510672.776      1849859.38      510619.998
     1850262.158      510581.109
#Sta/Elev= 30
       0  691.33   11.57  688.95   17.42  686.17   28.99  678.67  40.624  674.08
  52.194  662.54  64.279  654.07  83.112  644.67  95.647  641.22 127.079   640.4
 145.913   640.5 158.447   642.6 177.281  649.94   195.6  653.33 219.962  655.96
 232.368   659.1 238.538  658.39 257.115  652.37 275.692  650.04  319.08  648.87
 325.251  649.42 337.656  652.44 343.827  655.82 368.574  675.58 411.963  701.86
 424.368  711.11  436.71  722.25 455.286  736.79 467.692  744.25 480.098  755.83
#Mann= 3 , 0 , 0
       0      .1       0  95.647    .045       0 158.447      .1       0
Bank Sta=95.647,158.447
XS Rating Curve= 0 ,0
Skew Angle= 50
Exp/Cntr=0.3,0.1

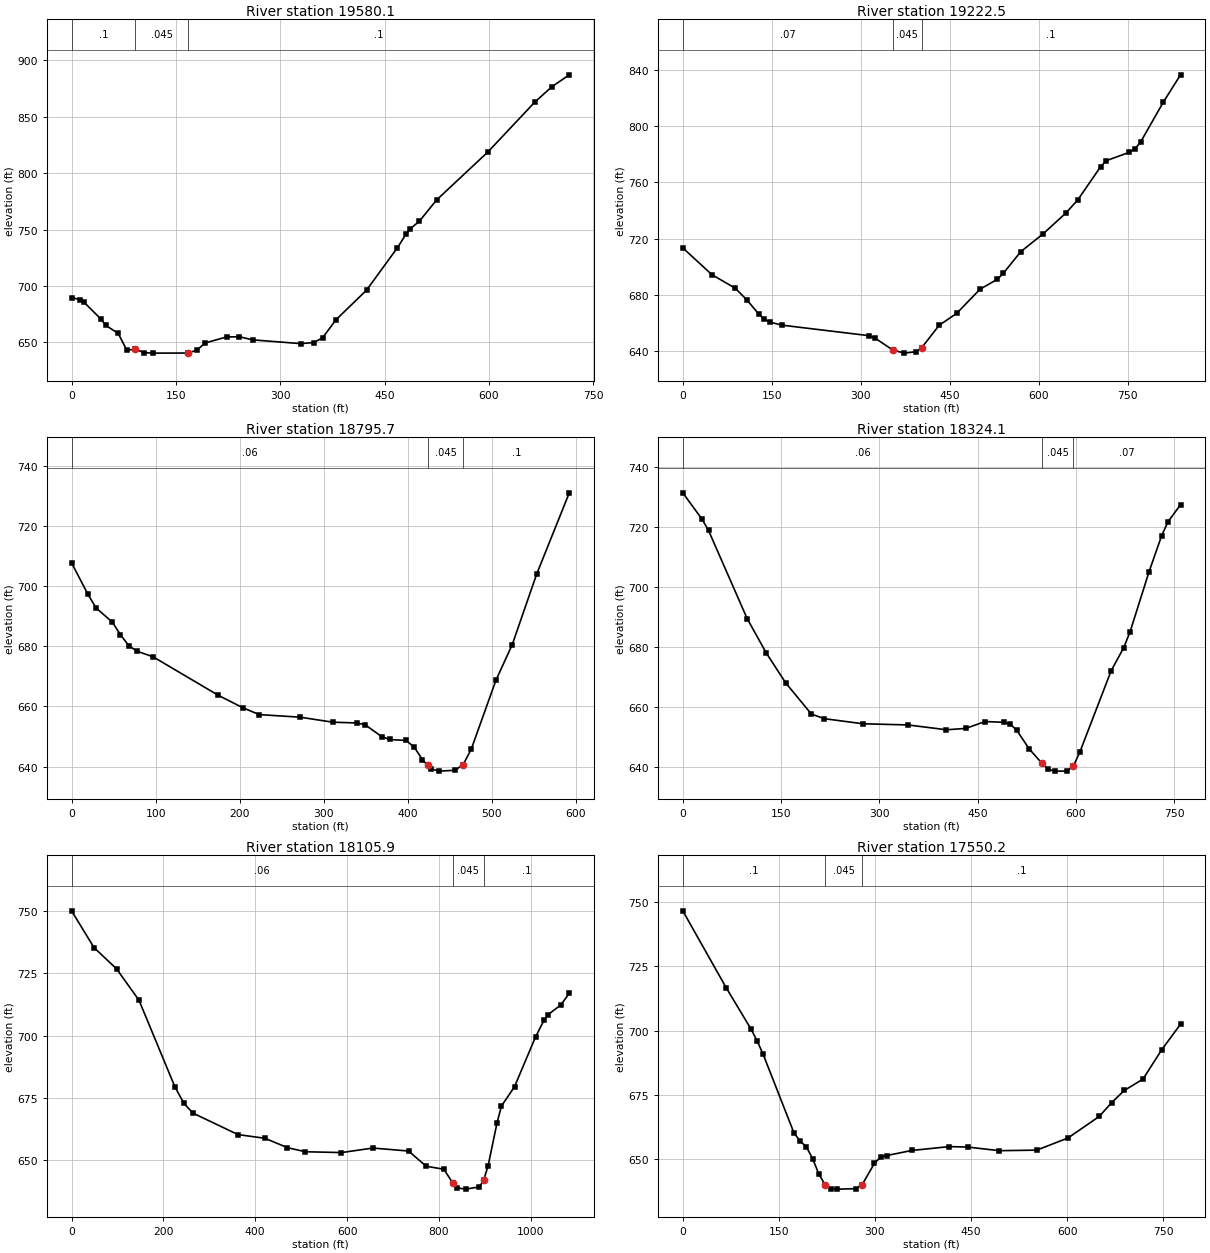
Type RM Length L Ch R = 1 ,19580.1 ,291.6,357.6,418.3
XS GIS Cut Line= 6
     1849592.774      510798.351     1849701.325      510856.803
     1849833.269      510726.248     1849873.547       510673.47
     1850293.277      510633.547     1850602.305      510699.519
#Sta/Elev= 30
       0  689.56  12.213  687.94  18.255  685.32  42.681  670.31  48.788  665.14
  67.043  657.92  79.256  643.16   91.79  643.72 104.389  640.87 116.923   640.4
 167.189  640.47 179.723  642.94 192.258  649.46 222.919  654.75 241.238  654.93
 260.136  652.18 329.493  648.82 348.391  649.78  360.99  654.14 379.887  669.88
 423.983  696.26 468.142  733.68 480.741  745.88  487.04  750.86 499.639  757.16
 524.579  776.15 598.435   818.8 666.121  863.18  690.74  876.78 715.358  887.14
#Mann= 3 , 0 , 0
       0      .1       0   91.79    .045       0 167.189      .1       0
Bank Sta=91.79,167.189
XS Rating Curve= 0 ,0
Skew Angle= 50
Exp/Cntr=0.3,0.1

Type RM Length L Ch R = 1 ,19222.5 ,416.2,426.8,438.1
XS GIS Cut Line= 3
     1849517.591      510737.699     1849605.511      511290.908
     1849736.775      511537.396
#Sta/Elev= 30
       0  713.45    49.1  694.42    88.4  684.85   108.1  676.53   127.8  666.62
   137.6  662.78   147.4  660.73   167.1  658.61   314.5  651.12   324.3  649.42
   353.8  641.02   373.4  638.76   393.1  639.74   402.9   642.6   432.4  658.52
   461.9  666.97   501.2  684.09   530.7  691.22   540.5  695.38   569.8  710.67
   608.3  723.62   646.8  738.47   666.1  747.52   704.6     771   714.2  775.33
   752.7  781.18   762.4  783.65     772   788.5   810.5  816.95   839.4  836.23
#Mann= 3 , 0 , 0
       0     .07       0   353.8    .045       0   402.9      .1       0
Bank Sta=353.8,402.9
XS Rating Curve= 0 ,0
Exp/Cntr=0.3,0.1

Type RM Length L Ch R = 1 ,18795.7 ,477.7,471.5,465.1
XS GIS Cut Line= 2
     1849302.675      510642.676       1849110.4      511202.833
#Sta/Elev= 30
       0  707.71    19.4   697.3    29.1  692.73    48.5  688.02    58.2  683.83
      68  680.19    77.7  678.37    97.1  676.47   174.8  663.66   203.9  659.55
   223.3  657.28   271.8  656.43   310.7  654.76   339.8   654.5   349.5  653.86
   368.9     650   378.6  649.01   398.1  648.68   407.8  646.42   417.5  642.31
   423.7640.3797   427.2  639.29   436.9   638.5   456.3  638.78     466  640.69
   475.7   645.9   504.9  668.69   524.3  680.52   553.4  703.98   592.2  730.97
#Mann= 3 , 0 , 0
       0     .06       0   423.7    .045       0     466      .1       0
Bank Sta=423.7,466
XS Rating Curve= 0 ,0
Exp/Cntr=0.3,0.1

Type RM Length L Ch R = 1 ,18324.1 ,230.4,218.2,206
XS GIS Cut Line= 3
     1848817.854      510316.539     1848731.116       510779.67
     1848715.881      511067.772
#Sta/Elev= 30
       0  731.23    29.4  722.44    39.3  718.69    98.2  689.33   127.6  677.81
   157.1  667.89   196.3  657.51     216  655.98   274.9  654.28   343.6  653.89
   402.5  652.28   431.9  652.73   461.4  655.02   490.4  654.77     500  654.12
   509.6  652.14   528.9  645.86   548.1  641.12   557.7   639.1   567.4   638.5
   586.6   638.5   596.2  640.21   605.8  644.72   653.9     672   673.1  679.68
   682.8     685   711.6   704.9   730.8   716.9   740.4  721.53   759.7  727.28
#Mann= 3 , 0 , 0
       0     .06       0   548.1    .045       0   596.2     .07       0
Bank Sta=548.1,596.2
XS Rating Curve= 0 ,0
Exp/Cntr=0.3,0.1

Type RM Length L Ch R = 1 ,18105.9 ,571.7,555.7,539.6
XS GIS Cut Line= 4
     1848030.539      510242.937     1848440.695      510792.416
     1848566.998      511030.697     1848649.029      511129.655
#Sta/Elev= 30
       0  749.97      49  735.23      98  726.72   146.9  714.14   225.3  679.36
   244.9  672.81   264.5  668.93   362.4  660.35   421.2  658.86   470.2   655.1
   509.4  653.47   587.7  653.14   656.3  654.95   733.8  653.76   772.4  647.66
   810.9  646.46   830.2   640.9   839.8  638.99     859   638.5   887.9   639.4
   897.6  642.14   907.2  647.94   926.5  665.02   936.1  671.76   964.6  679.53
  1010.4  699.46  1028.8  706.12    1038  708.43  1065.5  712.28  1083.9  716.96
#Mann= 3 , 0 , 0
       0     .06       0   830.2    .045       0   897.6      .1       0
Bank Sta=830.2,897.6
XS Rating Curve= 0 ,0
Exp/Cntr=0.3,0.1

Type RM Length L Ch R = 1 ,17550.2 ,406.3,403.2,400
XS GIS Cut Line= 3
     1847827.414      511153.093     1848141.216      511278.093
     1848521.425      511498.145
#Sta/Elev= 30
       0  746.42    67.6  716.67   106.2   700.7   115.8  696.11   125.5  690.76
   173.7  660.22   183.4  657.11     193  654.87   202.7  650.31   212.3  644.42
     222  640.27   231.6   638.7   241.3   638.5   270.2  638.66   279.9  640.15
   299.2  648.51   308.8  650.92   318.5  651.53   357.3  653.48   415.9  654.99
   445.2  654.81     494  653.41   552.6  653.62   601.4  658.33   650.2  666.69
   669.7  672.08   689.2  676.75   718.5  681.17   747.8  692.57   777.1  702.45
#Mann= 3 , 0 , 0
       0      .1       0     222    .045       0   279.9      .1       0
Bank Sta=222,279.9
XS Rating Curve= 0 ,0
Exp/Cntr=0.3,0.1

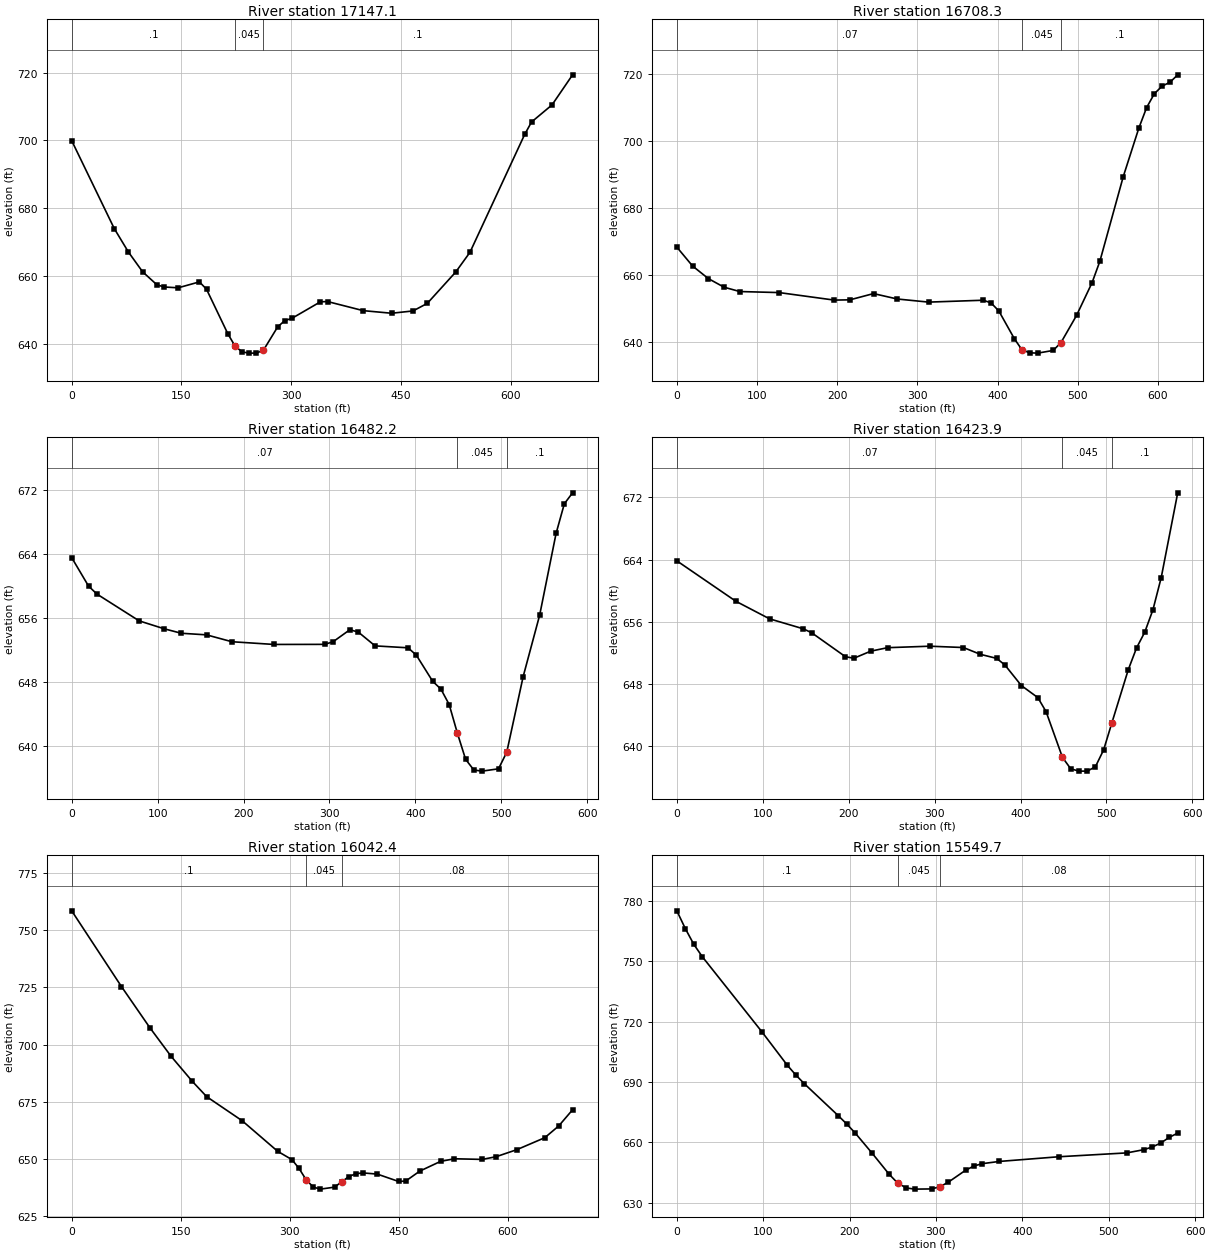
Type RM Length L Ch R = 1 ,17147.1 ,428.8,438.8,448.7
XS GIS Cut Line= 4
     1847853.456      511508.562     1847966.737      511628.353
     1848335.227      511719.499     1848461.529      511780.697
#Sta/Elev= 30
       0  699.93    58.2     674    77.6  667.07      97  661.25   116.4  657.45
   126.1  656.79   145.5  656.54   174.6  658.29   184.3  656.13   213.5  642.97
   223.3  639.36     233  637.63   242.7  637.28   252.5  637.28   262.2  638.17
   281.7  645.05   291.4  646.88   301.1  647.54   340.1  652.42   349.8  652.49
   398.5  649.81   437.4  649.04   466.6  649.72   486.1  651.94     525  661.19
   544.5  667.01   619.3  701.77   628.7  705.44   656.7  710.48   684.8  719.35
#Mann= 3 , 0 , 0
       0      .1       0   223.3    .045       0   262.2      .1       0
Bank Sta=223.3,262.2
XS Rating Curve= 0 ,0
Exp/Cntr=0.3,0.1

Type RM Length L Ch R = 1 ,16708.3 ,200.9,226,251.2
XS GIS Cut Line= 3
     1847727.154      511679.135     1847828.122      511986.845
     1848061.389      512176.814
#Sta/Elev= 30
       0  668.38    19.6  662.76    39.2  659.02    58.9  656.44    78.5  655.15
   127.6  654.84   196.3   652.6   215.9  652.68   245.3  654.54   274.8  652.93
     314     652   382.1  652.56   391.8  651.78   401.5   649.4   420.9  641.12
   430.5 637.755   440.3  636.89     450   636.8   469.4   637.6   479.1  639.94
   498.5  648.02   517.9   657.8   527.6  664.17   556.8  689.41   576.2  703.84
   585.9  709.95   595.6  714.11   605.3  716.37     615   717.5   624.7  719.72
#Mann= 3 , 0 , 0
       0     .07       0   430.5    .045       0   479.1      .1       0
Bank Sta=430.5,479.1
XS Rating Curve= 0 ,0
Exp/Cntr=0.3,0.1

Type RM Length L Ch R = 1 ,16482.2 ,58,58.4,58.4
XS GIS Cut Line= 3
     1847648.959      511698.759     1847752.258      512036.432
     1847701.042      512260.391
#Sta/Elev= 30
       0  663.51    19.6  659.95    29.4  658.95    78.5   655.6   107.9   654.6
   127.5  654.05   156.9  653.85   186.4  652.99   235.4  652.65   294.3  652.66
   304.1  652.98   323.7  654.49   333.5   654.2   353.1  652.47   391.4  652.23
     401  651.32   420.1  648.04   429.7  647.06   439.3  645.13   448.8  641.56
   458.4  638.28     468  636.94   477.6   636.8   496.7  637.09   506.3  639.17
   525.4  648.63   544.6  656.32   563.7  666.54   573.3  670.25   582.9  671.62
#Mann= 3 , 0 , 0
       0     .07       0   448.8    .045       0   506.3      .1       0
Bank Sta=448.8,506.3
XS Rating Curve= 0 ,0
Exp/Cntr=0.3,0.1

Type RM Length L Ch R = 1 ,16423.9 ,409.4,381.5,353.9
XS GIS Cut Line= 3
     1847589.694      511709.254     1847692.993      512046.928
     1847641.778      512270.886
#Sta/Elev= 30
       0  663.85    68.7  658.65   107.9  656.39   147.1  655.11   156.9   654.6
   196.2  651.52     206  651.32   225.6  652.23   245.2  652.68   294.3  652.87
   333.5   652.7   353.1  651.83   372.3   651.3   381.8  650.45     401   647.8
   420.1  646.26   429.7  644.45   448.8  638.56   458.4   637.1     468   636.8
   477.6   636.8   487.1  637.36   496.7  639.54   506.3  643.02   525.4  649.86
     535  652.65   544.6  654.69   554.1  657.57   563.7   661.7   582.9   672.6
#Mann= 3 , 0 , 0
       0     .07       0   448.8    .045       0   506.3      .1       0
Bank Sta=448.8,506.3
XS Rating Curve= 0 ,0
Exp/Cntr=0.3,0.1

Type RM Length L Ch R = 1 ,16042.4 ,528.8,492.7,456.6
XS GIS Cut Line= 4
     1846996.034      512142.459     1847181.581      512141.374
     1847418.126      512297.624      1847637.31        512313.9
#Sta/Elev= 30
       0  758.44    68.4  725.36   107.4  707.41   136.7  694.87     166  683.88
   185.6  677.25   234.4  666.73   283.3  653.36   302.9  649.73   312.6   645.9
   322.4  640.94   332.2  637.75     342  636.85   361.5  637.72   371.3  640.06
   381.1  642.32   390.8   643.6   400.6  643.93   420.2  643.42   449.5   640.2
   459.3  640.37   478.6  644.71   507.3  648.98   526.4  650.12   564.6  649.83
   583.7  651.02   612.4  654.12   650.6  659.32   669.7  664.44   688.8  671.52
#Mann= 3 , 0 , 0
       0      .1       0   322.4    .045       0   371.3     .08       0
Bank Sta=322.4,371.3
XS Rating Curve= 0 ,0
Exp/Cntr=0.3,0.1

Type RM Length L Ch R = 1 ,15549.7 ,324.7,322.5,320.3
XS GIS Cut Line= 2
     1847349.767      512878.136     1847655.756      512385.515
#Sta/Elev= 30
       0  774.93     9.8  766.11    19.7  758.26    29.5  752.14    98.3  714.99
   127.8  698.34   137.6  693.52   147.4   689.2   186.8   673.3   196.6  669.17
   206.4   664.7   226.1  654.64   245.7  644.24   255.6  639.84   265.4  637.43
   275.2  636.81   294.9  636.91   304.7     638   314.5  640.32   334.2  646.15
     344   648.3   353.8  649.46   373.5  650.56   442.3  652.88   520.9  654.79
   540.6  656.38   550.4  657.72   560.3   659.7   570.1   662.5   579.9  664.62
#Mann= 3 , 0 , 0
       0      .1       0   255.6    .045       0   304.7     .08       0
Bank Sta=255.6,304.7
XS Rating Curve= 0 ,0
Exp/Cntr=0.3,0.1

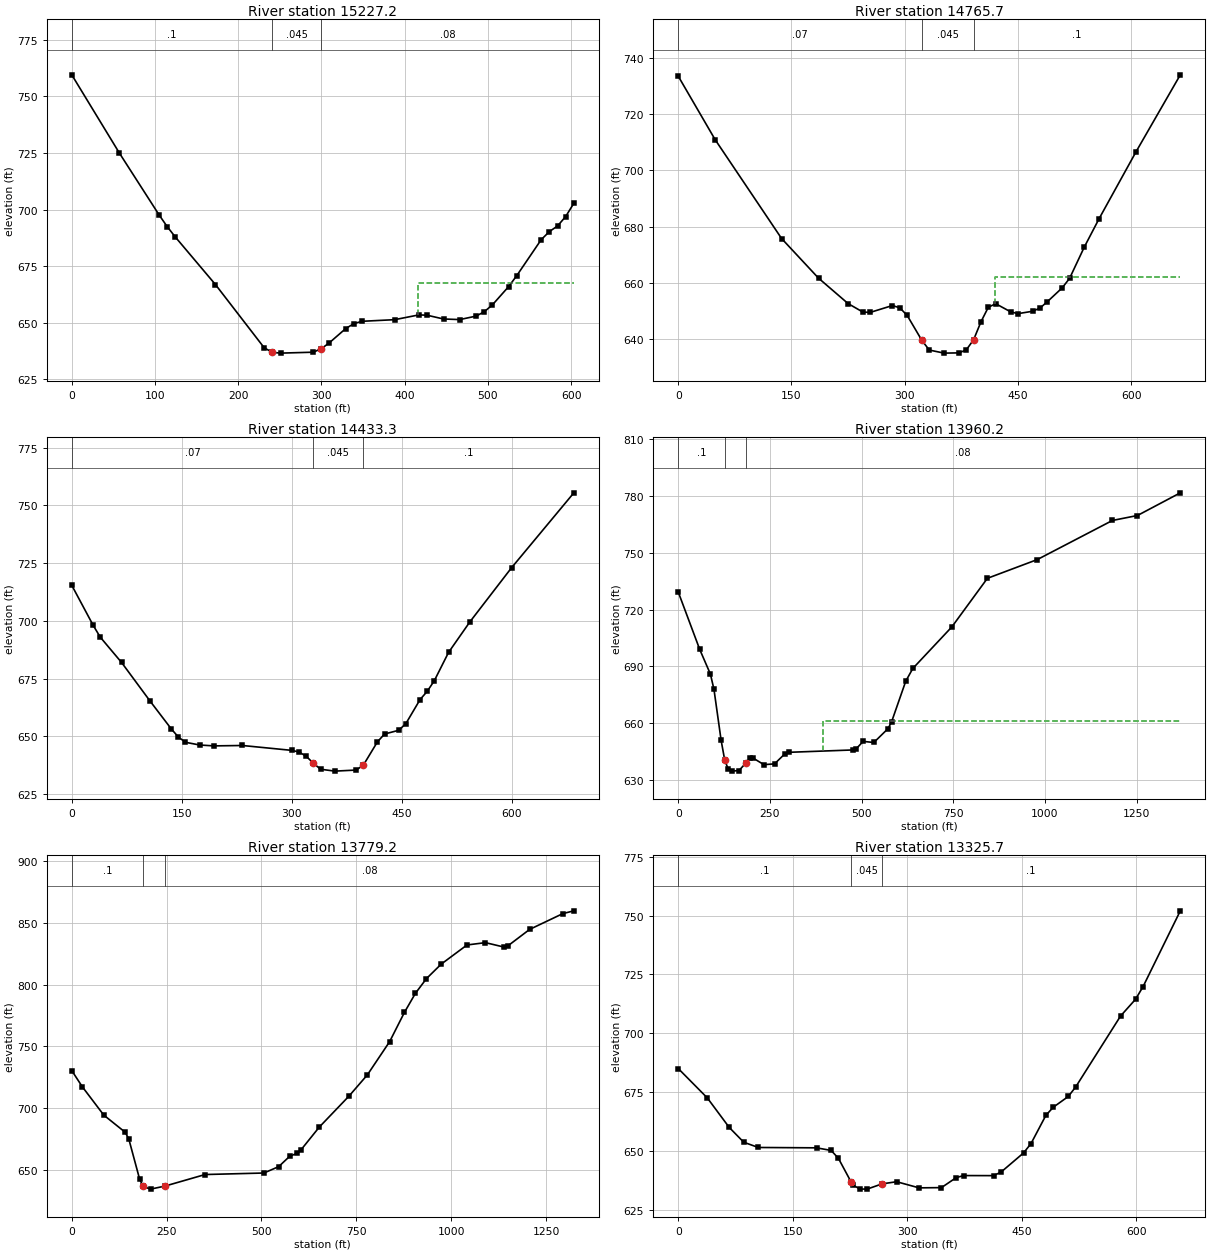
Type RM Length L Ch R = 1 ,15227.2 ,460,461.5,462.9
XS GIS Cut Line= 3
     1847640.565      513035.471     1847719.775      512916.114
     1847923.768      512503.787
#Sta/Elev= 30
       0  759.53    57.3  724.92     105  697.61   114.6  692.51   124.2  687.99
   172.6  666.91   231.3  638.93   241.1  636.94   250.9   636.6   290.1  637.01
   299.9  638.54   309.6   641.2   329.2  647.45     339  649.64   348.8  650.66
     388  651.38   417.3   653.5   427.1  653.33   446.7  651.68   466.2  651.42
   485.8  652.95   495.6  654.86   505.4   657.9     525  666.01   534.8  670.88
   564.1  686.73   573.9  690.29   583.7  692.76   593.5  696.95   603.3   702.8
#Mann= 3 , 0 , 0
       0      .1       0   241.1    .045       0   299.9     .08       0
#XS Ineff= 2 , 0
                          416.03          667.76
Permanent Ineff=
       F       F
Bank Sta=241.1,299.9
XS Rating Curve= 0 ,0
Exp/Cntr=0.3,0.1

Type RM Length L Ch R = 1 ,14765.7 ,327.1,332.3,337.6
XS GIS Cut Line= 2
     1848027.386       513281.46     1848359.678      512705.419
#Sta/Elev= 30
       0  733.57    48.9  710.97   136.9  675.79   185.8  661.69   224.9  652.65
   244.5  649.62   254.3   649.5   283.6  651.93   293.4  651.14   303.2  648.43
   322.7  639.53   332.5   636.1   352.1     635   371.6  635.09   381.4  636.12
   391.2  639.75     401  646.17   410.7  651.33   420.5  652.59   440.1  649.72
   449.9  649.05   469.4   649.9   479.2  651.05     489  653.33   508.5  658.22
   518.3  661.59   537.9  672.79   557.4  682.84   606.3  706.64     665  734.05
#Mann= 3 , 0 , 0
       0     .07       0   322.7    .045       0   391.2      .1       0
#XS Ineff= 2 , 0
                          419.87          662.27
Permanent Ineff=
       F       F
Bank Sta=322.7,391.2
XS Rating Curve= 0 ,0
Exp/Cntr=0.3,0.1

Type RM Length L Ch R = 1 ,14433.3 ,465.6,473.1,479.9
XS GIS Cut Line= 3
     1848247.119      513397.885     1848625.808      512995.324
     1848723.465      512906.348
#Sta/Elev= 30
       0   715.4    29.1  698.11    38.8  692.95    67.9  681.96   106.7  665.26
   135.8  653.13   145.4  649.63   155.1  647.36   174.5  646.18   193.9   645.8
   232.7  645.97   300.6  643.84   310.3  643.11     320  641.23   329.7  638.23
   339.4  635.68   358.8  634.86   387.8  635.32   397.6   637.4   416.9  647.55
   426.6  650.94     446  652.57   455.7  655.46   475.1   665.9   484.8  669.44
   494.5  674.06   513.9  686.31     543  699.55   599.9  723.04   684.8  755.48
#Mann= 3 , 0 , 0
       0     .07       0   329.7    .045       0   397.6      .1       0
Bank Sta=329.7,397.6
XS Rating Curve= 0 ,0
Exp/Cntr=0.3,0.1

Type RM Length L Ch R = 1 ,13960.2 ,173.1,180.9,188.7
XS GIS Cut Line= 5
     1848375.829      513557.236      1848555.69      513459.319
     1848666.295      513425.207     1849032.681      513052.467
     1849547.959      512945.523
#Sta/Elev= 30
       0  729.28    58.5  699.01    87.8   685.9    97.5  677.84     117  650.94
   126.8  640.54   136.5  635.72   146.3  634.73   165.8  635.05   185.3   639.2
     195  641.46   204.8  641.55   233.7  638.14   262.7  638.57   291.6     644
   301.2  644.66   475.4   645.9   485.1  646.46   504.4  650.43   533.5  649.84
   572.2  657.16   581.9  660.75   620.6  682.23   639.9  688.93   746.4  710.88
   843.2  736.49   979.6  746.41  1184.3  767.03  1252.5  769.64  1369.4  781.61
#Mann= 3 , 0 , 0
       0      .1       0   126.8    .045       0   185.3     .08       0
#XS Ineff= 2 , 0
                          394.87          661.27
Permanent Ineff=
       F       F
Bank Sta=126.8,185.3
XS Rating Curve= 0 ,0
Exp/Cntr=0.3,0.1

Type RM Length L Ch R = 1 ,13779.2 ,422.5,453.5,484
XS GIS Cut Line= 5
     1848379.128       513607.41     1848509.336      513660.535
      1848774.44      513619.389     1849233.468      513710.014
     1849673.746      513635.014
#Sta/Elev= 30
       0   730.5    28.1   717.3    84.4  694.53   140.6  680.71   150.2  675.35
     179  642.59   188.5  636.85   207.7   634.7     246  637.19   351.4   646.5
   506.4  647.72   545.4  652.88   574.6   661.3   594.1  663.64   603.9  666.33
   652.6   684.9   730.6  709.86   779.3  727.11   837.8  753.89   876.8  777.53
   905.9  793.01     935  804.89   973.9  816.59  1041.8  832.05  1090.4  833.92
  1138.9  830.38  1148.6   831.1  1206.9  844.63  1294.3  857.38  1323.4  859.64
#Mann= 3 , 0 , 0
       0      .1       0   188.5    .045       0     246     .08       0
Bank Sta=188.5,246
XS Rating Curve= 0 ,0
Exp/Cntr=0.3,0.1

Type RM Length L Ch R = 1 ,13325.7 ,505.4,506.2,507
XS GIS Cut Line= 3
     1848308.642      513762.965     1848414.892       514028.59
     1848527.392      514382.757
#Sta/Elev= 30
       0  685.12    38.1  672.65    66.8  660.14    85.8  653.87   104.9  651.64
   181.2  651.49   200.3  650.39   209.8  647.05   226.3637.1027   228.9  635.67
   238.4  633.98   247.9  634.04     267  636.21   286.1  637.12   315.4  634.52
   344.8  634.62   364.3   638.9   374.1  639.73   413.2   639.7     423  641.24
   452.3  649.31   462.1  653.28   481.7  665.32   491.4  668.73     511  673.28
   520.8  677.38   579.5  707.41     599  714.47   608.8  719.78   657.7  751.99
#Mann= 3 , 0 , 0
       0      .1       0   226.3    .045       0     267      .1       0
Bank Sta=226.3,267
XS Rating Curve= 0 ,0
Exp/Cntr=0.3,0.1