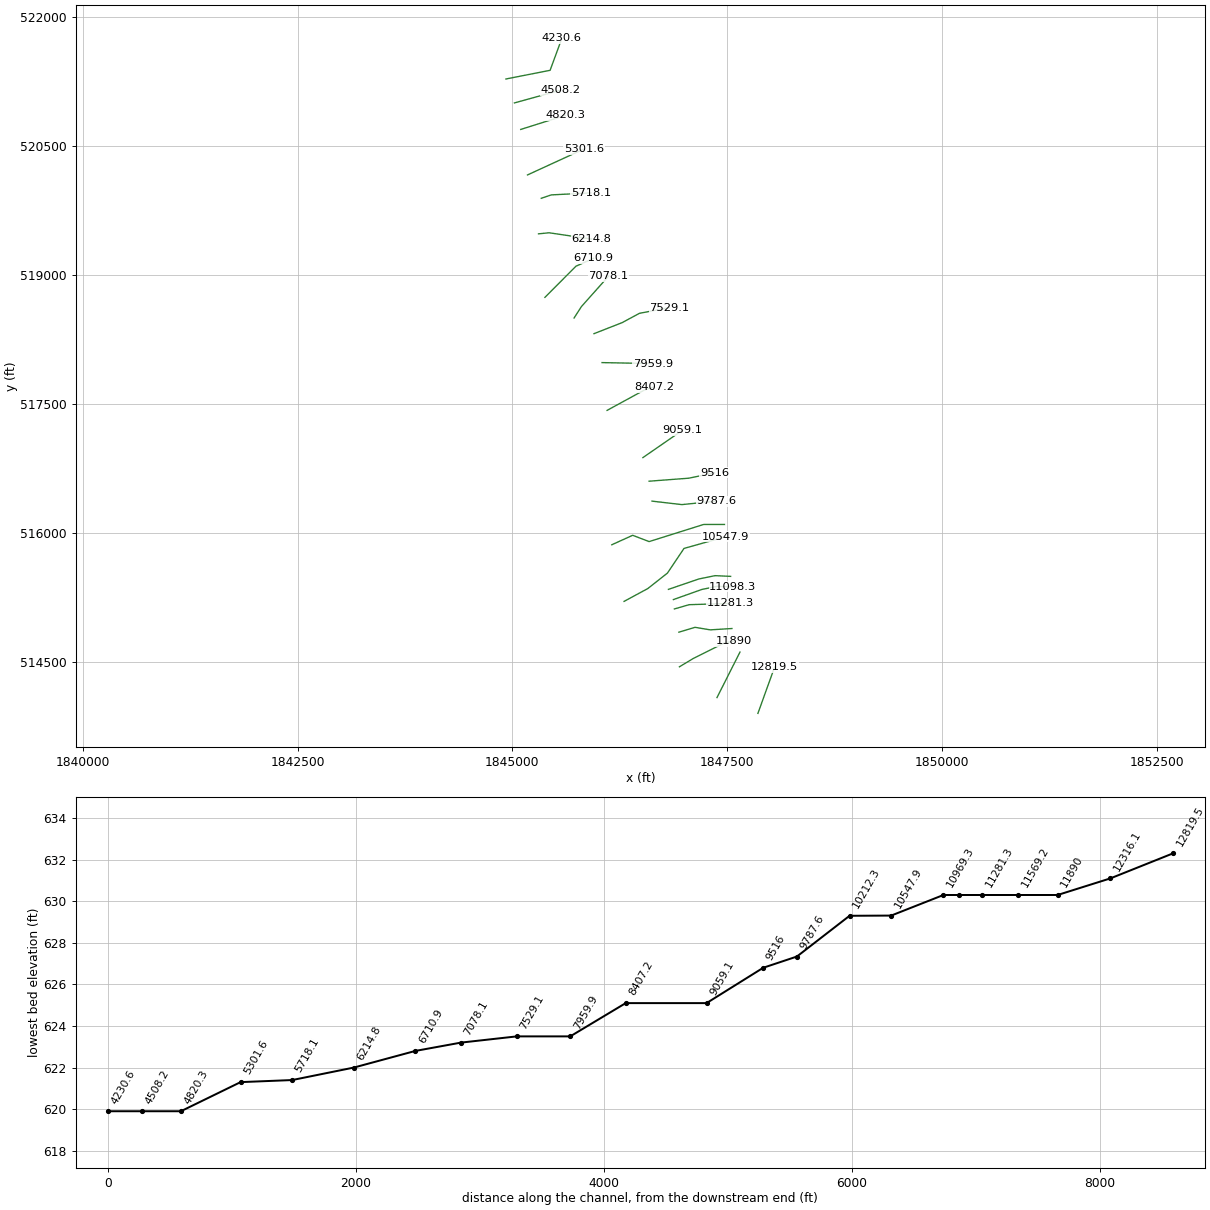
HEC-RAS study BLUECR.prj: BLUECR

--- BLUECR.g01 (geometry) --- (continued)

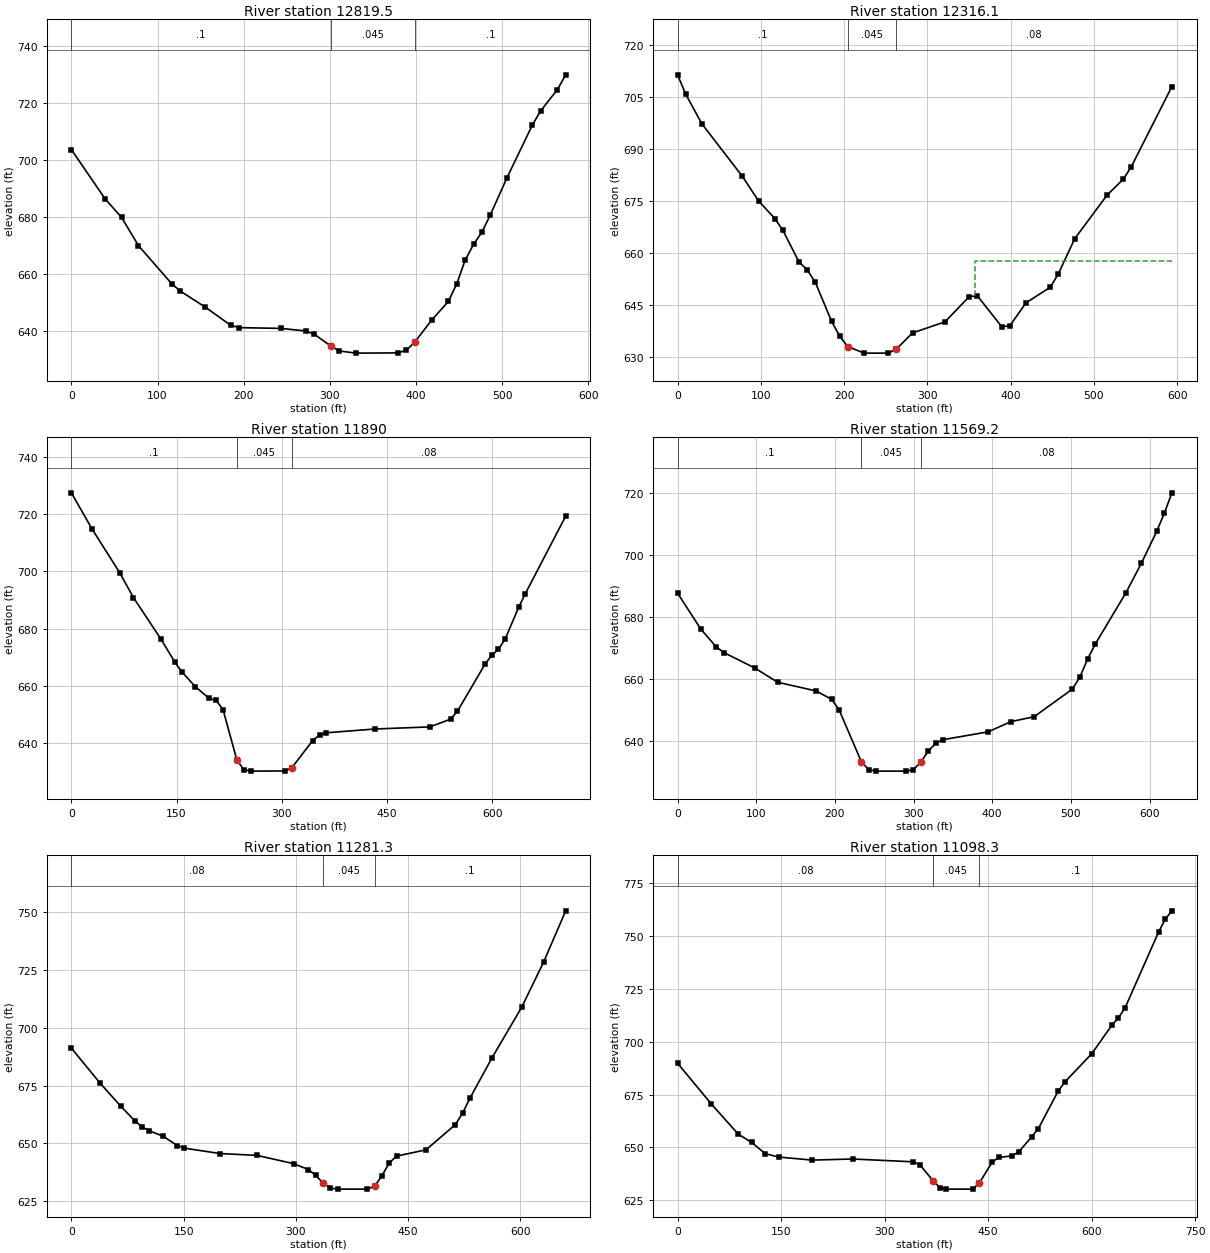
Type RM Length L Ch R = 1 ,12819.5 ,506.2,503.4,500
XS GIS Cut Line= 2
       1847857.6      513900.465     1848052.392      514440.048
#Sta/Elev= 30
       0  703.62    38.9  686.45    58.3  679.83    77.8  669.98   116.7  656.52
   126.4  654.04   155.6  648.37   184.7  642.09   194.5  641.23   243.1  640.97
   272.2  640.06     282  638.88   301.4  634.74   311.1  633.04   330.6   632.3
   379.2  632.38   388.9  633.37   398.6  636.18   418.1  643.87   437.5  650.39
   447.3  656.64     457  664.87   466.7  670.39   476.4  674.67   486.2  680.73
   505.6  693.79   534.8   712.1   544.5  717.14   563.9   724.6   573.7  729.81
#Mann= 3 , 0 , 0
       0      .1       0   301.4    .045       0   398.6      .1       0
Bank Sta=301.4,398.6
XS Rating Curve= 0 ,0
Exp/Cntr=0.3,0.1

Type RM Length L Ch R = 1 ,12316.1 ,440.3,426.1,412
XS GIS Cut Line= 2
     1847381.298      514084.077     1847649.147      514614.004
#Sta/Elev= 30
       0  711.32     9.7  705.76    29.2  697.19    77.9  682.03    97.3  674.96
   116.8   669.9   126.5  666.48     146  657.31   155.7  655.13   165.5  651.47
     185  640.26   194.7  635.97   204.4  633.01   223.9   631.1   253.1   631.1
   262.8  632.28   282.3  636.93   321.2  640.12   350.4  647.41   360.2  647.58
   389.4  638.71   399.1  638.99   418.6  645.62   447.8   650.1   457.5  654.02
     477  664.06   515.9  676.65   535.4  681.24   545.1  684.87   593.8  707.95
#Mann= 3 , 0 , 0
       0      .1       0   204.4    .045       0   262.8     .08       0
#XS Ineff= 2 , 0
                          357.14          657.71
Permanent Ineff=
       F       F
Bank Sta=204.4,262.8
XS Rating Curve= 0 ,0
Exp/Cntr=0.3,0.1

Type RM Length L Ch R = 1 ,11890   ,334.8,320.8,306.5
XS GIS Cut Line= 4
     1846944.059      514442.132     1847104.228      514538.185
     1847464.892      514718.173     1847577.392      514742.132
#Sta/Elev= 30
       0  727.38    29.5  714.74    68.8  699.57    88.5  690.84   127.8  676.32
   147.4  668.36   157.3  665.01   176.9  659.72   196.6  655.65   206.4  654.96
   216.3  651.74   235.9  634.22   245.8  630.79   255.6   630.3   304.7  630.36
   314.6  631.55   344.1  640.97   353.9  642.92   363.7  643.68   432.5  644.99
   511.2  645.73   540.7  648.43   550.5  651.19   589.8   667.6   599.4  670.69
     609  672.83   618.6   676.4   637.8  687.43   647.4  692.26   704.9  719.26
#Mann= 3 , 0 , 0
       0      .1       0   235.9    .045       0   314.6     .08       0
Bank Sta=235.9,314.6
XS Rating Curve= 0 ,0
Exp/Cntr=0.3,0.1

Type RM Length L Ch R = 1 ,11569.2 ,283.5,287.9,292.4
XS GIS Cut Line= 4
     1846938.156       514844.91     1847125.656      514901.333
     1847302.739      514871.819     1847555.343      514887.444
#Sta/Elev= 30
       0  687.68    29.4  676.15      49  670.39    58.7  668.54    97.9  663.59
   127.3  658.95   176.2  656.15   195.8  653.45   205.2  650.14   233.6  633.33
     243  630.75   252.5   630.3   290.3   630.3   299.7  630.76   309.2   633.2
   318.6  636.74   328.1  639.24   337.5  640.44   394.8  642.97     424  646.28
   453.2  647.84   501.9  656.75   511.6  660.76   521.3  666.48   531.1  671.32
     570  687.85   589.5  697.29     609  707.58   618.7  713.43   628.4  720.04
#Mann= 3 , 0 , 0
       0      .1       0   233.6    .045       0   309.2     .08       0
Bank Sta=233.6,309.2
XS Rating Curve= 0 ,0
Exp/Cntr=0.3,0.1

Type RM Length L Ch R = 1 ,11281.3 ,178.6,182.9,186.6
XS GIS Cut Line= 3
     1846885.208      515114.893     1847057.457      515164.595
     1847538.846      515179.092
#Sta/Elev= 30
       0  691.14    37.7  676.29      66  666.07    84.9  659.74    94.4  657.18
   103.8  655.52   122.7  653.12   141.5  649.11     151  647.99   198.9  645.65
   248.1  644.86   297.2  641.29   316.9  638.73   326.7  636.23   336.5  632.92
   346.4  630.75   356.2   630.3   395.5   630.3   405.3  631.53   415.2  636.07
     425  641.61   434.8  644.55   474.1  647.26   513.4  658.16   523.3  663.28
   533.1  669.69   562.6  687.09   601.9   708.7   631.4  728.32   660.9  750.39
#Mann= 3 , 0 , 0
       0     .08       0   336.5    .045       0   405.3      .1       0
Bank Sta=336.5,405.3
XS Rating Curve= 0 ,0
Exp/Cntr=0.3,0.1

Type RM Length L Ch R = 1 ,11098.3 ,129.5,129.1,129.3
XS GIS Cut Line= 4
     1846874.003      515223.925     1847205.114      515341.703
     1847382.312      515378.266     1847566.201      515371.625
#Sta/Elev= 30
       0  689.82    48.8  670.61    87.9  656.31   107.4  652.38   126.9  647.09
   146.4  645.47   195.2  644.03   253.8  644.55   341.7  643.22   351.4   641.7
   370.5  634.19     380  631.04   389.5   630.3   427.6   630.3   437.1  633.09
   456.2   643.2   465.7  645.27   484.8  646.06   494.3  647.87   513.3   655.1
   522.8  658.93   551.7  676.76   561.4  681.05   600.2  694.35   629.2  707.77
   638.9  711.34   648.6  716.12     697  751.86   706.7  757.97   716.4  761.95
#Mann= 3 , 0 , 0
       0     .08       0   370.5    .045       0   437.1      .1       0
Bank Sta=370.5,437.1
XS Rating Curve= 0 ,0
Exp/Cntr=0.3,0.1

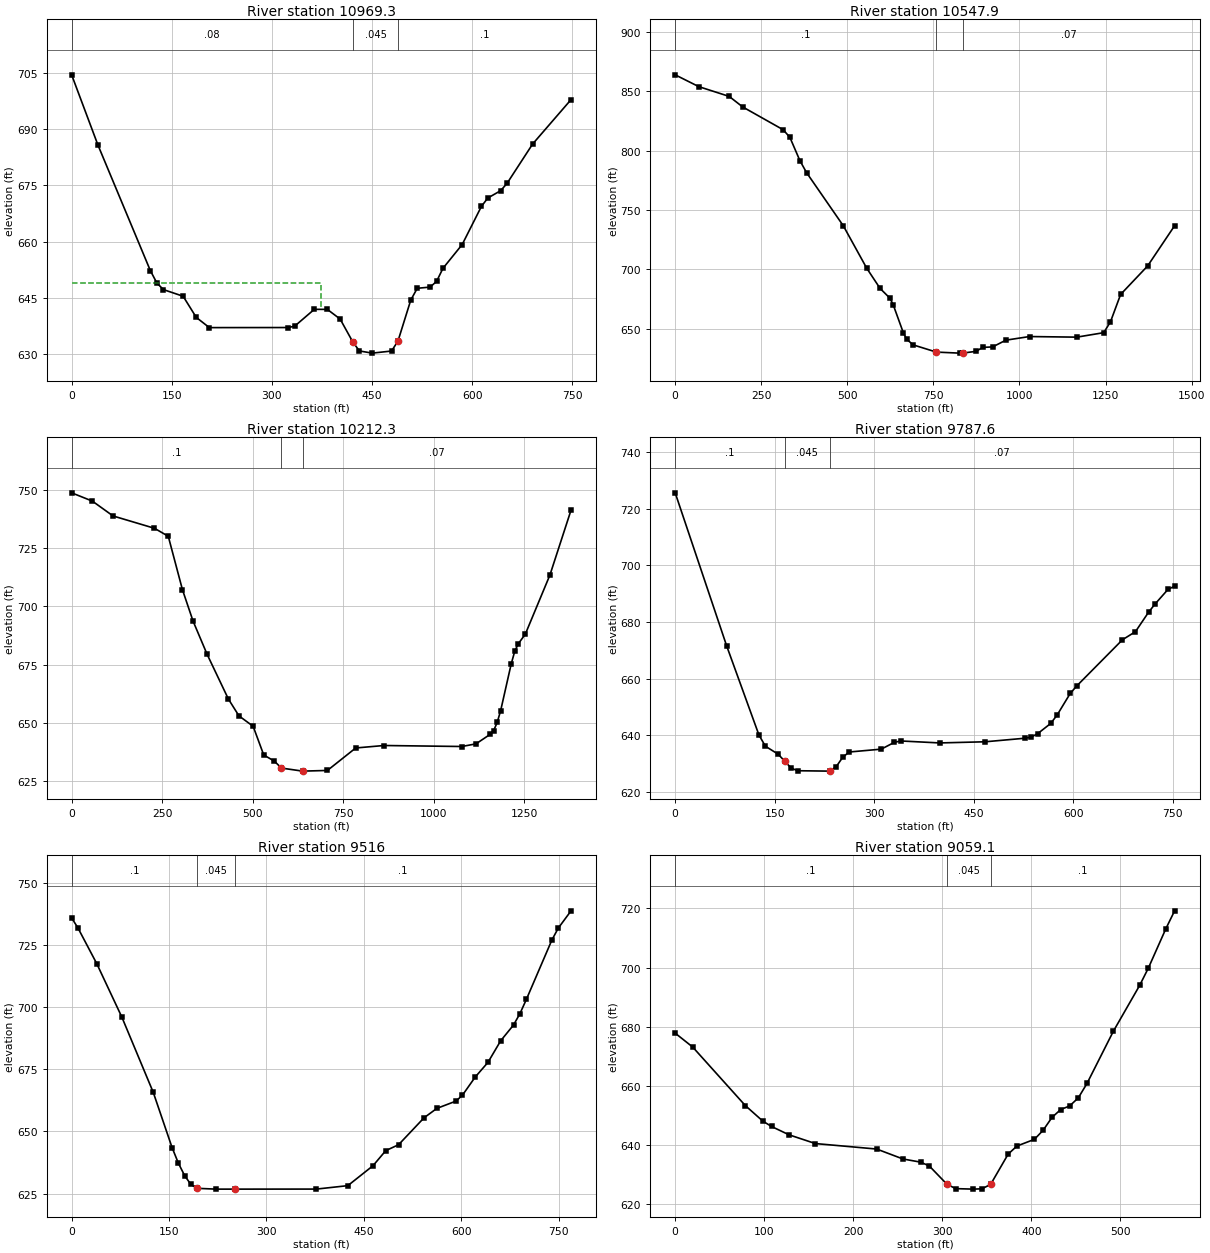
Type RM Length L Ch R = 1 ,10969.3 ,404.2,421.4,439.2
XS GIS Cut Line= 4
     1846816.242      515342.745     1847169.576        515463.3
     1847358.062      515502.193     1847540.159      515494.021
#Sta/Elev= 30
       0  704.47    39.3   685.8   117.9  652.29   127.7  648.98   137.5  647.23
     167  645.46   186.7  639.82   206.3   637.1   324.2  637.12     334  637.47
   363.5  641.97     383  641.96   402.2  639.38   421.4   633.2   431.1  630.88
   450.3   630.3   479.2  630.86   488.8   633.5     508  644.44   517.7  647.58
   536.9   647.9   546.6   649.4   556.2   652.9     585  659.24   613.8   669.4
   623.4  671.64   642.5  673.58   652.1  675.51   690.5  686.02   748.1  697.87
#Mann= 3 , 0 , 0
       0     .08       0   421.4    .045       0   488.8      .1       0
#XS Ineff= 2 , 0
          373.94  648.93
Permanent Ineff=
       F       F
Bank Sta=421.4,488.8
XS Rating Curve= 0 ,0
Exp/Cntr=0.3,0.1

Type RM Length L Ch R = 1 ,10547.9 ,350.3,335.6,319.8
XS GIS Cut Line= 5
     1846299.614      515202.896     1846575.656      515351.854
     1846804.545      515531.923      1846997.56       515818.88
     1847478.781      515953.937
#Sta/Elev= 30
       0  863.95    68.6  853.99   156.8  845.76     196  836.89   313.7  817.64
   333.1  811.25   362.2  791.61   381.6  781.47   488.4  736.62   556.4  700.85
   595.2  683.83   624.1  675.51   633.7  669.68   662.5  646.57   672.1  641.04
   691.4  636.24   758.6  630.18   825.8  629.31   835.4  629.36   873.9  630.82
   893.1  634.14   921.9  634.55   960.5  640.24  1029.1  643.29  1166.3  642.78
  1244.7  646.56  1264.3  655.78  1293.7   678.8  1372.1  702.79  1450.5  736.73
#Mann= 3 , 0 , 0
       0      .1       0   758.6    .045       0   835.4     .07       0
Bank Sta=758.6,835.4
XS Rating Curve= 0 ,0
Exp/Cntr=0.3,0.1

Type RM Length L Ch R = 1 ,10212.3 ,434.1,424.7,415.1
XS GIS Cut Line= 5
     1846156.906      515861.333     1846399.961      515971.576
     1846591.577      515898.347     1847225.482      516097.444
     1847468.538      516097.444
#Sta/Elev= 30
       0  748.66    57.2  745.11   114.4  738.74   228.8  733.45   266.9  730.03
     306  707.15   335.3  693.68   374.3  679.36     433  660.21   462.2  652.99
   501.3  648.54   530.6  636.23     560  633.57   579.5  630.61   638.1   629.3
   706.5  629.59   784.7  639.23   862.9  640.29  1077.8  639.86  1116.9     641
  1155.9  645.06  1165.6  646.68  1175.4  650.16  1185.1   655.3  1214.2  675.31
    1224  680.72  1233.7  683.92  1253.1  688.03  1321.2  713.45  1379.5  741.28
#Mann= 3 , 0 , 0
       0      .1       0   579.5    .045       0   638.1     .07       0
Bank Sta=579.5,638.1
XS Rating Curve= 0 ,0
Exp/Cntr=0.3,0.1

Type RM Length L Ch R = 1 ,9787.6  ,267.3,271.6,275.9
XS GIS Cut Line= 3
     1846625.332      516368.926      1846972.38      516328.613
      1847373.63      516368.856
#Sta/Elev= 30
       0  725.66    77.6  671.56   126.2  640.11   135.9  636.15   155.3   633.3
     165  630.86   174.7  628.43   184.4  627.48   232.9  627.34   242.6   628.9
   252.3  632.17     262  634.09   310.6  635.11     330  637.48   339.7     638
   398.6   637.3   467.4  637.71   526.4  638.95   536.3  639.36   546.1  640.55
   565.8  644.17   575.6  647.17   595.3  654.79   605.1  657.43     674  673.75
   693.6  676.61   713.3  683.46   723.1  686.37   742.8  691.59   752.6  692.65
#Mann= 3 , 0 , 0
       0      .1       0     165    .045       0   232.9     .07       0
Bank Sta=165,232.9
XS Rating Curve= 0 ,0
Exp/Cntr=0.3,0.1

Type RM Length L Ch R = 1 ,9516    ,444.8,456.9,468.8
XS GIS Cut Line= 3
     1846591.373      516600.697     1847054.133      516635.882
     1847352.744      516698.382
#Sta/Elev= 30
       0  735.89     9.7  731.85    38.7  717.48    77.4  695.95   125.7  665.72
   154.7  643.51   164.4  637.24     174  632.25   183.7  628.67   193.4  627.12
   222.4   626.8   251.4   626.8   377.1  626.82   425.4   628.2   464.1   636.2
   483.8  642.28   503.5  644.65   542.8   655.5   562.5  659.27     592  662.21
   601.9  664.58   621.6  671.88   641.2  677.78   660.9   686.5   680.6  692.81
   690.4  697.35   700.3  703.07   739.6  726.96   749.5  731.78   769.2  738.73
#Mann= 3 , 0 , 0
       0      .1       0   193.4    .045       0   251.4      .1       0
Bank Sta=193.4,251.4
XS Rating Curve= 0 ,0
Exp/Cntr=0.3,0.1

Type RM Length L Ch R = 1 ,9059.1  ,654.2,651.9,649.5
XS GIS Cut Line= 2
     1846519.192      516875.297     1846980.651      517194.047
#Sta/Elev= 30
       0  677.84    19.7  673.13    78.7  653.37    98.4   648.1   108.2  646.28
   127.9  643.46   157.4  640.51   226.3  638.65   255.8  635.29   275.5  634.23
   285.3  632.94     305   626.8   314.9  625.27   334.5   625.1   344.4  625.21
   354.2  626.69   373.9  636.94   383.7  639.66   403.4  641.94   413.2  645.02
   423.1  649.34   432.9  652.02   442.8   653.2   452.6  655.93   462.4  660.82
     492  678.47   521.5  693.96   531.3  699.83     551  713.17   560.8   719.2
#Mann= 3 , 0 , 0
       0      .1       0     305    .045       0   354.2      .1       0
Bank Sta=305,354.2
XS Rating Curve= 0 ,0
Exp/Cntr=0.3,0.1

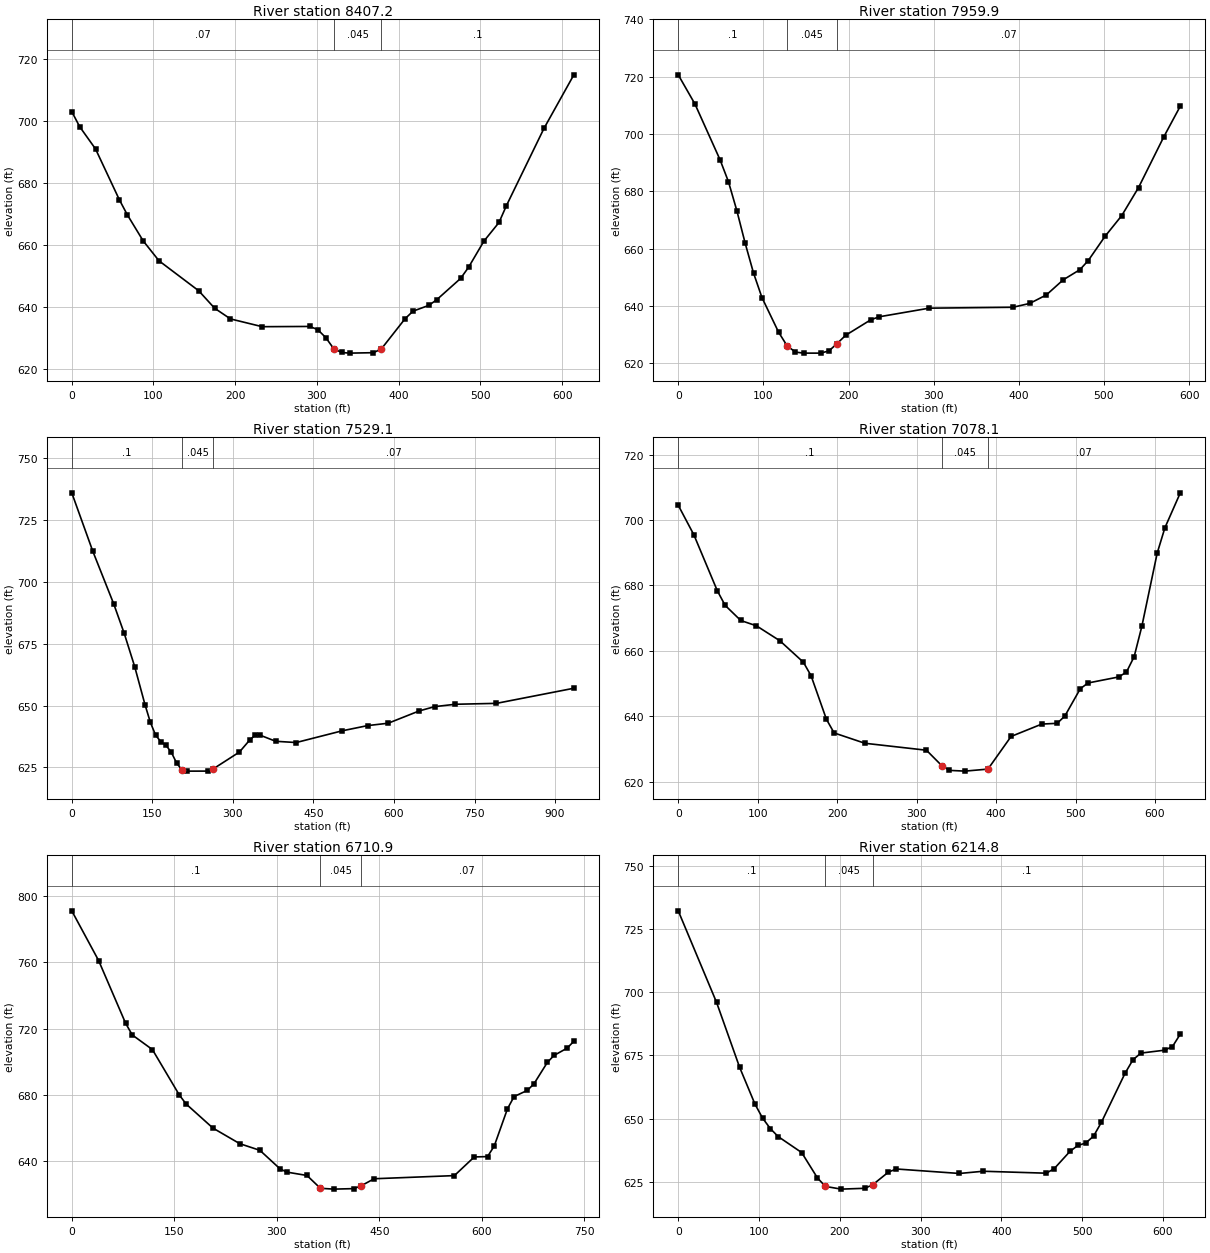
Type RM Length L Ch R = 1 ,8407.2  ,459,447.3,435.6
XS GIS Cut Line= 3
     1846102.178      517424.429     1846537.074      517661.409
     1846650.789      517696.999
#Sta/Elev= 30
       0  703.04     9.7  698.16    29.1  690.98    58.3  674.56      68  669.73
    87.4  661.32   106.8  654.88   155.4  645.21   174.8  639.59   194.2  636.14
   233.1  633.63   291.3  633.71     301  632.68   310.8  630.12   320.5  626.55
   330.2  625.31   339.9   625.1     369  625.24   378.7  626.41   407.9  636.21
   417.6  638.64     437  640.52   446.7  642.35   475.8   649.2   485.6  652.82
   504.4  661.26   522.8  667.26   531.9   672.7   577.8   697.6   614.4  714.91
#Mann= 3 , 0 , 0
       0     .07       0   320.5    .045       0   378.7      .1       0
Bank Sta=320.5,378.7
XS Rating Curve= 0 ,0
Exp/Cntr=0.3,0.1

Type RM Length L Ch R = 1 ,7959.9  ,421.8,430.8,439.6
XS GIS Cut Line= 2
     1846043.498      517980.159     1846633.081        517968.7
#Sta/Elev= 30
       0  720.66    19.7  710.43    49.1  691.01      59  683.34    68.8  673.27
    78.6  661.89    88.4  651.49    98.3  642.92   117.9  630.79   127.8  626.08
   137.6  623.86   147.4   623.5   167.1   623.5   176.9  624.26   186.7  626.86
   196.6  629.72     226  635.11   235.9  636.18   294.8   639.2   393.1  639.51
   412.8  640.85   432.4  643.82   452.1  649.08   471.8  652.64   481.6  655.83
   501.2  664.24   520.9  671.51   540.6  681.29     570  698.83   589.7  709.74
#Mann= 3 , 0 , 0
       0      .1       0   127.8    .045       0   186.7     .07       0
Bank Sta=127.8,186.7
XS Rating Curve= 0 ,0
Exp/Cntr=0.3,0.1

Type RM Length L Ch R = 1 ,7529.1  ,440.4,451,461.6
XS GIS Cut Line= 4
      1845950.27      518316.745     1846277.353       518444.87
     1846478.394      518553.075     1846827.352      518619.742
#Sta/Elev= 30
       0  736.02      39  712.49    78.1  691.12    97.6  679.24   117.1   665.8
   136.6  650.18   146.4   643.2   156.1  638.05   165.9  635.39   175.6   633.9
   185.4  631.09   195.2   626.8   204.9  624.02   214.7   623.5   253.7  623.51
   263.5  624.42   312.2  631.22   331.8  636.19   341.5  638.01   351.3  637.98
   379.8  635.56   417.9  635.06   503.5   639.8     551  641.91   589.2  642.87
   646.8  647.83   675.6  649.57     714  650.53   790.8   650.9   934.9  657.01
#Mann= 3 , 0 , 0
       0      .1       0   204.9    .045       0   263.5     .07       0
Bank Sta=204.9,263.5
XS Rating Curve= 0 ,0
Exp/Cntr=0.3,0.1

Type RM Length L Ch R = 1 ,7078.1  ,368.5,367.2,365.9
XS GIS Cut Line= 3
     1845717.977      518498.909     1845803.394        518631.2
     1846119.019      518985.367
#Sta/Elev= 30
       0   704.5    19.7  695.45    49.2  678.34      59   673.9    78.7  669.26
    98.4  667.64     128  663.05   157.5   656.5   167.2  652.36   186.5  639.05
   196.2  634.88   234.9  631.72   312.4  629.59   331.7  624.87   341.4  623.43
   360.8   623.2   389.8  623.82   418.9   633.8   457.6  637.59     477  637.82
   486.6  640.06     506  648.39   515.7  650.15   554.4     652   564.1  653.49
   573.8   658.2   583.5   667.5   602.8  689.86   612.5  697.61   631.9   708.3
#Mann= 3 , 0 , 0
       0      .1       0   331.7    .045       0   389.8     .07       0
Bank Sta=331.7,389.8
XS Rating Curve= 0 ,0
Exp/Cntr=0.3,0.1

Type RM Length L Ch R = 1 ,6710.9  ,517.1,496.1,475
XS GIS Cut Line= 3
     1845378.972      518739.244     1845740.083      519101.223
     1845944.077      519192.369
#Sta/Elev= 30
       0  791.21    39.3  761.12    78.7  723.25    88.5  716.11     118  707.25
   157.3  679.82   167.2  674.37   206.5  659.76   245.8  650.31   275.3  646.28
   304.8  635.06   314.6  633.11   344.2  631.06   363.8  623.31   383.5   622.8
     413  623.11   422.8  624.68   442.5  629.08   559.9  630.98     589  642.28
   608.4  642.49   618.2  648.88   637.6  671.45   647.3  678.84   666.7  682.55
   676.4  686.57   695.9  699.46   705.6  703.68     725  708.15   734.7  712.29
#Mann= 3 , 0 , 0
       0      .1       0   363.8    .045       0   422.8     .07       0
Bank Sta=363.8,422.8
XS Rating Curve= 0 ,0
Exp/Cntr=0.3,0.1

Type RM Length L Ch R = 1 ,6214.8  ,492.2,496.7,501.1
XS GIS Cut Line= 3
     1845304.146      519477.612     1845427.063      519490.112
     1845919.771      519417.196
#Sta/Elev= 30
       0  732.37    47.5  696.02      76  670.31      95  655.71   104.5  650.13
     114  646.02   123.6  642.87   152.8  636.51   172.4  626.42   182.2  623.08
   201.7     622     231  622.33   240.7  623.72   260.3  628.77     270  629.99
   348.2  628.21   377.5  629.09   455.6  628.32   465.4  630.09   484.9  636.94
   494.7  639.31   504.4  640.27   514.2  643.01     524  648.56   553.3  668.02
     563  673.31   572.8  675.95   602.1   677.1   611.9  678.54   621.6  683.48
#Mann= 3 , 0 , 0
       0      .1       0   182.2    .045       0   240.7      .1       0
Bank Sta=182.2,240.7
XS Rating Curve= 0 ,0
Exp/Cntr=0.3,0.1

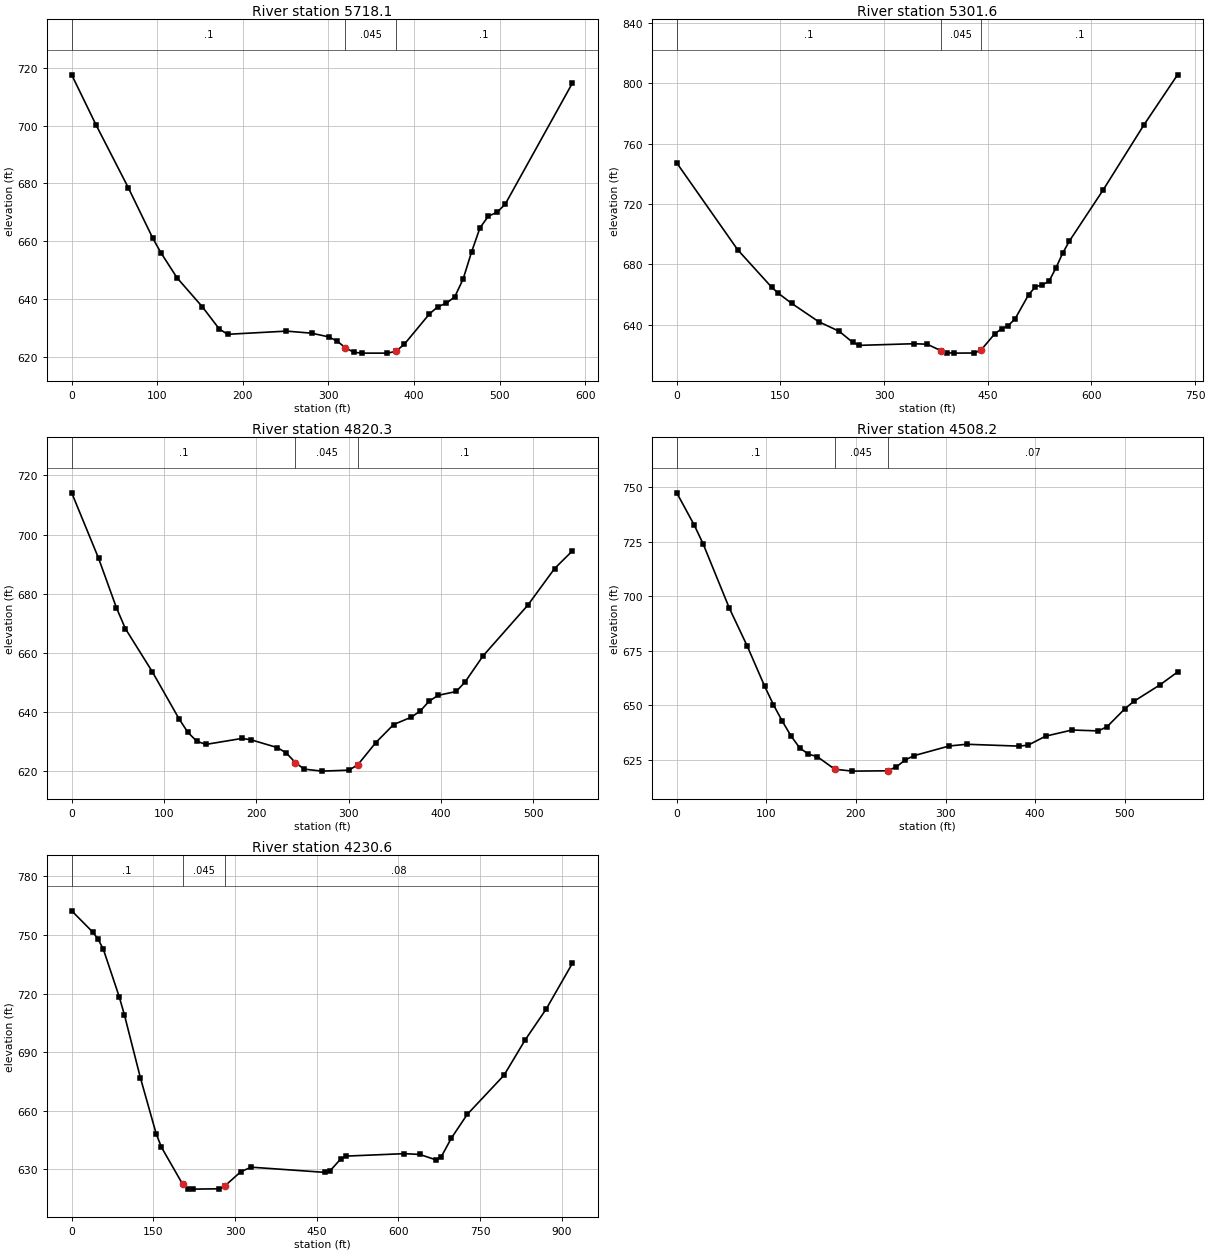
Type RM Length L Ch R = 1 ,5718.1  ,407.8,416.4,425
XS GIS Cut Line= 3
     1845336.438      519891.154     1845453.104      519930.737
     1845914.563      519953.654
#Sta/Elev= 30
       0   717.5    28.4  700.23    66.3  678.42    94.8  661.05   104.2  656.09
   123.2  647.36   152.7  637.38   172.4  629.75   182.2   627.9     251     629
   280.5  628.28   300.2  627.02     310  625.59   319.8  623.27   329.6  621.68
   339.5   621.4     369   621.4   378.8  622.02   388.6  624.44   418.1  634.95
   427.9  637.43   437.8  638.64   447.6  640.82   457.4  646.98   467.3  656.36
   477.1  664.67   486.9  668.71   496.8  669.98   506.6  672.83   585.2   714.7
#Mann= 3 , 0 , 0
       0      .1       0   319.8    .045       0   378.8      .1       0
Bank Sta=319.8,378.8
XS Rating Curve= 0 ,0
Exp/Cntr=0.3,0.1

Type RM Length L Ch R = 1 ,5301.6  ,484.1,481.3,478.4
XS GIS Cut Line= 2
     1845175.717      520162.616     1845834.267        520464.9
#Sta/Elev= 30
       0  747.21    88.1  689.75   137.1  665.04   146.9  660.93   166.5  654.16
   205.6  642.04     235  635.77   254.6  628.43   264.4  626.44   342.7  627.52
   362.3  627.21   381.9     623   391.7  621.51   401.5   621.3   430.8  621.39
   440.6  623.48   460.2  634.17     470  637.35   479.8  639.52   489.6  644.05
   509.2  660.01     519  665.19   528.8  666.47   538.6  668.89   548.4  677.43
   558.2  687.27   567.9  695.32   616.9  729.25   675.6  772.11   724.6  805.51
#Mann= 3 , 0 , 0
       0      .1       0   381.9    .045       0   440.6      .1       0
Bank Sta=381.9,440.6
XS Rating Curve= 0 ,0
Exp/Cntr=0.3,0.1

Type RM Length L Ch R = 1 ,4820.3  ,312.7,312.1,311.1
XS GIS Cut Line= 2
      1845097.39      520691.902     1845614.751      520855.096
#Sta/Elev= 30
       0  714.11    29.1  691.96    48.4  675.25    58.1  668.16    87.2   653.6
   116.2  637.65   125.9  632.98   135.6  630.01   145.3  628.94   184.1  630.95
   193.8  630.55   222.8  627.86   232.5  626.04   242.2  622.81   251.9  620.57
   271.2   619.9   300.3  620.23     310  622.06   329.4  629.55   348.7  635.66
   368.1  638.19   377.8  640.34   387.5  643.66   397.2  645.57   416.6  646.86
   426.2  650.11   445.6   658.9     494  676.04   523.1  688.47   542.5  694.49
#Mann= 3 , 0 , 0
       0      .1       0   242.2    .045       0     310      .1       0
Bank Sta=242.2,310
XS Rating Curve= 0 ,0
Exp/Cntr=0.3,0.1

Type RM Length L Ch R = 1 ,4508.2  ,279.4,277.6,275.9
XS GIS Cut Line= 2
     1845023.953      521000.235     1845562.494      521149.194
#Sta/Elev= 30
       0  747.43    19.6  732.58    29.4  724.08    58.8  694.45    78.4  677.43
      98  658.89   107.8  650.39   117.6  642.91   127.4  636.08   137.2  630.54
     147  627.66   156.8  626.54   176.4  620.75   196.1   619.9   235.3  620.05
   245.1  621.88   254.9     625   264.7  626.98   303.9  631.41   323.5  632.21
   382.3  631.35   392.1  631.81   411.7  635.93   441.1  638.74   470.5  638.33
   480.3   640.3     500  648.45   509.8  651.81   539.2  659.43   558.8   665.3
#Mann= 3 , 0 , 0
       0      .1       0   176.4    .045       0   235.3     .07       0
Bank Sta=176.4,235.3
XS Rating Curve= 0 ,0
Exp/Cntr=0.3,0.1

Type RM Length L Ch R = 1 ,4230.6  ,434.6,454.3,473.7
XS GIS Cut Line= 3
      1844925.69      521278.826      1845439.14      521379.596
     1845575.899      521751.487
#Sta/Elev= 30
       0  762.35    38.8  751.42    48.4  747.88    58.1  742.66    87.2  718.42
    96.9  708.95     126  677.03     155  648.33   164.7  641.37   203.5  622.52
   213.2  620.22   222.9   619.9   271.3  620.07     281  621.47   310.1  628.73
   329.4  631.14   465.1  628.47   474.8   629.4   494.2  635.42   503.9   636.8
   610.2  638.05   639.2  637.66   668.2  634.93   677.9  636.13   697.2  646.04
   726.2  658.14   793.8   678.2   832.5  696.22   871.2  712.07   919.5  735.55
#Mann= 3 , 0 , 0
       0      .1       0   203.5    .045       0     281     .08       0
Bank Sta=203.5,281
XS Rating Curve= 0 ,0
Exp/Cntr=0.3,0.1