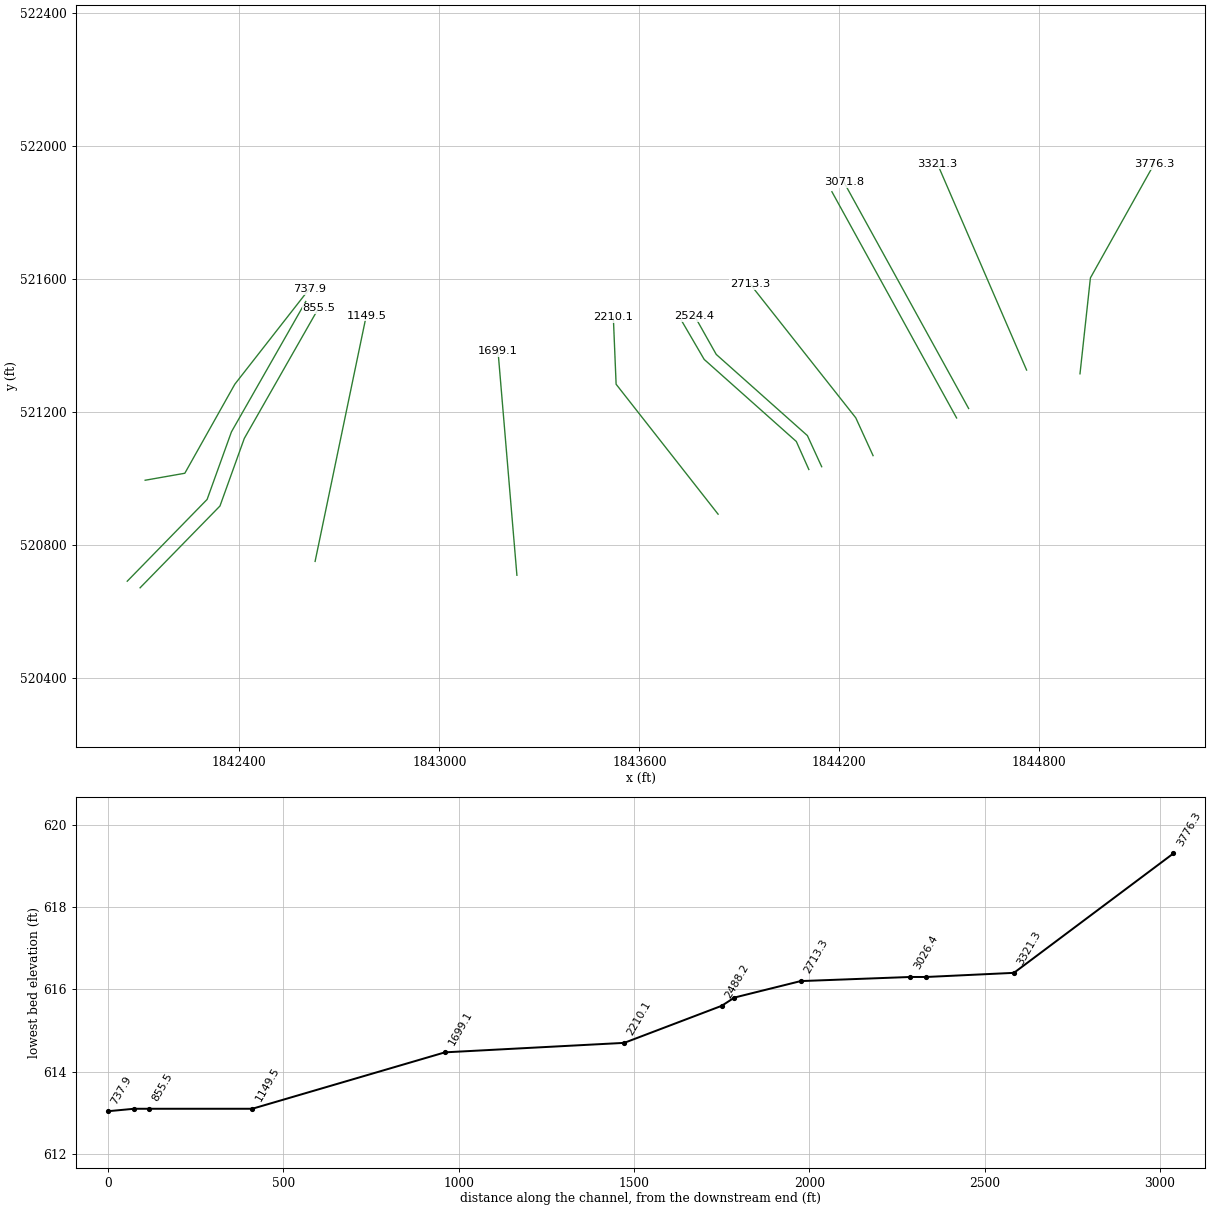
HEC-RAS study BLUECR.prj: BLUECR

--- BLUECR.g01 (geometry) --- (continued)

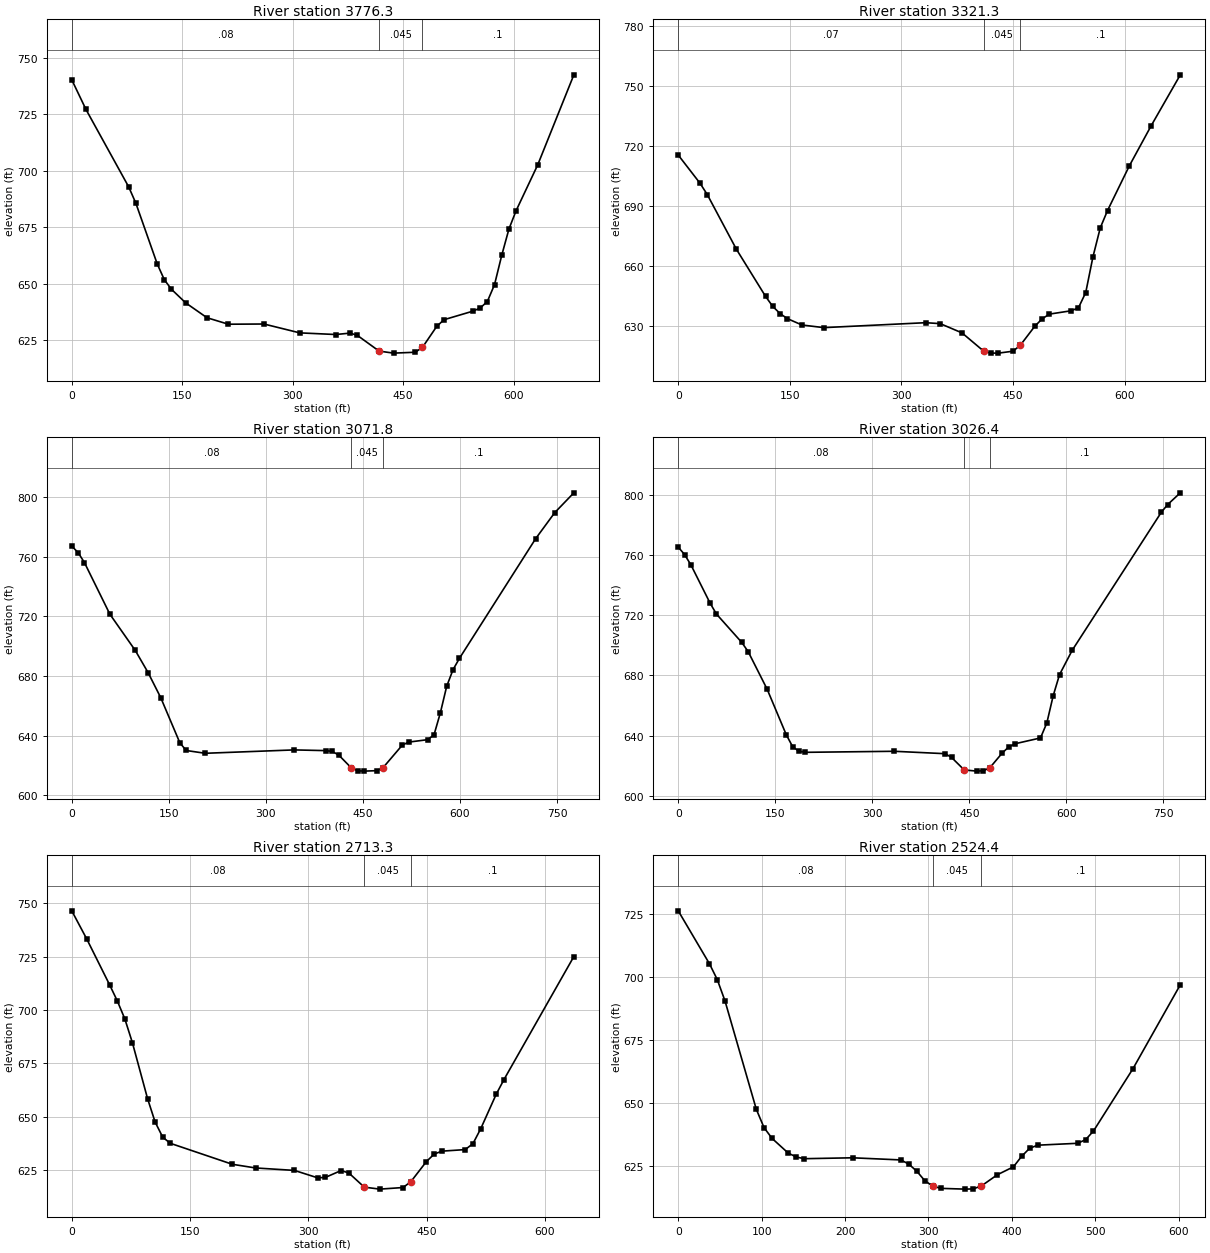
Type RM Length L Ch R = 1 ,3776.3  ,434.1,454.9,475.5
XS GIS Cut Line= 3
     1844921.728      521314.862     1844952.978      521603.056
      1845143.95       521945.07
#Sta/Elev= 30
       0  740.21    19.3  727.07    77.3  692.82      87  685.61     116  658.76
   125.6  651.81   135.3  647.54   154.6  641.55   183.6  634.95   212.6  632.09
   260.9  632.18   309.5  628.26   358.4  627.53     378  628.16   387.8  627.13
   417.2   620.2   436.8   619.3   466.2  619.69     476  621.81   495.5  631.14
   505.3  634.08   544.5  637.86   554.3  639.23   564.1  642.09   573.9  649.57
   583.7  662.57   593.5  674.22   603.3  682.38   632.6   702.6   681.6   742.4
#Mann= 3 , 0 , 0
       0     .08       0   417.2    .045       0     476      .1       0
Bank Sta=417.2,476
XS Rating Curve= 0 ,0
Exp/Cntr=0.3,0.1

Type RM Length L Ch R = 1 ,3321.3  ,247.4,249.5,251.7
XS GIS Cut Line= 2
     1844761.508      521326.084       1844494.1      521945.653
#Sta/Elev= 30
       0  715.53    29.3  701.41    39.1  695.71    78.2  668.37   117.4  644.78
   127.1  639.75   136.9  636.19   146.7  633.66   166.3  630.48   195.6  629.16
   332.5  631.63   352.1  631.16   381.4  626.53   410.8  617.31   420.5  616.41
   430.3   616.4   449.9  617.36   459.7  620.31   479.2  629.84     489  633.53
   498.8  635.92   528.1   637.6   537.9  639.08   547.7  646.74   557.4  664.61
   567.2  679.08     577  687.78   606.4   710.2   635.7  730.25   674.8  755.68
#Mann= 3 , 0 , 0
       0     .07       0   410.8    .045       0   459.7      .1       0
Bank Sta=410.8,459.7
XS Rating Curve= 0 ,0
Exp/Cntr=0.3,0.1

Type RM Length L Ch R = 1 ,3071.8  ,45.5,45.5,45.5
XS GIS Cut Line= 2
     1844587.611      521210.631      1844213.63      521890.531
#Sta/Elev= 30
       0     767     9.8  762.65    19.6  755.95    58.9  721.39    98.2  697.09
   117.9  682.33   137.5  665.51     167  635.33   176.8  630.12   206.3  628.25
   343.8  630.51   392.9  630.03   402.7  629.46   412.5  627.11   432.2  618.41
     442  616.54   451.8   616.3   471.5  616.61   481.3  618.71   510.8  633.69
   520.6  635.73     550  637.36   559.9  640.63   569.7  655.35   579.5  673.15
   589.3  684.27   599.2  691.86     717     772   746.5  789.43     776  802.68
#Mann= 3 , 0 , 0
       0     .08       0   432.2    .045       0   481.3      .1       0
Bank Sta=432.2,481.3
XS Rating Curve= 0 ,0
Exp/Cntr=0.3,0.1

Type RM Length L Ch R = 1 ,3026.4  ,309.3,313,316.7
XS GIS Cut Line= 2
       1844551.5      521182.159     1844177.518      521862.059
#Sta/Elev= 30
       0  765.32     9.8  760.38    19.6   753.5    49.1  728.16    58.9  720.88
    98.2  701.91     108  695.86   137.5  670.71     167  640.48   176.8  632.59
   186.6  629.48   196.4  628.81     334   629.5   412.5   627.9   422.4  625.42
     442  617.09   461.6   616.3   471.5  616.57   481.3  618.38   500.9  628.41
   510.8  632.39   520.6  634.51   559.9  638.38   569.7  648.35   579.5  666.41
   589.3  680.49     609  696.75   746.5  788.42   756.3  793.58     776  801.44
#Mann= 3 , 0 , 0
       0     .08       0     442    .045       0   481.3      .1       0
Bank Sta=442,481.3
XS Rating Curve= 0 ,0
Exp/Cntr=0.3,0.1

Type RM Length L Ch R = 1 ,2713.3  ,184.9,189,192.9
XS GIS Cut Line= 3
     1844300.997      521068.867     1844249.079       521182.54
     1843932.247      521584.492
#Sta/Elev= 30
       0  746.43    19.2  733.11    48.1  711.73    57.7  704.31    67.3  695.86
    76.9  684.72    96.1  658.59   105.7   647.6   115.4  640.49     125  637.64
   203.7  627.82   233.2   626.1   282.4  624.96     312  621.47   321.8  621.71
   341.5  624.88   351.3  623.79     371  617.13   390.7   616.2   420.2  616.95
   430.1  619.69   449.8   629.1   459.6  632.58   469.4  633.97     499   634.7
   508.8  637.47   518.7  644.46   538.4  660.66   548.2  667.49   636.8  725.03
#Mann= 3 , 0 , 0
       0     .08       0     371    .045       0   430.1      .1       0
Bank Sta=371,430.1
XS Rating Curve= 0 ,0
Exp/Cntr=0.3,0.1

Type RM Length L Ch R = 1 ,2524.4  ,36.2,36.2,36.2
XS GIS Cut Line= 4
      1844146.83      521035.534     1844103.951      521129.093
     1843830.481      521373.139      1843765.58      521488.659
#Sta/Elev= 30
       0  726.19    37.4  705.21    46.8  698.92    56.1  690.42    93.6  647.48
   102.9  640.18   112.6  635.89   131.8  630.12   141.5  628.54   151.1  627.87
     209  628.23   266.9  627.38   276.5  625.72   286.2  622.84   295.8  619.08
   305.5  616.94   315.1   616.1   344.1   615.8   353.7  615.89   363.4  617.04
   382.6   621.5   401.9  624.64   411.6  628.75   421.2  631.97   430.9  633.23
   478.9  633.98   488.4  635.41   497.8  638.81   545.2  663.55     602  696.87
#Mann= 3 , 0 , 0
       0     .08       0   305.5    .045       0   363.4      .1       0
Bank Sta=305.5,363.4
XS Rating Curve= 0 ,0
Exp/Cntr=0.3,0.1

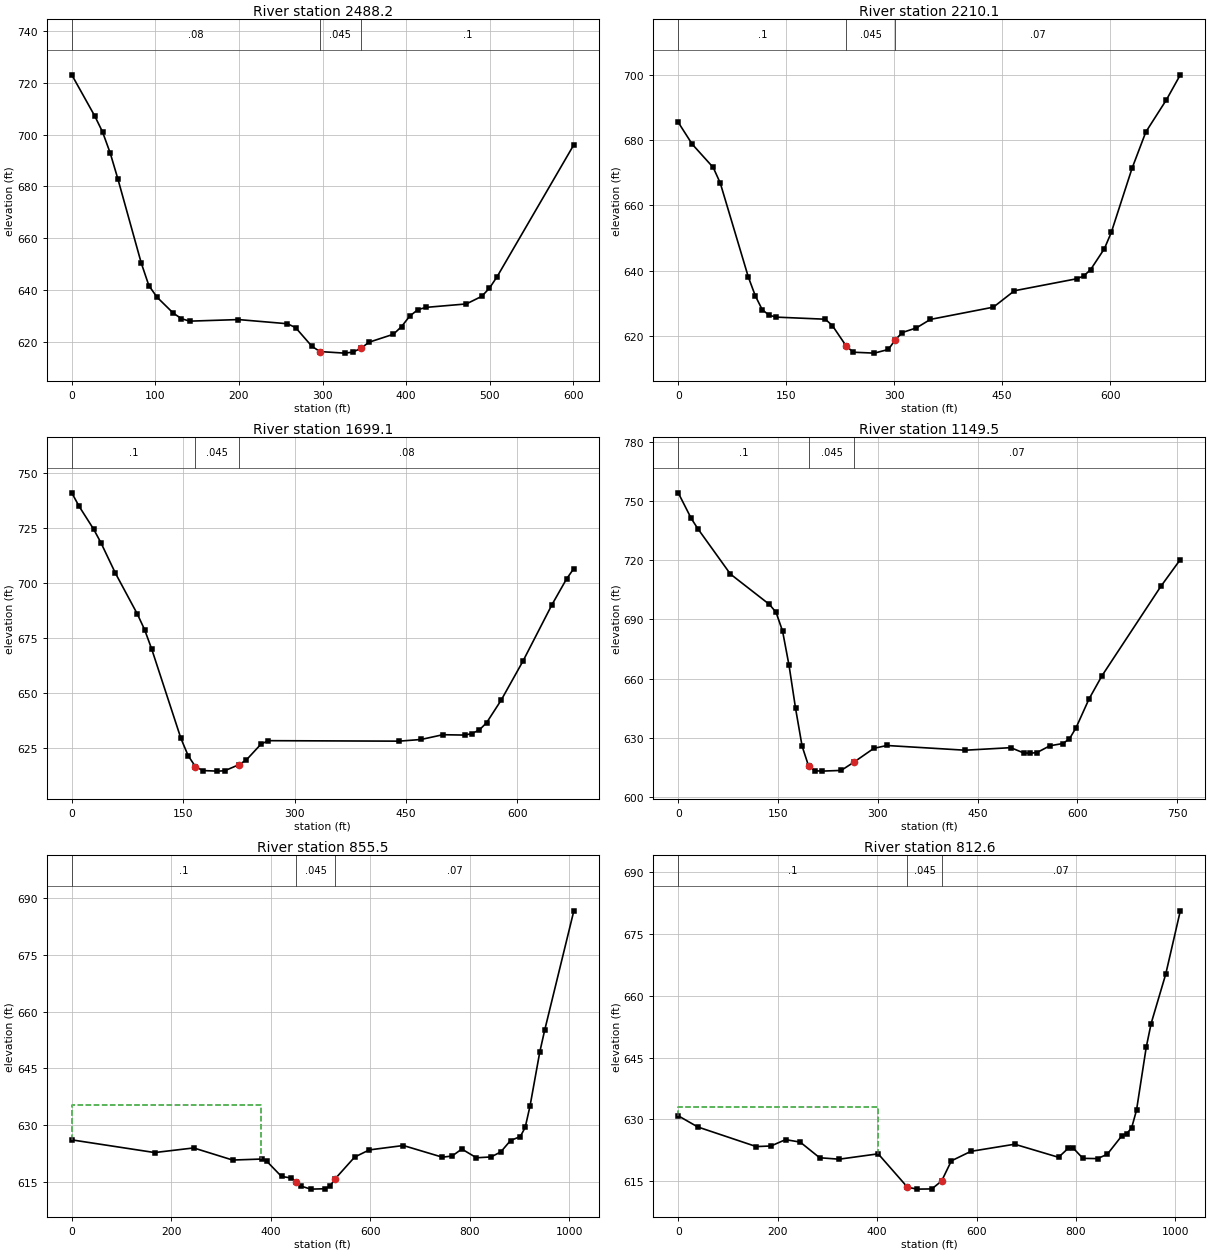
Type RM Length L Ch R = 1 ,2488.2  ,282.2,278.1,274.1
XS GIS Cut Line= 4
     1844108.288      521027.201     1844070.741      521111.398
      1843794.31      521358.087     1843724.955      521477.201
#Sta/Elev= 30
       0  723.09    27.7  707.06    36.9  700.96    46.1  692.75    55.3  682.71
      83  650.52    92.2  641.69   101.9  637.23   121.4  631.05   131.2  628.91
   140.9  627.95   199.4  628.56   257.9  626.95   267.7  625.46   287.2  618.23
   296.9   616.2   326.2   615.6   335.9  615.97   345.7  617.42   355.4   619.8
   384.7  622.89   394.4  625.85   404.2  629.89   413.9  632.38   423.7  633.27
   471.9   634.6   490.3  637.53   499.4  640.63   508.6  645.06   600.5  696.08
#Mann= 3 , 0 , 0
       0     .08       0   296.9    .045       0   345.7      .1       0
Bank Sta=296.9,345.7
XS Rating Curve= 0 ,0
Exp/Cntr=0.3,0.1

Type RM Length L Ch R = 1 ,2210.1  ,524.1,511.1,498
XS GIS Cut Line= 3
     1843836.026      520892.931     1843530.163      521283.451
      1843521.83      521484.492
#Sta/Elev= 30
       0  685.49    19.4  678.78    48.6  671.63    58.4  666.84    97.3  638.07
     107   632.3   116.7     628   126.4  626.31   136.2  625.74   204.2   625.1
     214  623.17   233.4  616.84   243.2  614.98   272.3   614.7   291.8  615.82
   301.5  618.79   311.2  621.02   330.7  622.43   350.2  625.04   437.7   628.8
   466.9  633.83   553.5  637.51   563.1  638.35   572.7   640.3   591.9  646.75
   601.4   651.7   630.2  671.34   649.4  682.51   678.1  692.43   697.3  700.05
#Mann= 3 , 0 , 0
       0      .1       0   233.4    .045       0   301.5     .07       0
Bank Sta=233.4,301.5
XS Rating Curve= 0 ,0
Exp/Cntr=0.3,0.1

Type RM Length L Ch R = 1 ,1699.1  ,556,549.5,543
XS GIS Cut Line= 2
     1843232.563       520709.33     1843175.894      521382.858
#Sta/Elev= 30
       0  741.03     9.8  734.94    29.4  724.52    39.2  718.37    58.8  704.45
    88.2  685.96      98  678.85   107.8  669.79   146.9  629.38   156.7  621.48
   166.5   616.5   176.3  614.73   195.9  614.47   205.7  614.61   225.3  617.44
   235.1  619.58   254.7  626.73   264.5  628.32   440.8   628.1   470.2  628.86
   499.6  631.03     529  630.86   538.8  631.56   548.6  633.18   558.4  636.46
     578  646.71   607.3  664.43   646.5   690.2   666.1  701.88   675.9   706.6
#Mann= 3 , 0 , 0
       0      .1       0   166.5    .045       0   225.3     .08       0
Bank Sta=166.5,225.3
XS Rating Curve= 0 ,0
Exp/Cntr=0.3,0.1

Type RM Length L Ch R = 1 ,1149.5  ,297.2,294,290.8
XS GIS Cut Line= 2
     1842627.163       520750.98     1842780.718      521489.964
#Sta/Elev= 30
       0  754.14    19.6  741.13    29.4  735.98    78.4  712.98   137.2  697.55
     147  693.61   156.8  684.14   166.6  666.64   176.4  644.86   186.2  625.78
     196  615.66   205.8  613.29   215.6   613.1     245  613.46   264.7  617.78
   294.1  624.66   313.7  626.09   431.3   623.7   499.9  624.99   519.5  622.29
   529.3   622.2   539.1  622.47   558.7  625.95   578.3  627.09   588.1  629.46
   597.9  634.97   617.5  649.63   637.1  661.46   725.4  706.67   754.8  720.31
#Mann= 3 , 0 , 0
       0      .1       0     196    .045       0   264.7     .07       0
Bank Sta=196,264.7
XS Rating Curve= 0 ,0
Exp/Cntr=0.3,0.1

Type RM Length L Ch R = 1 ,855.5   ,43,43,43
XS GIS Cut Line= 4
     1842102.212      520671.645     1842341.795      520917.478
     1842414.768      521120.584     1842637.629       521512.27
#Sta/Elev= 30
       0  626.11   166.7  622.76   245.2  623.98   323.6  620.78   382.5  621.05
   392.3  620.44   421.8  616.44   441.4  616.05   451.2  615.11     461   613.9
   480.6   613.1     510   613.2   519.8     614   529.7  615.83   568.9  621.57
   598.3  623.46   666.8  624.62   745.2  621.54   764.8  621.84   784.4  623.69
   813.8  621.38   843.2   621.6   862.8  622.93   882.4  625.94     902  626.98
   911.8  629.38   921.6  635.06   941.2  649.33     951  655.06  1009.7  686.61
#Mann= 3 , 0 , 0
       0      .1       0   451.2    .045       0   529.7     .07       0
#XS Ineff= 2 , 0
          381.32   635.3
Permanent Ineff=
       F       F
Bank Sta=451.2,529.7
XS Rating Curve= 0 ,0
Exp/Cntr=0.3,0.1

Type RM Length L Ch R = 1 ,812.6   ,78.4,74.7,70.9
XS GIS Cut Line= 4
      1842063.67      520691.437     1842303.254       520937.27
     1842376.227      521140.375     1842599.087      521532.062
#Sta/Elev= 30
       0  630.89    39.2  628.18   156.9  623.42   186.4  623.56   215.8   625.1
   245.2  624.51   284.4  620.71   323.6  620.36   402.1  621.66     461  613.56
   480.6   613.1     510  613.15   529.7  615.08   549.3  619.96   588.5  622.26
   676.6  623.99   764.8  620.82   784.4  623.02   794.2  623.07   813.8  620.56
   843.2   620.5   862.8  621.55   892.2  626.05     902  626.58   911.8  627.96
   921.6  632.23   941.2  647.53     951  653.26   980.4  665.25  1009.7  680.59
#Mann= 3 , 0 , 0
       0      .1       0     461    .045       0   529.7     .07       0
#XS Ineff= 2 , 0
           402.2  633.11
Permanent Ineff=
       F       F
Bank Sta=461,529.7
XS Rating Curve= 0 ,0
Exp/Cntr=0.3,0.1

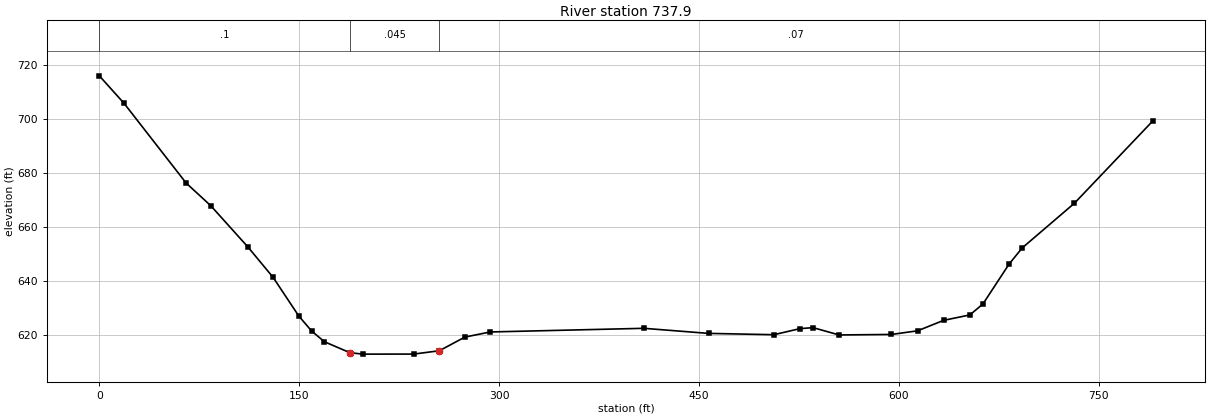
Type RM Length L Ch R = 1 ,737.9   ,754.7,737.9,720.9
XS GIS Cut Line= 4
     1842117.359      520994.886     1842236.359      521015.893
     1842386.367      521283.567     1842609.494      521569.522
#Sta/Elev= 30
       0  716.11    18.6   705.9    65.1  676.42    83.7  667.96   111.5  652.71
   130.4  641.46   149.6  627.19   159.2  621.65   168.8  617.64     188  613.58
   197.6  613.04   235.9  613.06   255.1  614.29   274.3  619.36   293.4  621.25
   408.5   622.6   457.1  620.72   506.1  620.23   525.7  622.48   535.5  622.85
   555.1  620.14   594.3  620.33   613.9  621.67   633.5  625.55   653.2  627.56
     663  631.62   682.6  646.38   692.4  652.35   731.6  668.91   790.4  699.38
#Mann= 3 , 0 , 0
       0      .1       0     188    .045       0   255.1     .07       0
Bank Sta=188,255.1
XS Rating Curve= 0 ,0
Exp/Cntr=0.3,0.1

Chan Stop Cuts=-1
Use User Specified Reach Order=0
Composite Channel Slope=5